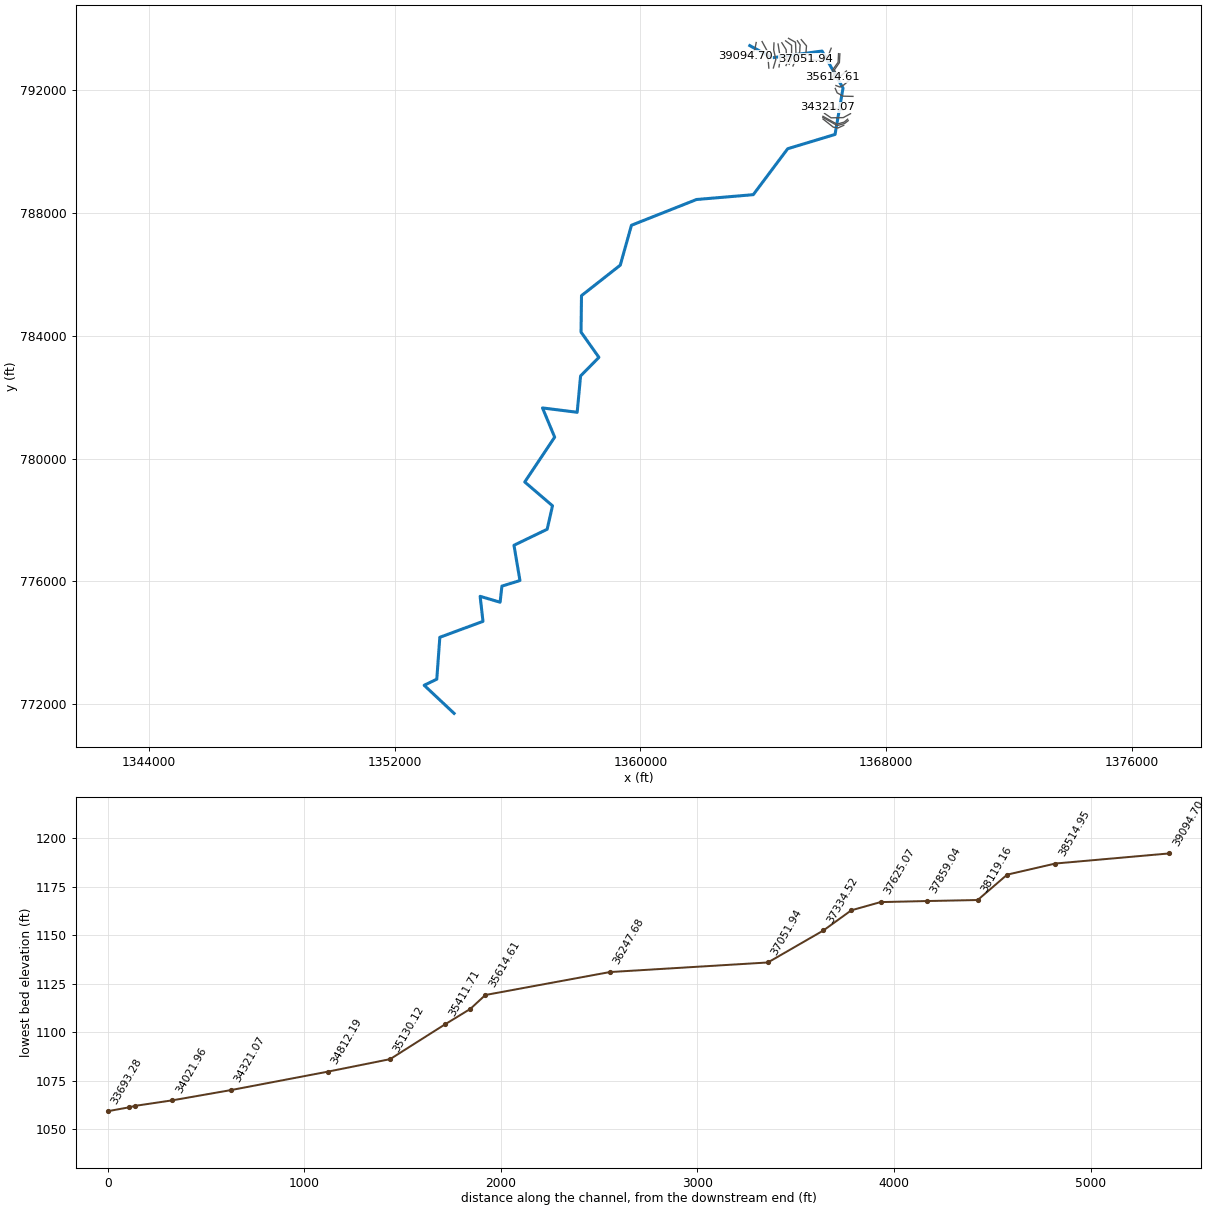
--- GladeCreek.prj (project) ---

Proj Title=Glade Creek
Current Plan=p01
Default Exp/Contr=0.3,0.1
English Units
Geom File=g01
Flow File=f01
Plan File=p01
Y Axis Title=Elevation
X Axis Title(PF)=Main Channel Distance
X Axis Title(XS)=Station
BEGIN DESCRIPTION:
END DESCRIPTION:
DSS Export Rating Curves= 0
DSS Export Rating Curve Sorted= 0
DSS Export Volume Flow Curves= 0
DXF OffsetX= 0
DXF OffsetY= 0
DXF ScaleX= 1
DXF ScaleY= 10

--- GladeCreek.p01 (plan) ---

Plan Title=GladeCreek LDS
Program Version=3.12
Short Identifier=LDS
Geom File=g01
Flow File=f01
Subcritical Flow
K Sum by GR= 0
Std Step Tol= 0.01
Critical Tol= 0.01
Num of Std Step Trials= 20
Max Error Tol= 0.3
Flow Tol Ratio= 0.001
Split Flow NTrial= 30
Split Flow Tol= 0.02
Split Flow Ratio= 0.02
Log Output Level= 0
Friction Slope Method= 1
Unsteady Friction Slope Method= 2
Unsteady Bridges Friction Slope Method= 1
Calc Critical at every XS
Parabolic Critical Depth
Global Vel Dist= 0 , 0 , 0
Global Log Level= 0
CheckData=True
Encroach Param=-1 ,0,0, 2
Encroach River=GladeCreek
Encroach Reach=Main
Encroach Node=39094.70
       1  354.03     380
Encroach Node=38514.95
       1  369.52   645.2
Encroach Node=38269.14
       1     277   555.1
Encroach Node=38119.16
       1     300     506
Encroach Node=37859.04
       1     244     556
Encroach Node=37625.07
       1     265     650
Encroach Node=37476.09
       1   385.1  404.33
Encroach Node=37334.52
       1     224     239
Encroach Node=37051.94
       1     450     475
Encroach Node=36247.68
       1   309.3   533.2
Encroach Node=35614.61
       1     590     860
Encroach Node=35538.03
       1     700   791.6
Encroach Node=35411.71
       1     312     362
Encroach Node=35130.12
       1     302     332
Encroach Node=34812.19
       1  341.88     412
Encroach Node=34321.07
       1     221     260
Encroach Node=34021.96
       1     524  550.13
Encroach Node=33834.95
       1     430     480
Encroach Node=33799.97
       1     460     510
Encroach Node=33693.28
       1     293     332
Encroach Node=33348.71
       1     605     685
Encroach Node=33256.75
       1     650     730
Encroach Node=33182.55
       1     462  523.09
Encroach Node=32797.62
       1     423     485
Encroach Node=32284.64
       1     400     440
Encroach Node=31569.57
       1     376   399.9
Encroach Node=30968.15
       1     540     584
Encroach Node=30233.45
       1     570     830
Encroach Node=28844.23
       1  662.85  708.38
Encroach Node=27861.55
       1     480     560
Encroach Node=27215.55
       1   560.4     605
Encroach Node=26637.26
       1     385     450
Encroach Node=25964.91
       1  267.61  489.75
Encroach Node=25569.53
       1     640     954
Encroach Node=25433.94
       1     640     952
Encroach Node=25096.17
       1     254   592.4
Encroach Node=24681.23
       1     475     550
Encroach Node=24590.73
       1     490     540
Encroach Node=24323.81
       1     410     476
Encroach Node=23822.72
       1     595  704.48
Encroach Node=23137.65
       1     489  572.97
Encroach Node=22544.15
       1     438  552.07
Encroach Node=21713.20
       1     445  568.59
Encroach Node=21113.97
       1     506     555
Encroach Node=20394.86
       1     575     620
Encroach Node=19499.87
       1  305.37  412.12
Encroach Node=19192.54
       1   708.5     821
Encroach Node=19109.02
       1     739     802
Encroach Node=18915.82
       1  454.32  516.03
Encroach Node=18227.41
       1  579.69   633.5
Encroach Node=17625.33
       1  365.74  415.87
Encroach Node=16914.64
       1  310.73  385.07
Encroach Node=16206.51
       1     658     720
Encroach Node=15764.53
       1     880  953.65
Encroach Node=15284.34
       1  657.84  695.62
Encroach Node=14527.54
       1     420     510
Encroach Node=13780.00
       1  479.75  550.28
Encroach Node=12806.80
       1     600     678
Encroach Node=12076.03
       1  561.34     805
Encroach Node=11540.03
       1    1390    1460
Encroach Node=10670.31
       1 2032.95 2125.48
Encroach Node=10049.05
       1     473  541.25
Encroach Node=9433.596
       1  626.26   699.9
Encroach Node=8524.434
       1     536     626
Encroach Node=7987.905
       1  327.02     399
Encroach Node=7658.222
       1     525     680
Encroach Node=7610.096
       1     535     690
Encroach Node=7485.738
       1  339.84  512.33
Encroach Node=6920.967
       1   455.5  552.95
Encroach Node=6022.355
       1     745     838
Encroach Node=5092.741
       1     428     529
Encroach Node=4609.912
       1  451.69     558
Encroach Node=3744.177
       1     569     668
Encroach Node=2655.739
       1  263.98  322.59
Encroach Node=1661.538
       1     420     490
Encroach Node=1417.58
       1     685     765
Encroach Node=1317.619
       1   650.5     724
Encroach Node=765.75
       1     482     565
Encroach Node=328.34
       1     297     411
Computation Interval=1HOUR
Output Interval=1HOUR
Run HTab= 0
Run UNet= 0
Run PostProcess= 0
UNET Theta= 1
UNET Theta Warmup= 1
UNET ZTol= 0.02
UNET ZSATol= 0.05
UNET MxIter= 20
UNET MaxInSteps= 0
UNET DtIC= 0
UNET DtMin= 0
UNET MaxCRTS= 20
UNET WFStab= 2
UNET SFStab= 1
UNET WFX= 1
UNET SFX= 1
UNET DSS MLevel= 4
UNET DZMax Abort= 100
UNET Convert EG Bridges=-1
UNET Use Existing IB Tables=-1
UNET Froude Reduction=False
UNET Froude Limit= 1
UNET Froude Power= 10
Instantaneous Interval=1HOUR
Write IC File= 0
Echo Input=False
Echo Output=False
Write Detailed= 0
Detailed Automatic Start=False, 10

--- GladeCreek.f01 (steady flow) ---

Flow Title=GladeCreek
Program Version=3.12
Number of Profiles= 2
Profile Names=P100yr,Encr
River Rch & RM=GladeCreek,Main            ,39094.70
     110     110
River Rch & RM=GladeCreek,Main            ,38514.95
     150     150
River Rch & RM=GladeCreek,Main            ,38269.14
     200     200
River Rch & RM=GladeCreek,Main            ,37625.07
     230     230
River Rch & RM=GladeCreek,Main            ,37051.94
     280     280
River Rch & RM=GladeCreek,Main            ,35614.61
     530     530
River Rch & RM=GladeCreek,Main            ,34812.19
     630     630
River Rch & RM=GladeCreek,Main            ,33348.71
    1300    1300
River Rch & RM=GladeCreek,Main            ,31569.57
    1430    1430
River Rch & RM=GladeCreek,Main            ,28844.23
    1620    1620
River Rch & RM=GladeCreek,Main            ,27215.55
    1840    1840
River Rch & RM=GladeCreek,Main            ,25096.17
    2500    2500
River Rch & RM=GladeCreek,Main            ,23137.65
    2760    2760
River Rch & RM=GladeCreek,Main            ,15764.53
    3000    3000
River Rch & RM=GladeCreek,Main            ,13780.00
    4030    4030
River Rch & RM=GladeCreek,Main            ,10670.31
    4550    4550
Boundary for River Rch & Prof#=GladeCreek,Main            , 1
Up Type= 0
Dn Type= 3
Dn Slope=0.003905
DSS Import GetInterval= 0
DSS Import GetPeak= 0
DSS Import FillOption= 0

--- GladeCreek.g01 (geometry) ---

Geom Title=NCFMP Lidar
Program Version=3.12

River Reach=GladeCreek      ,Main
Reach XY= 30
  1363562.878037   793450.942307  1364291.499093   793054.809977
  1365916.882042   793274.060634  1366599.593178    792067.18327
  1366340.248665   790558.248798  1364798.002275   790093.000552
  1363676.251241   788596.191061  1361828.631628   788438.998898
   1359709.07374   787599.723449  1359345.001584   786300.251993
  1358082.131058   785307.500357  1358067.250293   784120.381282
  1358649.549489   783296.971518  1358052.500565   782692.630338
  1357941.594668   781508.903977  1356811.498611   781650.558793
  1357208.355789   780698.608959  1356234.315868   779238.873371
  1357137.753202   778463.690564  1356963.750992   777698.561897
  1355882.882132   777177.628477  1356077.745223   776029.187926
  1355490.501728   775847.309148  1355430.749282   775322.500961
  1354780.501071    775515.00068  1354873.790442   774699.654867
  1353468.130377   774180.499295  1353368.784475   772815.387385
   1352957.74833   772617.879385  1353933.042789   771702.574905

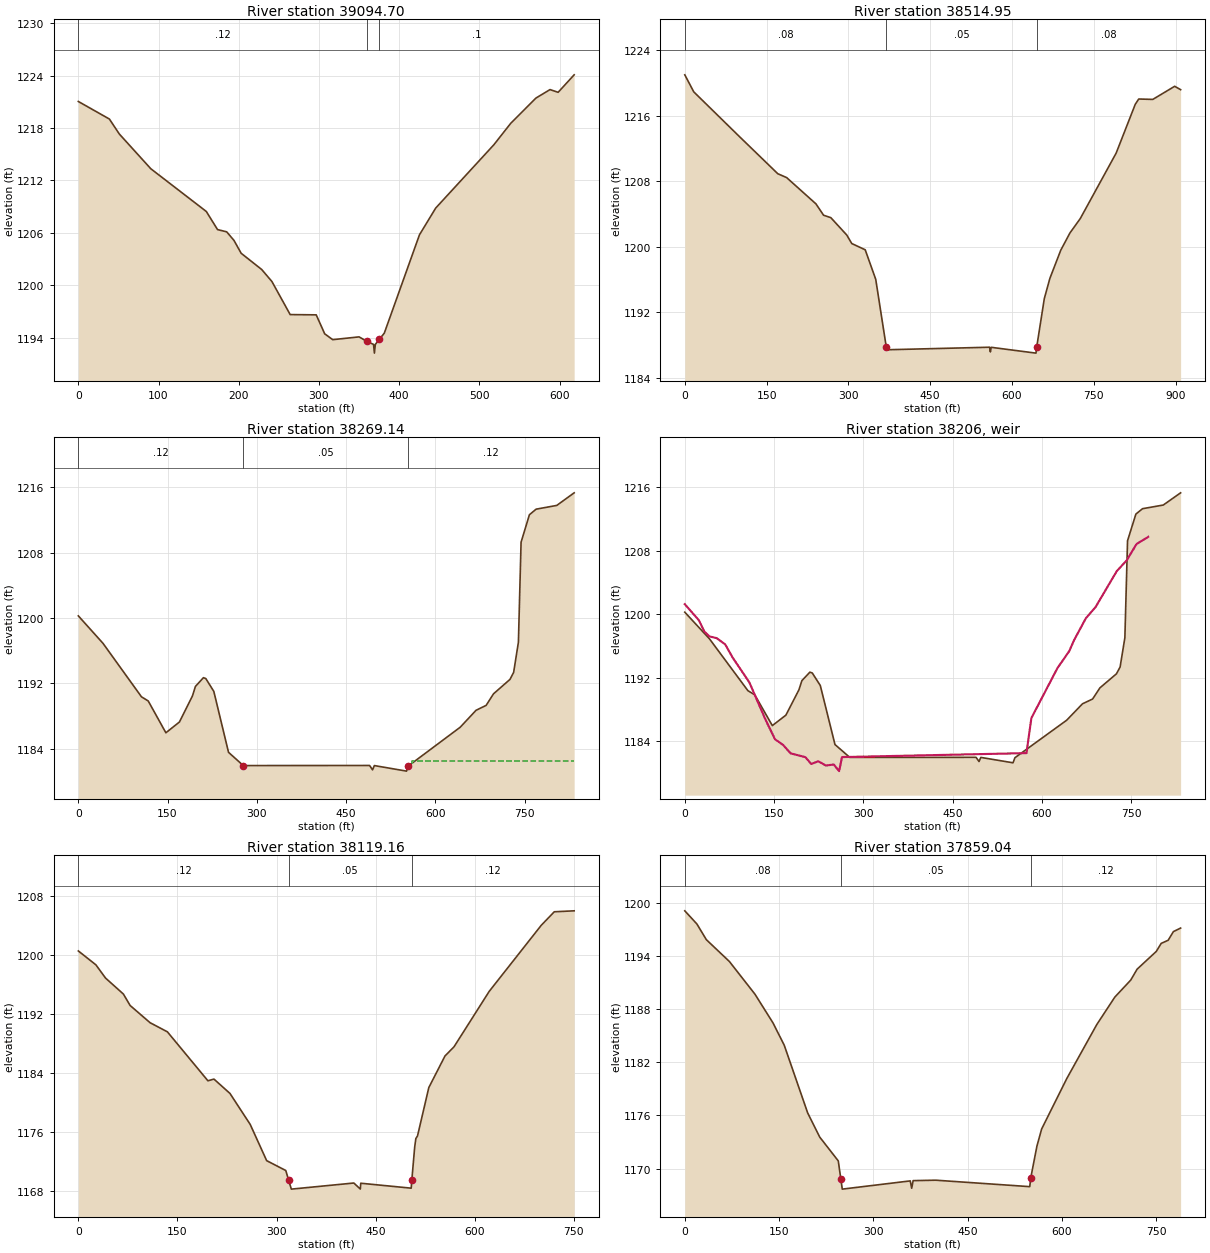
Type RM Length L Ch R = 1 ,39094.70,545.39,579.75,613.61
XS GIS Cut Line= 3
  1363771.778068   793551.249473   1363719.37427   793285.736951
  1363418.925835   793111.057623
#Sta/Elev= 30
       0 1221.03   38.72 1219.02   51.08 1217.31   90.38 1213.33  159.57 1208.44
  173.55 1206.37  184.99 1206.11  194.13 1205.12  202.99 1203.66  228.63  1201.8
  241.39 1200.42  264.13 1196.64  296.59 1196.61  307.17 1194.44  317.16 1193.77
  350.02 1194.09  359.83 1193.57  368.05 1193.23  369.14 1192.23  370.27 1193.23
  375.36 1193.81  381.48 1194.52  425.31 1205.77  445.55 1208.83  518.01 1216.07
  539.08 1218.53  570.54 1221.42  588.07 1222.39   598.2 1222.08  618.17 1224.08
#Mann= 3 , 0 , 0
       0     .12       0  359.83     .05       0  375.36      .1       0
Bank Sta=359.83,375.36
Exp/Cntr=0.3,0.1

Type RM Length L Ch R = 1 ,38514.95,241.61,245.8,250
XS GIS Cut Line= 3
  1363963.925282   793582.691762   1364138.60461   793261.281817
  1364184.021254   792719.775993
#Sta/Elev= 30
       0 1220.98   16.47  1218.9  101.33 1213.37  170.57 1208.91  186.77 1208.44
  240.54 1205.23  254.45 1203.85  267.79 1203.55  297.02 1201.43  306.23 1200.39
  330.84 1199.63  350.16 1196.02  369.59 1187.71  370.02 1187.43   558.9 1187.74
  560.36 1187.17  561.81 1187.73  643.96 1187.02   645.2 1187.71  659.25 1193.67
  669.51 1196.15   689.5 1199.59  706.32 1201.69  725.21 1203.44  791.03 1211.43
  826.08 1217.39  832.44 1218.03  858.19 1217.98   898.3 1219.58  909.22 1219.17
#Mann= 3 , 0 , 0
       0     .08       0  369.59     .05       0   645.2     .08       0
Bank Sta=369.59,645.2
Exp/Cntr=0.5,0.3

Type RM Length L Ch R = 1 ,38269.14,150,149.98,170
XS GIS Cut Line= 4
  1364351.713381   793537.275164  1364341.232603   793313.685615
  1364411.104334   792999.262871  1364330.751871    792723.26957
#Sta/Elev= 30
       0 1200.27   41.48 1196.91  106.12 1190.37   117.5 1189.86  147.15 1185.97
  169.94 1187.29  191.88 1190.49   196.8 1191.64  210.27 1192.71  214.31  1192.6
  227.73 1191.03  252.45 1183.58  277.31 1181.96  489.52 1181.97  494.53 1181.44
  497.56 1181.96  551.68 1181.28  554.87 1181.92  641.88 1186.65  668.46 1188.72
  685.42 1189.32  697.76 1190.73  725.51  1192.5  731.68 1193.36  739.68 1197.05
  744.17 1209.28  758.17 1212.64  769.41 1213.32  804.21 1213.78  833.38 1215.32
#Mann= 3 , 0 , 0
       0     .12       0  277.31     .05       0  554.87     .12       0
#XS Ineff= 2 , 0
       0     265  1182.5     560       0  1182.5
Permanent Ineff=
       F       F
Bank Sta=277.31,554.87
Exp/Cntr=0.5,0.3

Type RM Length L Ch R = 5 ,38206   ,,,
IW Pilot Flow=0
#Inline Weir SE= 30
       0 1201.28   23.46 1199.27    32.9 1197.83   41.48 1197.21    53.6    1197
   67.95  1196.2   80.11 1194.59  108.68 1191.39  136.04 1186.65  151.71 1184.24
   165.1 1183.54  177.85 1182.47  202.66 1181.99  212.42 1181.13  224.38 1181.47
  237.01 1180.94  250.41 1181.06  259.37 1180.23  264.23    1182  574.27  1182.5
  582.51 1186.92  626.32 1193.22  646.19 1195.36  654.49 1196.78  674.24 1199.52
  690.36 1200.91  726.08 1205.45  742.84 1206.81  759.37 1208.87     779 1209.77
IW Dist,WD,Coef,Skew,MaxSub,Min_El,Is_Ogee,SpillHt,DesHd
120,20,2.6,0,0.95,, 0 ,,,0,0,

Type RM Length L Ch R = 1 ,38119.16,263.56,260.12,256.64
XS GIS Cut Line= 4
  1364484.469643   793502.339299  1364533.379864    793194.90371
  1364547.354219   792995.769294  1364515.911931   792758.205436
#Sta/Elev= 30
       0 1200.56   26.63 1198.67   41.15 1196.88   68.24  1194.7    78.4 1193.15
  108.61 1190.81  134.82 1189.57  196.16 1182.92   205.3 1183.15  229.55  1181.2
   260.2 1176.99  285.08 1172.07  314.01 1170.73   318.4 1169.41  322.44  1168.2
  417.07 1169.03  426.82 1168.21  427.54    1169  503.89 1168.33  504.84 1169.43
  509.16 1173.91  510.93 1175.07  513.45 1175.43  530.55    1182  555.03 1186.29
  568.64 1187.53  622.07 1195.08  700.81 1204.05  720.47 1205.88  750.56 1206.01
#Mann= 3 , 0 , 0
       0     .12       0   318.4     .05       0  504.84     .12       0
Bank Sta=318.4,504.84
Exp/Cntr=0.5,0.3

Type RM Length L Ch R = 1 ,37859.04,239.1,233.9,230.4
XS GIS Cut Line= 4
  1364606.745172   793544.262319  1364746.488635   793320.672816
  1364777.930876   792883.974543  1364742.995011   792803.622033
#Sta/Elev= 30
       0 1199.13   19.29 1197.64   34.29 1195.87      71  1193.4  111.73  1189.7
  140.38 1186.46  158.31 1183.93  195.59 1176.28  214.77 1173.55  244.27 1170.86
  248.36  1168.8  250.62 1167.67  358.81  1168.6  361.11 1167.77   363.4 1168.63
  399.35 1168.68  548.96 1167.95  550.68 1168.97  560.41 1172.53  567.93 1174.47
  608.02 1180.18  655.66 1186.27  684.42 1189.38  709.71  1191.3  719.82 1192.53
  750.36 1194.54  758.19 1195.45  769.25  1195.8  777.59 1196.78  789.11 1197.18
#Mann= 3 , 0 , 0
       0     .08       0  248.36     .05       0  550.68     .12       0
Bank Sta=248.36,550.68
Exp/Cntr=0.5,0.3

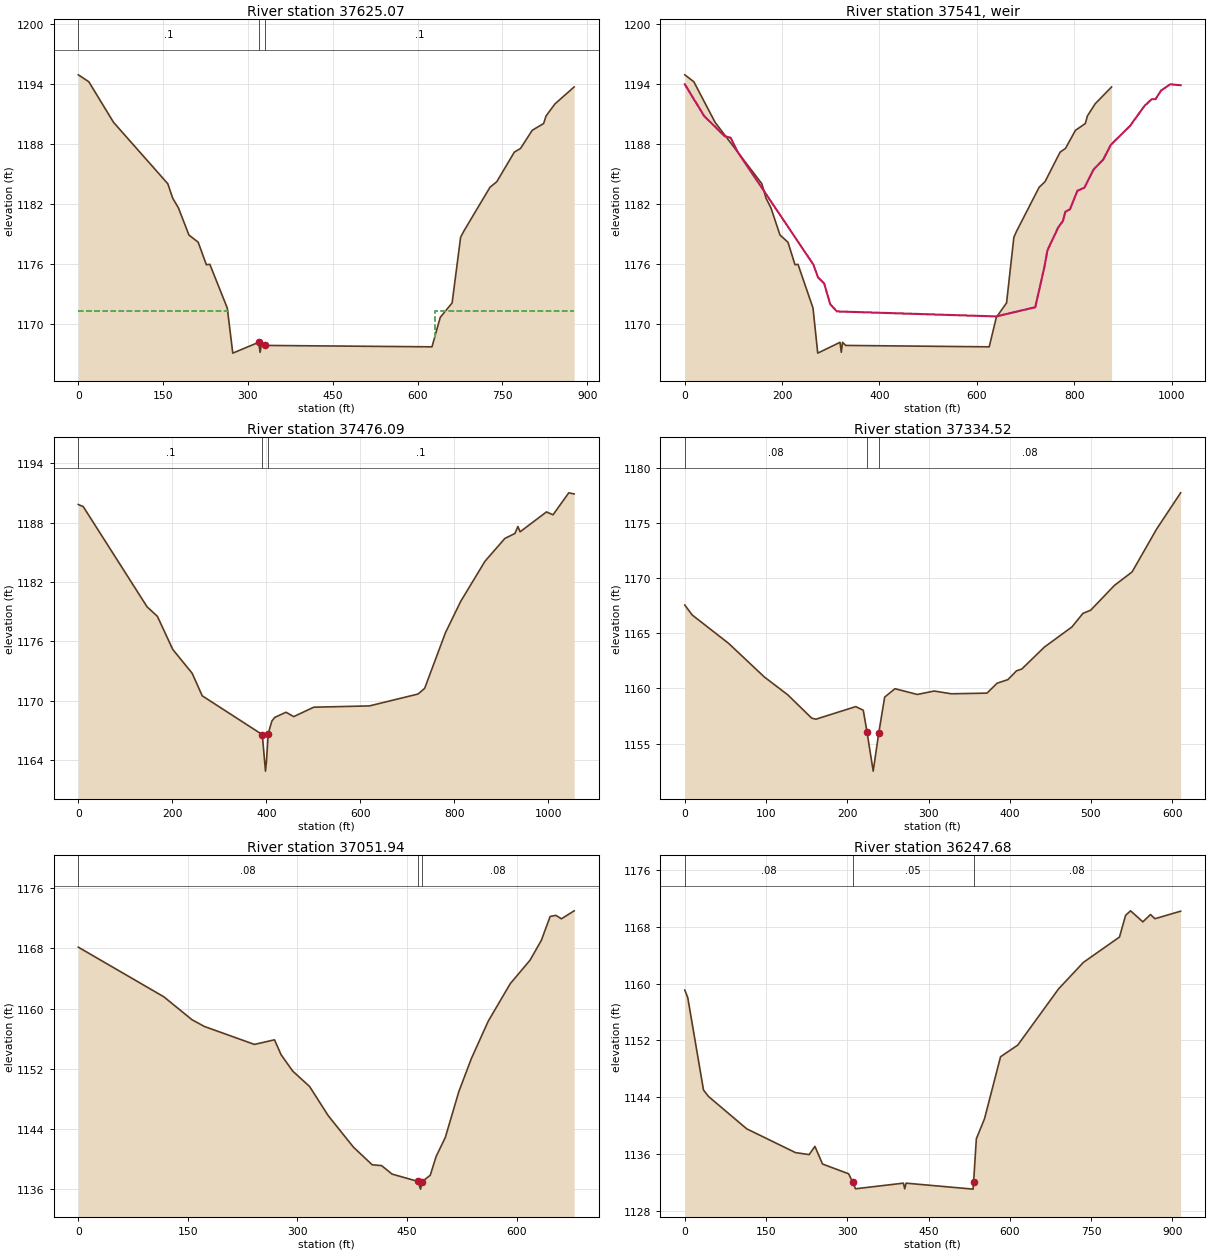
Type RM Length L Ch R = 1 ,37625.07,142,148.98,154
XS GIS Cut Line= 4
  1364730.189139   793605.905163  1364925.200729   793461.169952
  1364923.677225   793022.393851  1364847.500813   792842.617488
#Sta/Elev= 30
       0 1194.96   18.52 1194.27   62.24 1190.21  158.24 1184.07  166.97 1182.62
     177 1181.66  195.62 1178.94  211.99 1178.22  226.43 1175.97  232.57 1176.01
  263.42 1171.64  273.15 1167.13  318.89 1168.21  321.51 1167.21  324.11 1168.21
  330.65  1167.9  625.43 1167.76  640.08 1170.71  661.05 1172.15  676.06 1178.71
  681.63 1179.32  728.06 1183.72  740.03 1184.27  771.08 1187.23  782.08  1187.6
  802.63 1189.41  822.87 1190.09  827.11 1190.84   842.9 1192.05  876.88 1193.75
#Mann= 3 , 0 , 0
       0      .1       0  318.89    .045       0  330.65      .1       0
#XS Ineff= 2 , 0
       0     265  1171.3     630       0  1171.3
Permanent Ineff=
       F       F
Bank Sta=318.89,330.65
Exp/Cntr=0.5,0.3

Type RM Length L Ch R = 5 ,37541   ,,,
IW Pilot Flow=0
#Inline Weir SE= 30
       0 1194.01    39.8 1190.84   81.94 1188.83   94.29 1188.66  107.88 1187.31
   264.1 1175.99  273.53 1174.72  286.47 1174.08  298.79 1172.02   312.4  1171.3
  639.77  1170.8  720.04 1171.72  738.99 1175.78  744.91 1177.39  767.18  1179.7
  776.75 1180.34  781.87 1181.26  791.35 1181.51  806.68 1183.37     821 1183.67
  839.77 1185.49  859.47 1186.47  875.12 1187.95  915.01 1189.87  944.23 1191.84
   959.1 1192.52  967.21 1192.53  978.14 1193.37   997.3 1194.01 1018.69 1193.92
IW Dist,WD,Coef,Skew,MaxSub,Min_El,Is_Ogee,SpillHt,DesHd
120,20,2.6,0,0.95,, 0 ,,,0,0,

Type RM Length L Ch R = 1 ,37476.09,145.43,141.58,138.51
XS GIS Cut Line= 4
  1364824.647879   793688.175685  1365051.653566   793560.199297
  1365074.506499   793034.582069  1364969.383045   792787.770504
#Sta/Elev= 30
       0 1189.83   10.41 1189.62   146.3 1179.49  168.27 1178.53  200.92 1175.19
  242.16 1172.78  263.65  1170.5  391.44 1166.58  398.22 1162.89   400.3  1163.9
  404.03 1166.68  411.76 1167.95  417.96 1168.32  441.88 1168.84  458.29  1168.4
  500.94 1169.35  619.41 1169.48  722.77 1170.68  736.93 1171.26  781.19 1176.88
  813.44 1180.03  865.28  1184.1  907.52  1186.4  929.09 1186.91  935.24 1187.61
  939.95 1187.07  996.04 1189.08 1010.06 1188.79 1043.47 1191.01 1054.97  1190.9
#Mann= 3 , 0 , 0
       0      .1       0  391.44    .045       0  404.03      .1       0
Bank Sta=391.44,404.03
Exp/Cntr=0.5,0.3

Type RM Length L Ch R = 1 ,37334.52,281.24,282.56,281.37
XS GIS Cut Line= 5
  1365113.687706     793608.8711  1365203.859103   793475.068358
  1365198.041596   793405.258234  1365189.315337   793251.094172
  1365125.322719   793035.846247
#Sta/Elev= 30
       0 1167.55    9.16 1166.65   53.85 1164.09   97.79 1161.05  126.72 1159.43
  156.15 1157.32  161.35 1157.22  210.47 1158.36  219.71 1158.03  224.29 1156.08
  231.93 1152.52  238.77 1155.97  246.03 1159.22  258.73 1159.98  286.21 1159.46
  306.96 1159.77  328.24 1159.52  371.98 1159.58   384.5 1160.48  397.68  1160.8
  408.36  1161.6  414.82 1161.76  442.54 1163.74  476.57 1165.57  490.14  1166.8
  499.71 1167.09  528.71 1169.32  550.63 1170.55  580.72 1174.42  610.37 1177.71
#Mann= 3 , 0 , 0
       0     .08       0  224.29     .05       0  238.77     .08       0
Bank Sta=224.29,238.77
Exp/Cntr=0.3,0.1

Type RM Length L Ch R = 1 ,37051.94,828.99,804.26,778.4
XS GIS Cut Line= 3
  1365239.084284   793645.576338  1365410.269988   793442.948299
    1365378.8277    793030.70516
#Sta/Elev= 30
       0 1168.16  116.99 1161.57   155.6 1158.52  172.66 1157.62  241.03 1155.24
  268.53 1155.85  277.48 1153.88  293.52 1151.69  316.54 1149.65  342.08 1145.77
  376.64 1141.58  402.31 1139.24  415.04 1139.14  429.42 1138.01  464.66 1137.04
   468.5 1136.01  470.36 1136.99  481.75 1137.86  489.76 1140.35  502.37 1142.89
  520.81 1148.96  538.02 1153.37  561.06 1158.32  591.15  1163.3  618.37 1166.44
  633.84 1169.08  645.83 1172.24  653.64 1172.39  661.26 1171.93   678.7 1172.99
#Mann= 3 , 0 , 0
       0     .08       0  464.66     .05       0  470.36     .08       0
Bank Sta=464.66,470.36
Exp/Cntr=0.3,0.1

Type RM Length L Ch R = 1 ,36247.68,622.4,633.075,643.6
XS GIS Cut Line= 4
  1366213.794804   793366.089414  1366129.948763   793149.487066
  1365888.891328   792967.820583   1365508.09043   792985.288516
#Sta/Elev= 30
       0 1159.08    5.46 1158.03   34.52 1145.02   43.69 1144.11  114.31 1139.55
  204.37  1136.2  229.52 1135.92  240.18 1137.08  254.31 1134.59  302.44 1133.22
  310.15    1132  315.19 1131.11  403.56  1131.9  406.03  1131.1  408.51  1131.9
  532.21 1131.06  533.11    1132  538.18 1138.14  553.24 1140.96   582.9  1149.7
  614.67 1151.34   689.9 1159.24  735.78 1162.98  802.45 1166.55  813.74 1169.61
  822.91 1170.24   845.6 1168.69  859.73 1169.72  867.93 1169.13  915.31 1170.19
#Mann= 3 , 0 , 0
       0     .08       0  310.15     .05       0  533.11     .08       0
Bank Sta=310.15,533.11
Exp/Cntr=0.5,0.3

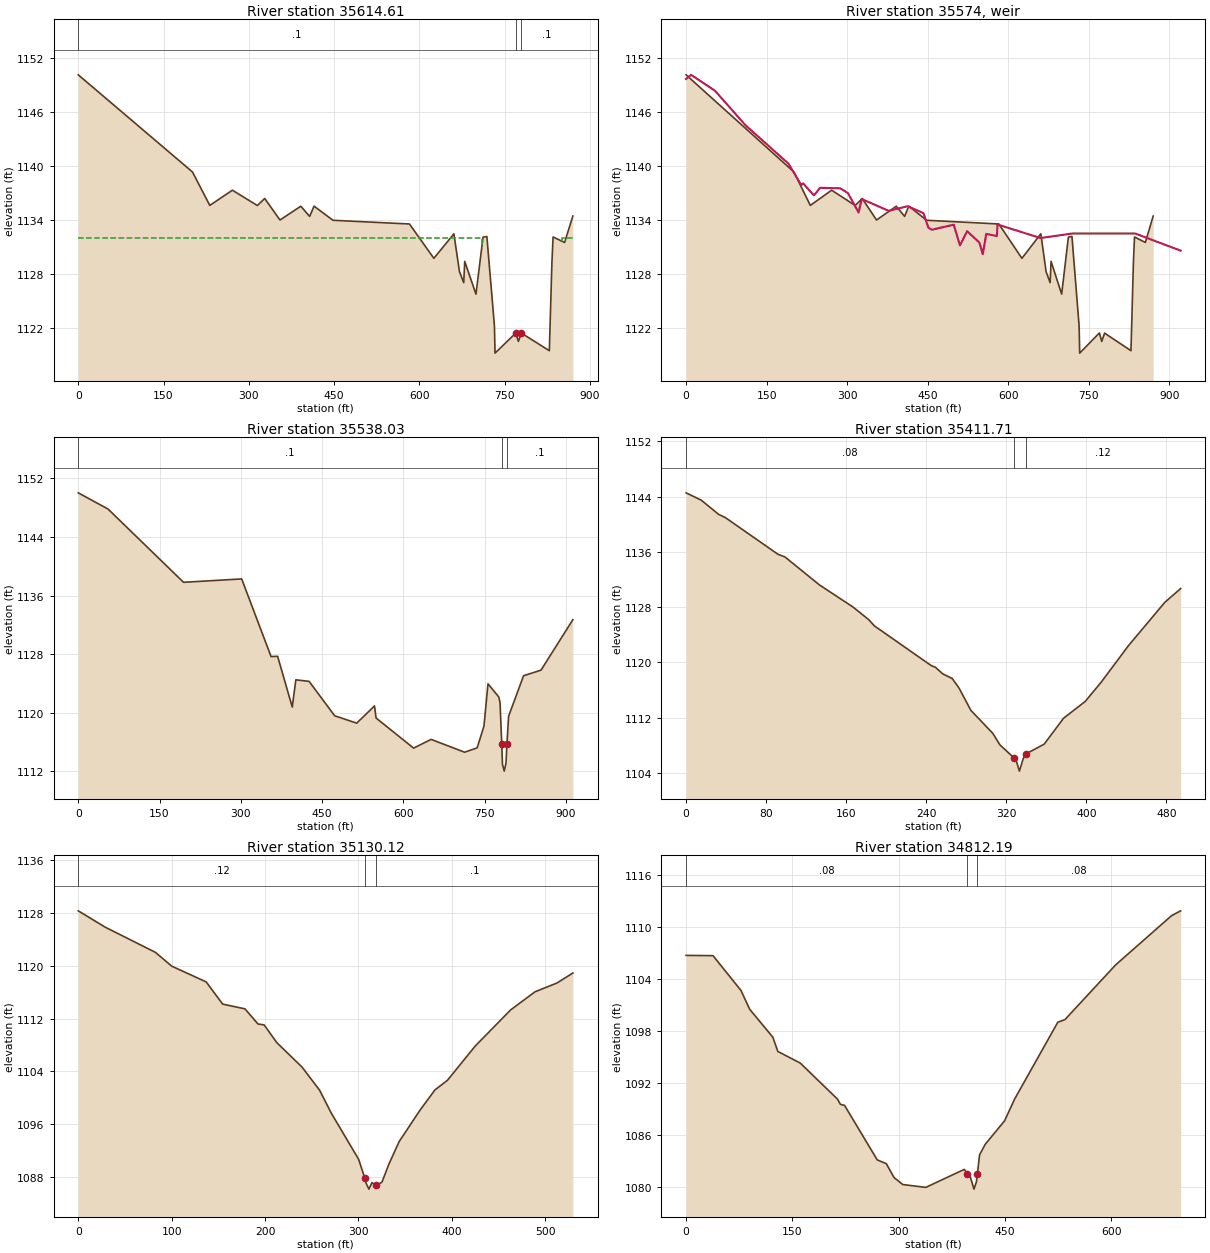
Type RM Length L Ch R = 1 ,35614.61,68,76.58,84
XS GIS Cut Line= 6
  1366453.774652   793189.244435  1366439.844767    792907.96667
  1366265.083157   792665.269501   1366254.43516   792650.892907
  1366320.948495   792535.369746  1366247.433756   792418.679637
#Sta/Elev= 30
       0 1150.11  200.86 1139.33  231.32 1135.62  271.07 1137.31  314.93 1135.61
  327.93 1136.39  354.68    1134  391.36 1135.53   406.9  1134.4  414.66 1135.54
  447.95 1133.97  582.45 1133.56  625.34 1129.75  660.57 1132.47  670.38 1128.27
  677.88 1127.05  679.63 1129.41  699.38 1125.78  711.88  1132.1  718.56 1132.17
  731.89 1122.23  732.92 1119.23  769.65 1121.47  773.97 1120.53  779.31 1121.45
  828.42  1119.5  832.94 1129.24     835 1132.12  855.24 1131.51   869.8 1134.44
#Mann= 3 , 0 , 0
       0      .1       0  769.65    .045       0  779.31      .1       0
#XS Ineff= 2 , 0
       0     710    1132     850       0    1132
Permanent Ineff=
       F       F
Bank Sta=769.65,779.31
Exp/Cntr=0.5,0.3

Type RM Length L Ch R = 5 ,35574   ,,,
IW Pilot Flow=0
#Inline Weir SE= 30
       0 1149.65     9.3 1150.11   53.71 1148.35  111.03 1144.49  190.71 1140.25
   214.5 1137.88   217.8 1138.07  238.15 1136.73  249.41 1137.57  287.24 1137.52
  301.43 1136.98  321.21 1134.83  327.09 1136.33  377.08 1135.02  412.63 1135.53
  441.88 1134.77  451.16 1133.16  457.51 1132.92  498.41 1133.48  509.91 1131.19
  523.29 1132.76  546.09  1131.5  552.48 1130.21  558.92 1132.46   578.7 1132.22
     580  1133.5     660    1132  718.56  1132.5  836.45  1132.5     921  1130.6
IW Dist,WD,Coef,Skew,MaxSub,Min_El,Is_Ogee,SpillHt,DesHd
56,10,2.6,0,0.95,, 0 ,,,0,0,

Type RM Length L Ch R = 1 ,35538.03,137.2,126.319,110.58
XS GIS Cut Line= 6
  1366496.949975   793184.576832  1366481.780267   792897.519233
  1366317.247233   792659.471459  1366390.762019   792519.443385
   1366340.55847      792411.459  1366290.282045   792380.988454
#Sta/Elev= 30
       0 1150.03   54.91 1147.82  194.31 1137.82  301.63 1138.28  355.86 1127.68
  367.93 1127.72  394.96  1120.8  401.56 1124.51  426.03  1124.3   473.3  1119.6
  513.96  1118.6  546.73 1120.95  549.67  1119.3  618.91 1115.19  651.22 1116.38
  713.11 1114.63  736.24 1115.23  748.75 1118.19  756.24 1123.97  776.15 1122.17
  778.46  1121.4   781.6 1115.72  782.92 1112.99  786.17 1112.05   789.4 1113.14
  791.17 1115.72  794.24 1119.54  821.91 1125.07  854.07 1125.83  912.86 1132.72
#Mann= 3 , 0 , 0
       0      .1       0   781.6    .045       0  791.17      .1       0
Bank Sta=781.6,791.17
Exp/Cntr=0.5,0.3

Type RM Length L Ch R = 1 ,35411.71,290,281.59,275
XS GIS Cut Line= 3
  1366709.884076   792625.449128   1366440.87793   792384.391693
  1366308.121669   792373.910914
#Sta/Elev= 30
       0 1144.56   15.25 1143.49   32.54 1141.44   39.19 1140.98   91.94 1135.65
   98.78 1135.28  133.39 1131.21  166.85 1128.02  182.57 1126.19  188.12  1125.3
   245.1 1119.53  249.11 1119.31  256.57 1118.34  266.05 1117.66  272.82 1116.29
  284.62 1113.06  306.61 1109.72  313.71 1108.05  327.87 1106.16  329.41 1106.08
  333.14 1104.25  336.86 1106.01  339.34 1106.71  358.01 1108.17  377.34 1111.92
  398.86 1114.33  414.95 1117.14  442.33 1122.45  478.39 1128.68  494.38  1130.7
#Mann= 3 , 0 , 0
       0     .08       0  327.87     .05       0  339.34     .12       0
Bank Sta=327.87,339.34
Exp/Cntr=0.3,0.1

Type RM Length L Ch R = 1 ,35130.12,345.36,317.92,284.54
XS GIS Cut Line= 5
  1366811.237491   792330.473005  1366622.168344   792167.582684
  1366566.901986   792144.312658  1366502.909369   792100.681313
  1366369.106627   792150.130165
#Sta/Elev= 30
       0  1128.3   28.77 1125.83   82.65 1122.01  100.01 1119.93  136.97 1117.54
  154.61 1114.18   178.5 1113.46  192.46 1111.17  199.05 1111.03  212.67 1108.34
  239.73 1104.63  258.49 1101.13  270.99 1097.66  300.25 1090.68  306.67  1087.9
  307.92 1087.17  311.24 1086.17  314.47 1087.16  319.07 1086.72  325.15 1087.22
  332.74 1089.99  343.68 1093.38  366.19 1098.17  381.96 1101.19  395.29 1102.64
  425.13 1107.84  463.01  1113.3  489.07 1116.04  512.55 1117.37  529.63 1118.88
#Mann= 3 , 0 , 0
       0     .12       0  306.67     .05       0  319.07      .1       0
Bank Sta=306.67,319.07
Exp/Cntr=0.3,0.1

Type RM Length L Ch R = 1 ,34812.19,486,491.12,496
XS GIS Cut Line= 4
  1366922.992847   791797.469225   1366605.07648    791804.45638
  1366409.435642   791912.757554  1366346.551111   792055.994593
#Sta/Elev= 30
       0 1106.71   37.98 1106.68   77.54 1102.65   89.72 1100.49   122.4 1097.26
  129.52 1095.61  161.07 1094.27  213.86 1090.09  217.73  1089.5  223.64 1089.38
  269.77 1083.08  282.58 1082.64  293.46 1081.04  305.87 1080.23  338.22  1079.9
  392.67 1081.98   397.1 1081.48  401.34 1081.06  406.29  1079.7  409.78 1080.55
   411.1 1081.43  414.21 1083.67  422.27 1084.89  449.41 1087.58  463.76 1090.12
  524.66 1098.99  534.67 1099.29  606.46 1105.63  685.28 1111.31  698.04 1111.86
#Mann= 3 , 0 , 0
       0     .08       0   397.1     .05       0   411.1     .08       0
Bank Sta=397.1,411.1
Exp/Cntr=0.3,0.1

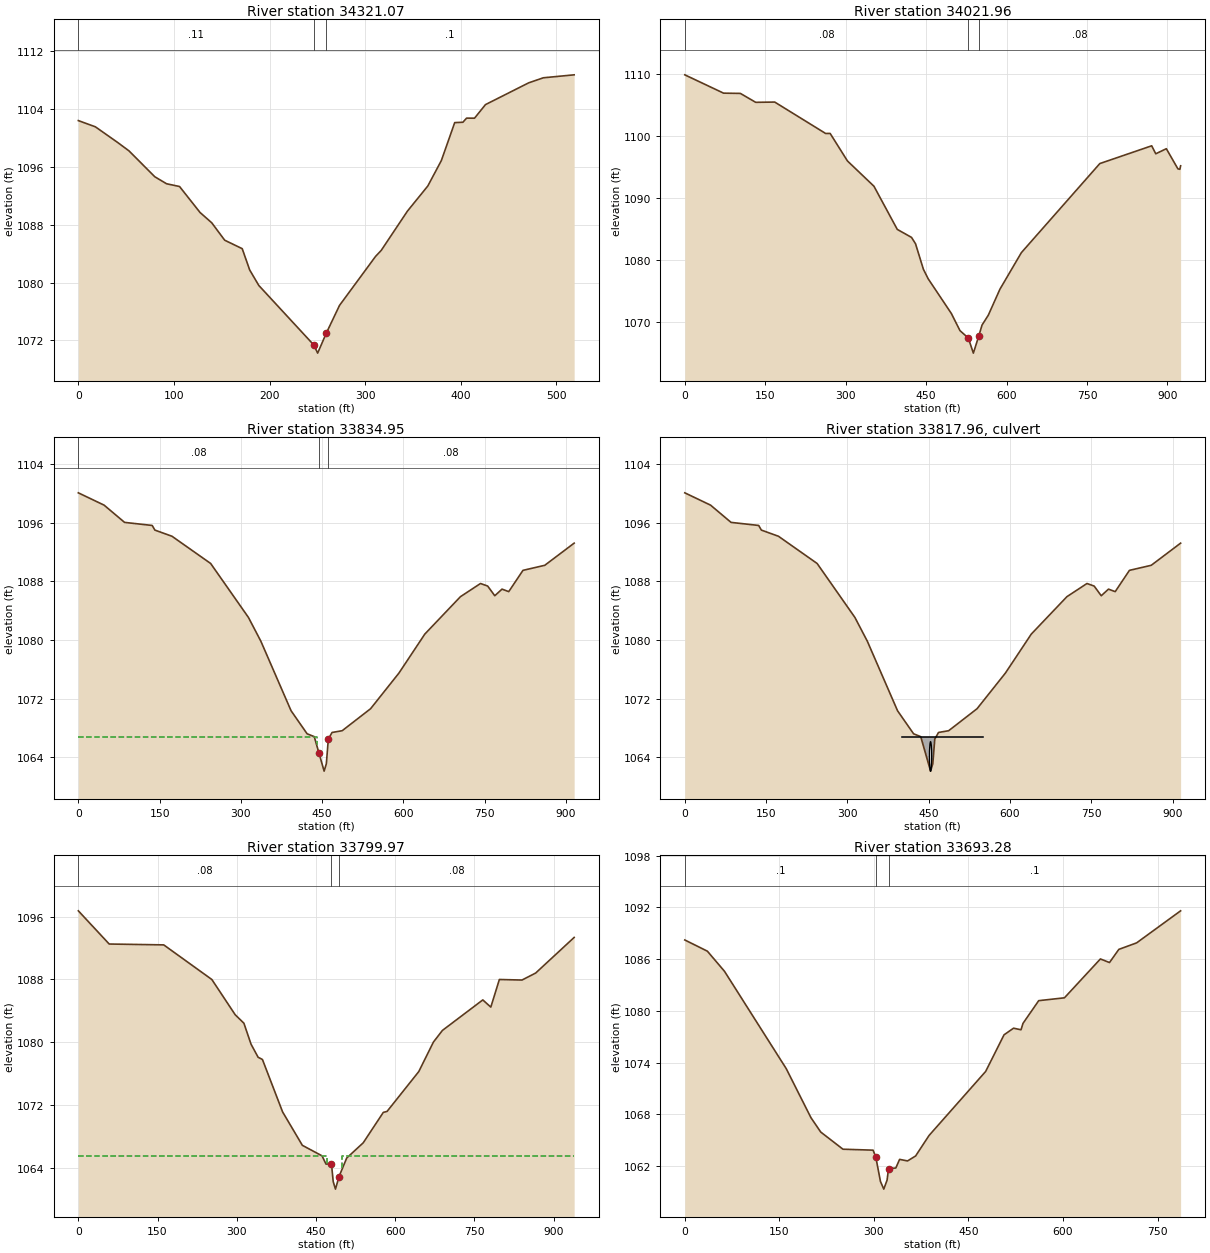
Type RM Length L Ch R = 1 ,34321.07,293.23,299.11,305.76
XS GIS Cut Line= 3
  1366610.533331   791350.222373  1366366.197873   791393.853718
  1366101.501096   791449.120076
#Sta/Elev= 30
       0  1102.4   17.81 1101.54   40.84  1099.4      53 1098.21   79.97 1094.63
    92.3 1093.66  105.86 1093.28  127.36 1089.68  139.55 1088.26   153.1 1085.85
  171.42 1084.68  179.21 1081.74  188.78 1079.59   246.2 1071.37  250.33 1070.23
  259.21 1072.95  273.18 1076.83  310.89 1083.61  316.75 1084.43   344.2 1089.87
  365.54 1093.35   379.7 1096.87  393.68 1102.12  402.26 1102.17  406.08 1102.74
   414.4 1102.73  425.86 1104.61  471.02 1107.62   486.4 1108.32  518.61 1108.73
#Mann= 3 , 0 , 0
       0     .11       0   246.2     .05       0  259.21      .1       0
Bank Sta=246.2,259.21
Exp/Cntr=0.3,0.1

Type RM Length L Ch R = 1 ,34021.96,202.77,187,170.58
XS GIS Cut Line= 4
  1366844.094365   791234.573576  1366607.834219   791106.017673
   1366208.78033    791099.62256  1365996.841487   791244.078003
#Sta/Elev= 30
       0 1109.87   72.32 1106.91  103.59 1106.87  132.24 1105.43  167.73 1105.47
   262.6  1100.4  271.01 1100.41  303.32 1095.96  352.71 1091.88  396.21 1084.91
  422.75 1083.62  430.25 1082.59  444.97 1078.46  453.73 1076.95  497.12 1071.32
  513.07 1068.57  528.63 1067.37  538.11 1064.93  548.22 1067.71  554.25 1069.46
  565.91 1071.05  587.68 1075.26  627.63 1081.16  773.88 1095.54  870.63 1098.41
  878.18 1097.12  897.93 1097.94  919.48 1094.69  923.13 1094.61  924.56 1095.18
#Mann= 3 , 0 , 0
       0     .08       0  528.63     .05       0  548.22     .08       0
Bank Sta=528.63,548.22
Exp/Cntr=0.5,0.3

Type RM Length L Ch R = 1 ,33834.95,35.14,34.98,34.83
XS GIS Cut Line= 4
  1366750.407738   791055.347019  1366637.429974   790959.934651
   1366402.10427   790892.826527  1365946.398215   791148.106282
#Sta/Elev= 30
       0 1100.06   47.58 1098.38   85.35 1096.03  136.39 1095.61  141.24 1094.98
   172.8 1094.14  244.16 1090.43  313.84 1083.08  336.82 1079.83  392.58 1070.35
  422.17 1067.21  435.36 1066.82  443.79 1064.64  453.56 1062.12  457.66 1063.13
   461.3 1066.49  468.18 1067.39  486.91 1067.63  539.31 1070.63  591.63 1075.49
  639.34  1080.8  705.07  1085.9  742.13  1087.7  755.35 1087.35  768.45 1086.03
  781.81 1086.93  794.21 1086.59  820.47 1089.49   860.7 1090.18  914.92  1093.2
#Mann= 3 , 0 , 0
       0     .08       0  443.79     .05       0   461.3     .08       0
#XS Ineff= 2 , 0
       0     440  1066.8     470       0  1066.8
Permanent Ineff=
       F       F
Bank Sta=443.79,461.3
Exp/Cntr=0.5,0.3

Type RM Length L Ch R = 2 ,33817.96,,,
BEGIN DESCRIPTION:
Driveway;  37003-0101
END DESCRIPTION:
Bridge Culvert--1,0,-1,-1, 0
Deck Dist Width WeirC Skew NumUp NumDn MinLoCord MaxHiCord MaxSubmerge Is_Ogee
8,13,2.6,0, 2, 2, , , 0.95, 0, 0,0,,
     400     550
  1066.8  1066.8
                
     400     550
  1066.8  1066.8
                
BR Coef=-1 , 0 , 0 ,, 0 ,,,0.8,-1,,0,
WSPro=,,,, 1 ,,,, 0 ,,,, 0 ,,,,-1 ,-1 ,-1 , 0 , 0 , 0 , 0 , 0
Culvert=1,4,,16,0.024,0.9,1,2,3,1062.12,453.5,1061.29,486.9,Culvert #1  , 0 ,5
Culvert Bottom n=0.024
BC Design=,, 0 ,, 0 ,,,,,,

Type RM Length L Ch R = 1 ,33799.97,96.72,106.68,116.24
XS GIS Cut Line= 4
  1366768.058862   791006.467019  1366650.845909   790914.337796
  1366412.652989   790846.412017  1365941.172611   791113.731445
#Sta/Elev= 30
       0 1096.75   58.43 1092.52  161.71 1092.41  252.79    1088     297 1083.51
  313.49 1082.43  326.99 1079.76  340.43 1078.09  348.57 1077.81  386.75 1071.13
  424.17 1066.87  461.45 1065.53  468.91 1064.48  479.29  1064.5  482.57 1062.25
  486.85 1061.29   493.6 1062.89  508.13 1065.25  539.38 1067.19  577.46 1071.07
  584.52 1071.19  644.61 1076.27  672.34 1080.03  689.33 1081.51  765.83  1085.4
  780.97 1084.48  797.18    1088  839.99 1087.93  865.85 1088.82  938.77 1093.36
#Mann= 3 , 0 , 0
       0     .08       0  479.29     .05       0   493.6     .08       0
#XS Ineff= 2 , 0
       0     470  1065.5     500       0  1065.5
Permanent Ineff=
       F       F
Bank Sta=479.29,493.6
Exp/Cntr=0.5,0.3

Type RM Length L Ch R = 1 ,33693.28,365.22,344.57,307.62
XS GIS Cut Line= 4
  1366622.544412   790854.200947  1366437.384353    790770.35486
  1366283.666535   790794.809948  1365948.282281   791060.322517
#Sta/Elev= 30
       0 1088.22   35.81 1086.92   62.95 1084.59   160.9  1073.3  200.14 1067.61
  215.68 1065.94  250.95 1063.95   298.7 1063.84  303.02 1063.05  310.43 1060.21
  315.72 1059.32  320.96 1060.37  323.27  1061.7  334.78 1061.77  340.82 1062.77
   353.4 1062.59  366.25 1063.17  387.51 1065.54  477.35 1072.97  506.53 1077.22
  521.67 1077.99  533.41  1077.8  536.62 1078.55  561.51 1081.18  602.35 1081.51
  659.41 1086.02   673.8  1085.6  688.65 1087.13  716.79 1087.88  786.67  1091.6
#Mann= 3 , 0 , 0
       0      .1       0  303.02     .05       0  323.27      .1       0
Bank Sta=303.02,323.27
Exp/Cntr=0.5,0.3