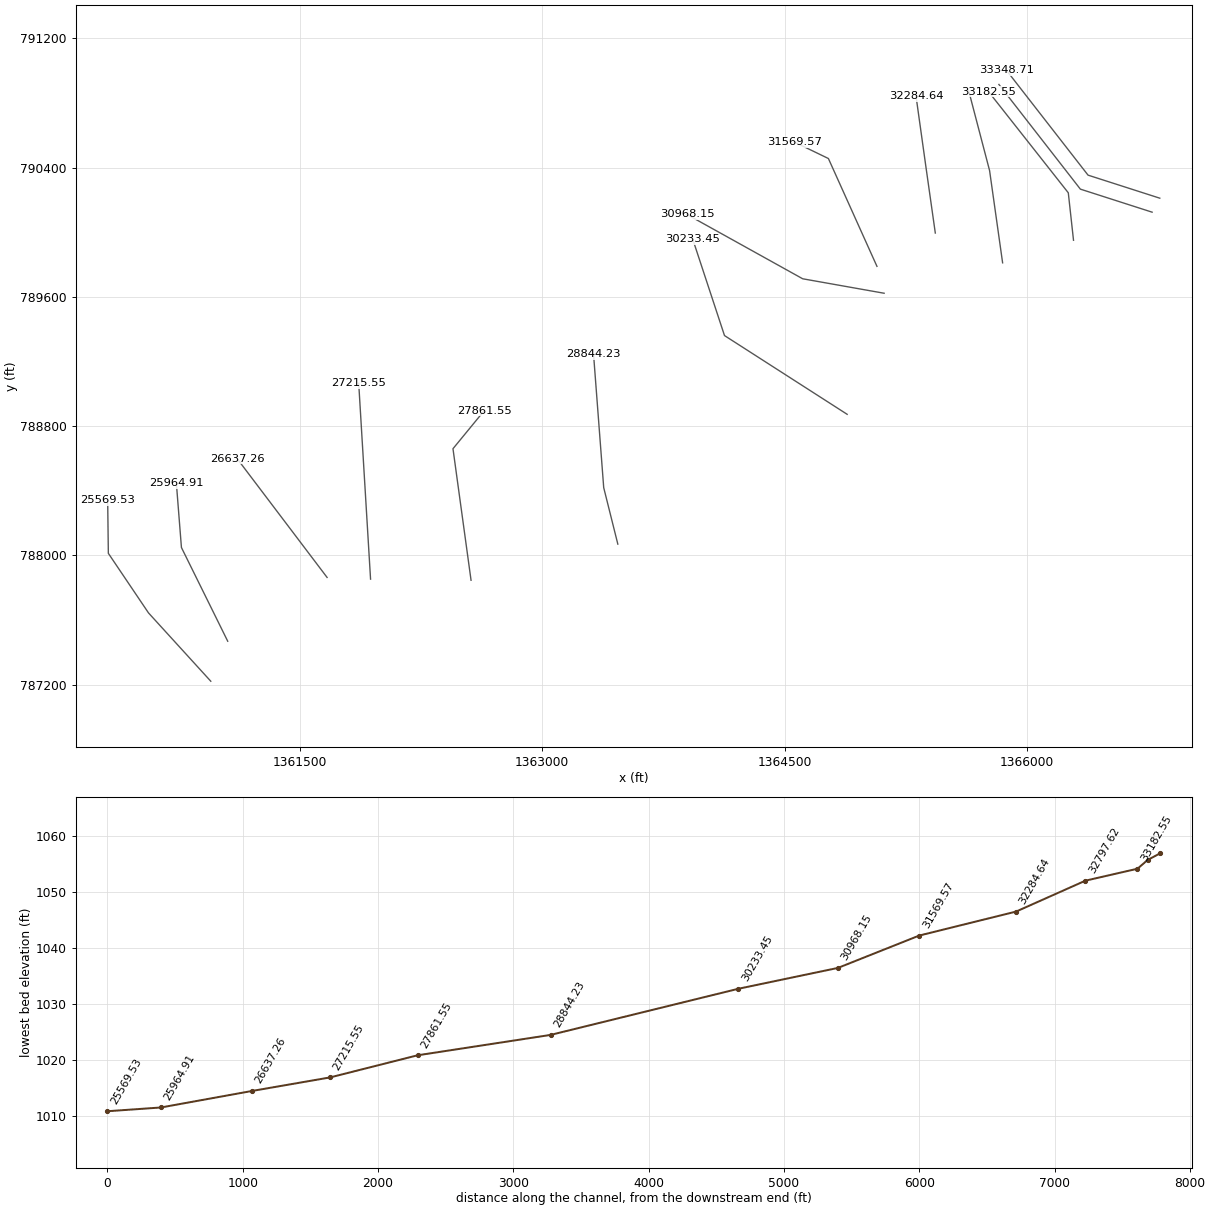
HEC-RAS study GladeCreek.prj: Glade Creek

--- GladeCreek.g01 (geometry) --- (continued)

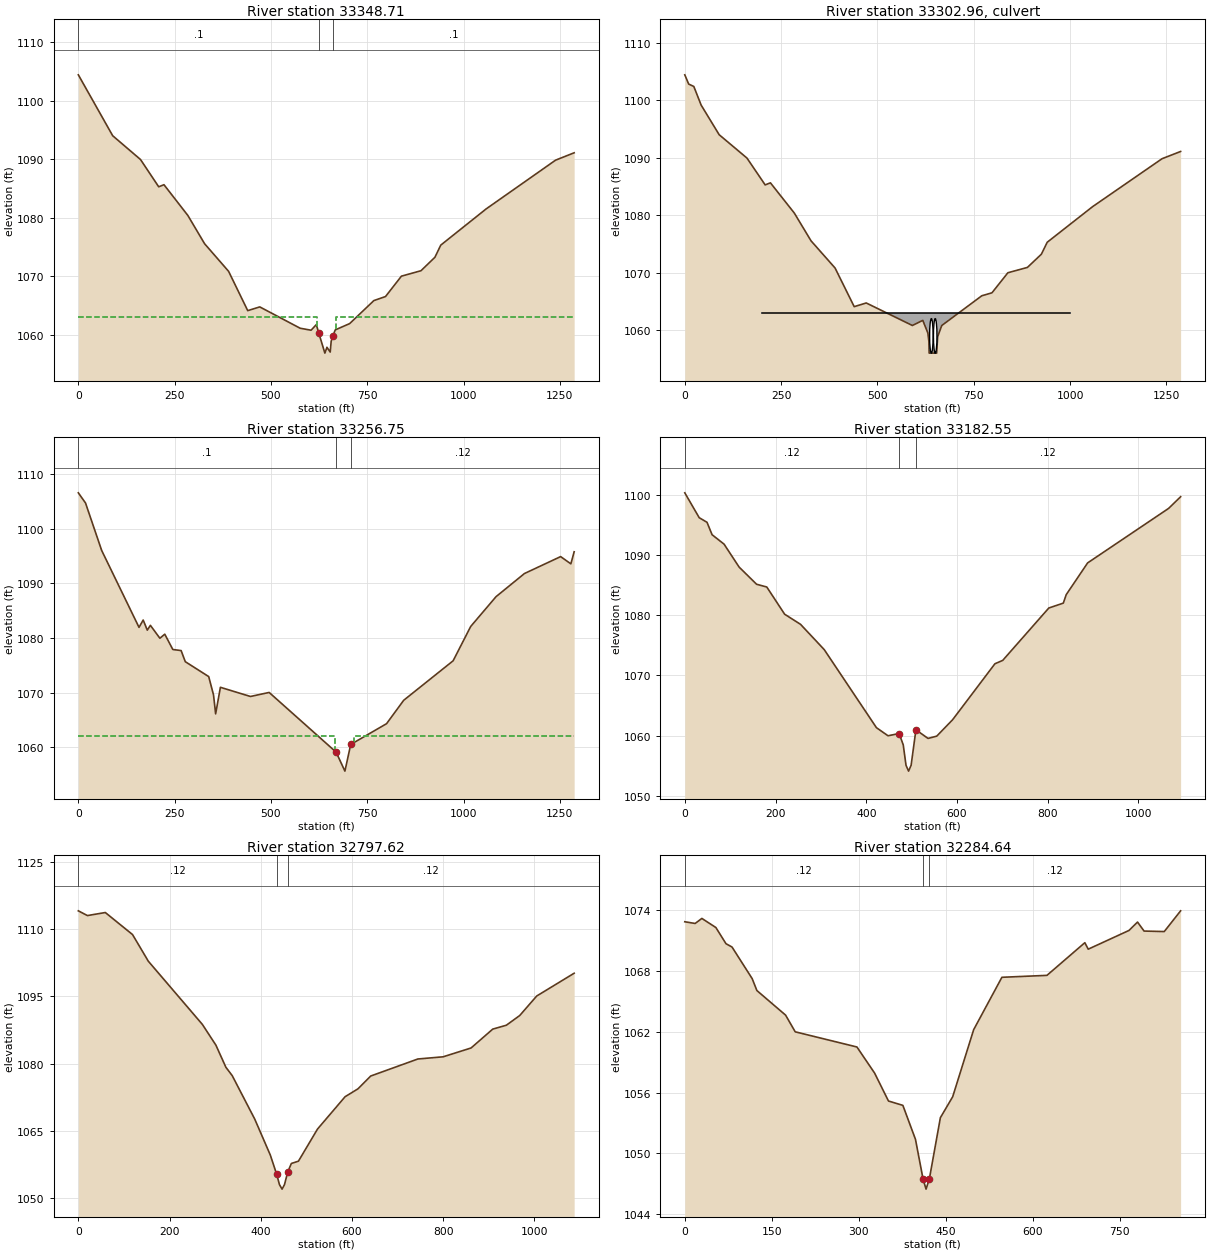
Type RM Length L Ch R = 1 ,33348.71,91.9,91.96,91.81
XS GIS Cut Line= 3
  1366821.691028   790210.470224  1366377.697938   790353.036851
  1365873.623226   791000.696498
#Sta/Elev= 30
       0 1104.44   89.18 1094.02  161.39 1089.95  208.64 1085.28  222.28 1085.64
  284.28 1080.38  327.76 1075.54  390.02 1070.82  439.72 1064.09  470.96 1064.73
  575.81 1061.08  604.14 1060.74  617.75  1061.7  623.93  1060.3  639.97 1056.82
  645.36 1057.82  653.78    1057  656.32 1058.84   660.2  1059.7  666.97  1060.8
  704.25 1061.87   767.1 1065.81  797.33  1066.5  838.64 1069.99  889.42 1070.92
  925.59 1073.22  940.78  1075.3 1058.45 1081.49 1238.85 1089.84 1287.02  1091.1
#Mann= 3 , 0 , 0
       0      .1       0  623.93     .05       0   660.2      .1       0
#XS Ineff= 2 , 0
       0     620    1063     670       0    1063
Permanent Ineff=
       F       F
Bank Sta=623.93,660.2
Exp/Cntr=0.5,0.3

Type RM Length L Ch R = 2 ,33302.96,,,
BEGIN DESCRIPTION:
Boston Road, SR 1604; 37003-0045
This is an ellipse CMP.
END DESCRIPTION:
Bridge Culvert--1,0,-1,-1, 0
Deck Dist Width WeirC Skew NumUp NumDn MinLoCord MaxHiCord MaxSubmerge Is_Ogee
22,38,2.6,0, 2, 2, , , 0.95, 0, 0,0,,
     200    1000
    1063    1063
                
     200    1000
    1063    1063
                
BR Coef=-1 , 0 , 0 ,, 0 ,,,0.8,-1,,0,
WSPro=,,,, 1 ,,,, 0 ,,,, 0 ,,,,-1 ,-1 ,-1 , 0 , 0 , 0 , 0 , 0
Multiple Barrel Culv=4,6,9,48,0.024,0.5,1,29,1,1056,1055.64, 2,Culvert #1  , 0 ,18
     640     687     650     697
Culvert Bottom n=0.024024
BR U #Sta/Elev= 30
       0 1104.44    10.1 1102.83   23.36 1102.42   42.46 1099.17   89.18 1094.02
  161.39 1089.95  208.64 1085.28  222.28 1085.64  284.28 1080.38  327.76 1075.54
  390.02 1070.82  439.72 1064.09  470.96 1064.73  590.75 1060.81  617.75  1061.7
   630.9  1059.5   633.6 1058.04   634.3    1056  653.78    1056  656.32 1058.84
  666.97  1060.8  770.84 1065.98  797.33  1066.5  838.64 1069.99  889.42 1070.92
  925.59 1073.22  940.78  1075.3 1058.45 1081.49 1238.85 1089.84 1287.02  1091.1
BR U #Mann= 3
       0      .1   633.6    .045  656.32      .1
BR U Banks=,656.32
BR D #Sta/Elev= 183
       0 1106.57    8.36 1105.86    9.75 1105.73    13.1 1105.38   17.06 1104.95
   18.66 1104.71   31.54 1102.39   43.66 1100.11   47.66 1099.21    54.3 1097.54
   60.57 1096.03   81.22 1093.34   83.21 1093.09    84.6 1092.87   94.08 1092.02
   98.44 1091.48  106.73    1090  115.67 1088.44  118.11 1087.97  125.48 1086.48
  127.33 1086.24  129.96 1085.78   141.8 1084.48  150.58 1083.41  152.87 1083.39
  157.52 1081.95  159.22 1081.93  160.17 1081.94  168.35 1083.29  173.84 1082.09
  178.99 1081.44  187.03 1082.32  189.36 1082.12  194.31 1081.41  200.82 1081.76
  204.92 1081.22  211.68 1079.96  221.28  1080.8  221.68 1080.73  222.33 1080.75
  224.42  1080.7   230.2 1080.16  232.48 1080.04  234.43 1079.91  245.26  1077.9
  256.92 1078.47  257.04 1078.45  257.17 1078.45  265.33 1077.74  266.84  1077.7
  277.62 1075.67  286.95 1075.95  290.17 1075.48   293.5 1075.47  298.19 1074.88
  301.64 1074.95  307.75 1074.56  314.07 1074.07  322.16 1072.94  329.62 1073.03
  332.28 1072.83  336.72 1073.06  338.44 1072.94  350.91 1069.59  356.42 1066.12
  359.06 1067.64  365.04 1070.37  368.77 1070.98  371.28  1070.9  380.55 1070.58
  386.81 1070.85  402.21 1071.18  402.44 1071.17  402.75 1071.16  418.44 1070.46
  424.69 1070.03   438.8 1069.38  446.79  1069.3  450.29 1069.39  458.42 1070.06
  465.45 1070.41  466.32 1070.47   475.3 1070.44  495.33 1070.04  523.79 1068.36
  527.85 1068.18  531.94 1068.12  540.78 1067.81  545.13 1067.65  553.87 1066.76
   558.4 1066.49  566.96 1065.88  571.94 1065.39   580.1 1064.98  585.04 1064.76
  593.14 1063.97   598.2 1063.76   603.5 1063.39  611.34 1062.57  617.02 1062.21
  624.56 1061.93  632.58 1061.26  638.99    1061  643.71 1060.84  647.09 1060.67
   652.6 1061.06  659.52  1059.9  669.08 1059.12  674.87 1057.65  681.48 1055.64
  686.43 1055.64  687.43 1055.64     692 1055.64  693.16 1055.64  697.56 1055.64
     702 1055.64  705.25 1059.57  707.03 1060.52  712.68 1060.31  734.93 1061.68
  735.07 1061.67  735.23 1061.68  735.76 1061.71  771.14 1063.45  784.58 1063.44
  785.84 1063.52  800.03 1064.32  809.71 1064.94  815.44 1065.67  816.85 1065.89
  825.39 1066.59  831.84 1066.97  838.96 1067.91  844.64 1068.61  857.62 1069.27
  862.06 1069.53  865.45 1069.74  877.29 1070.55  878.83 1070.55   880.1 1070.74
  903.59 1071.92  916.09 1072.47  917.99 1072.62  923.25 1072.97   935.5 1073.95
  939.79 1074.04  959.77 1075.29  962.57 1075.43  972.86 1075.83  977.53 1076.53
  988.05 1078.31  995.26 1078.16 1007.26 1079.96 1018.44 1082.11 1023.05 1082.59
 1026.57  1082.8 1049.11 1084.07 1060.09 1084.98 1084.16 1087.56 1085.04 1087.58
 1094.53 1088.16 1111.71 1088.94 1112.57 1089.08 1116.29 1089.31 1134.32 1090.33
 1138.12 1090.77 1143.19 1091.12 1157.96  1091.8 1166.52 1092.09 1174.82 1092.34
 1176.88 1092.31 1186.54 1092.59 1198.63 1093.06 1200.89 1093.08 1216.07 1093.41
 1219.96 1093.51 1249.21 1094.76 1251.97  1094.9  1263.6 1094.31 1273.56  1093.9
 1278.46 1093.57  1281.6 1094.51 1287.02 1095.78
BR D #Mann= 3
       0      .1  674.87    .045  705.25      .1
BR D Banks=674.87,705.25
BC Design=,, 0 ,, 0 ,,,,,,

Type RM Length L Ch R = 1 ,33256.75,74,74.19,74.39
XS GIS Cut Line= 3
   1366774.16885    790123.91194   1366330.17576    790266.47852
  1365826.101001   790914.138214
#Sta/Elev= 30
       0 1106.57   18.66 1104.71   60.57 1096.03  157.52 1081.95  168.35 1083.29
  178.99 1081.44  187.03 1082.32  211.68 1079.96  224.42  1080.7  245.26  1077.9
  266.84  1077.7  277.62 1075.67  338.44 1072.94  350.91 1069.59  356.42 1066.12
  368.77 1070.98  446.79  1069.3  495.33 1070.04  669.08 1059.12     692 1055.64
  707.03 1060.52  800.03 1064.32  844.64 1068.61  972.86 1075.83 1018.44 1082.11
 1084.16 1087.56 1157.96  1091.8 1251.97  1094.9 1278.46 1093.57 1287.02 1095.78
#Mann= 3 , 0 , 0
       0      .1       0  669.08     .05       0  707.03     .12       0
#XS Ineff= 2 , 0
       0     665    1062     715       0    1062
Permanent Ineff=
       F       F
Bank Sta=669.08,707.03
Exp/Cntr=0.5,0.3

Type RM Length L Ch R = 1 ,33182.55,400.76,384.94,369.04
XS GIS Cut Line= 3
  1366287.745215   789950.116483  1366255.498032   790243.735762
  1365761.606587   790870.010427
#Sta/Elev= 30
       0 1100.39   31.79 1096.25   48.94 1095.49   60.16 1093.42   86.58 1091.85
  119.82 1088.03  158.22 1085.18  180.74 1084.72  220.06  1080.2  255.16 1078.51
  307.32 1074.31  422.44 1061.32  448.01 1059.97  472.45 1060.35  481.54 1058.46
  487.65 1055.06   493.3 1054.09   498.9 1055.07  509.49 1060.97  536.17 1059.53
  555.36 1059.91  590.35 1062.64   683.6 1071.95  700.91 1072.52  802.46 1081.23
   834.4 1082.04   840.8 1083.45  887.97 1088.73 1066.53  1097.8 1092.97 1099.74
#Mann= 3 , 0 , 0
       0     .12       0  472.45     .05       0  509.49     .12       0
Bank Sta=472.45,509.49
Exp/Cntr=0.3,0.1

Type RM Length L Ch R = 1 ,32797.62,500,512.98,523
XS GIS Cut Line= 3
  1365849.013492    789810.52003  1365768.395509   790381.210709
   1365638.98237   790875.526418
#Sta/Elev= 30
       0 1114.09   19.98 1113.03   59.19 1113.71  118.89 1108.79  153.42 1102.85
  272.05 1088.73  301.67 1084.11  323.64 1079.16  337.52 1077.29  386.93 1067.58
  421.13 1059.54  434.95 1055.27  441.09 1052.96  446.77 1051.96  452.06 1052.96
  459.39 1055.85  467.19 1057.69  482.68  1058.2  524.59 1065.38     585 1072.59
  613.21 1074.35  641.21 1077.21   744.5 1081.01  799.97  1081.5  861.27 1083.47
  908.75 1087.68  938.63 1088.55  967.99 1090.72 1005.17 1095.07 1087.33 1100.16
#Mann= 3 , 0 , 0
       0     .12       0  434.95     .05       0  459.39     .12       0
Bank Sta=434.95,459.39
Exp/Cntr=0.3,0.1

Type RM Length L Ch R = 1 ,32284.64,700.8,715.06,721.21
XS GIS Cut Line= 3
  1365432.487293   789994.742248  1365374.312182   790404.876827
  1365313.228318   790841.190138
#Sta/Elev= 30
       0 1072.88   17.86 1072.71   29.41 1073.21   53.57 1072.31   71.02 1070.71
   81.42 1070.38  116.15 1067.26  124.27 1066.08  173.78 1063.65  190.39    1062
  296.77  1060.5  327.24 1057.92  351.15 1055.16  375.96 1054.73  397.71 1051.37
  410.76 1047.45  415.89 1046.45  421.61 1047.45  440.62 1053.51  461.84 1055.58
     498 1062.21   546.7 1067.39  624.36 1067.58  689.68 1070.81  695.53 1070.17
  765.77 1072.02  780.52 1072.85  791.78 1071.96  826.59 1071.91  854.81 1073.96
#Mann= 3 , 0 , 0
       0     .12       0  410.76     .05       0  421.61     .12       0
Bank Sta=410.76,421.61
Exp/Cntr=0.3,0.1

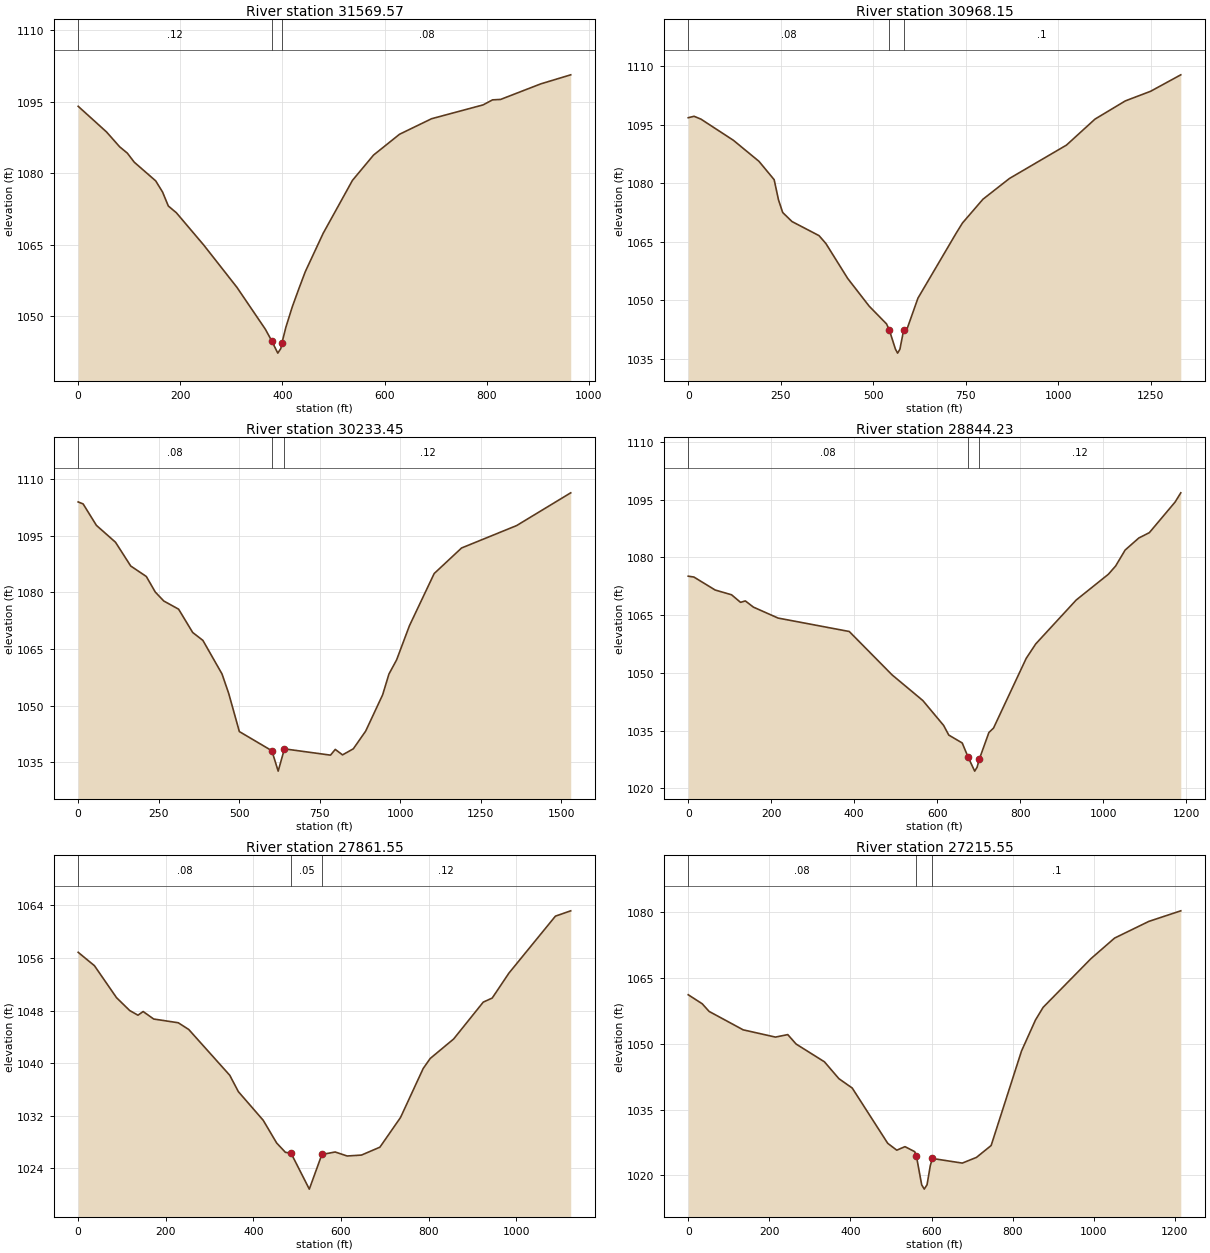
Type RM Length L Ch R = 1 ,31569.57,579.79,601.42,619
XS GIS Cut Line= 3
   1365071.39211   789788.657139  1364770.943722   790455.932117
  1364561.328528    790557.24609
#Sta/Elev= 30
       0 1094.05   55.54 1088.66    81.4 1085.52   96.19 1084.22  109.87  1082.3
  151.91 1078.37  165.34 1076.02  176.55  1073.1  192.28 1071.68  245.78 1064.91
  311.02 1055.99  366.55 1047.21  378.98 1044.77  390.98 1042.18  396.95 1043.16
  399.09 1044.35  406.86 1047.65  419.51 1051.97  432.16  1055.7  444.74 1059.28
  479.73 1067.34  537.22 1078.49   578.4 1083.79  629.33 1088.17  692.23 1091.44
  792.94 1094.34  811.52  1095.4  827.32 1095.49     906 1098.76  964.61 1100.66
#Mann= 3 , 0 , 0
       0     .12       0  378.98     .05       0  399.09     .08       0
Bank Sta=378.98,399.09
Exp/Cntr=0.3,0.1

Type RM Length L Ch R = 1 ,30968.15,724.16,734.7,714.58
XS GIS Cut Line= 3
  1365115.760876   789622.234545  1364611.898273   789711.736461
  1363895.883041    790109.52268
#Sta/Elev= 30
       0 1096.75   15.82 1097.11   34.44 1096.38  122.05 1090.96  191.11 1085.57
  232.15 1080.87  243.86  1075.7  255.19 1072.46  280.29 1070.14  353.48 1066.52
  371.89 1064.51  430.87 1055.55  488.98 1048.44  535.78  1043.9     543 1042.42
  559.94 1037.41  565.75 1036.41  571.93  1037.4  581.88 1042.25  591.77 1042.76
  620.72 1050.51  723.86 1067.14  740.86 1069.75  796.23 1075.85  867.99 1081.18
 1021.99 1089.73 1099.04 1096.39 1181.05 1101.06 1249.29 1103.52 1330.84 1107.74
#Mann= 3 , 0 , 0
       0     .08       0     543     .05       0  581.88      .1       0
Bank Sta=543,581.88
Exp/Cntr=0.3,0.1

Type RM Length L Ch R = 1 ,30233.45,1410.33,1389.22,1358.78
XS GIS Cut Line= 4
  1364887.033779   788873.070423  1364127.924995   789360.358604
  1363938.976548   789933.833752  1363932.346788   789957.037979
#Sta/Elev= 30
       0 1103.94   15.39 1103.41   56.68 1097.74  116.02 1093.27  163.29 1086.98
  211.72 1084.21  239.56 1080.09  265.96 1077.72  311.99 1075.56  355.74 1069.39
  387.41  1067.3  446.81 1058.42   467.7 1053.24  500.67 1043.17  601.72 1038.09
  621.29  1032.7  640.71 1038.59  783.76 1036.93  798.63 1038.45  821.15    1037
  854.63  1038.6  893.11  1043.3  945.73 1052.89  965.32 1058.39  989.14 1062.14
 1029.12  1071.2 1105.87 1084.99 1190.88 1091.75  1361.9 1097.68 1529.98 1106.35
#Mann= 3 , 0 , 0
       0     .08       0  601.72     .05       0  640.71     .12       0
Bank Sta=601.72,640.71
Exp/Cntr=0.3,0.1

Type RM Length L Ch R = 1 ,28844.23,979.94,982.68,984.24
XS GIS Cut Line= 3
  1363467.836056    788069.81271  1363380.496392   788419.171366
  1363317.611862   789243.657692
#Sta/Elev= 30
       0 1075.12   13.63  1074.9   64.85 1071.53  104.43 1070.29   126.1 1068.32
  137.57  1068.7  157.11 1067.08  216.47 1064.24  388.05 1060.75  491.23 1049.48
  565.47  1042.8  615.51 1036.34  627.84 1033.84  660.21 1031.79  674.85 1028.02
  690.33 1024.47  696.11 1025.47  701.27 1027.52   724.6 1034.51  735.68 1035.65
  814.47 1053.77  837.41 1057.52  934.97 1068.93 1012.68 1075.64 1029.91 1077.76
 1052.94 1081.92 1085.84 1085.04 1111.22 1086.43 1173.25 1094.38 1186.99 1096.78
#Mann= 3 , 0 , 0
       0     .08       0  674.85     .05       0  701.27     .12       0
Bank Sta=674.85,701.27
Exp/Cntr=0.3,0.1

Type RM Length L Ch R = 1 ,27861.55,646.35,646,642.24
XS GIS Cut Line= 3
  1362559.503644   787846.223208  1362447.708892   788660.228802
  1362639.856107   788894.299083
#Sta/Elev= 30
       0 1056.87   37.19 1054.83   87.54 1049.97  117.67 1048.01  136.57  1047.3
  148.36 1047.86  172.39 1046.72  228.51 1046.15  252.41 1045.13  346.09 1038.16
  365.73 1035.67  422.51 1031.31  453.11 1027.86  473.24 1026.43  485.83 1026.33
   527.7 1020.84  556.38 1026.11  586.72 1026.49   614.1 1025.88  646.78 1026.02
  688.83 1027.22  735.96 1031.74  787.65 1039.19   803.6 1040.71  857.17 1043.68
  924.79 1049.29  945.25 1049.91  983.49 1053.71 1089.55 1062.37 1124.48 1063.18
#Mann= 3 , 0 , 0
       0     .08       0  485.83     .05       0  556.38     .12       0
Bank Sta=485.83,556.38
Exp/Cntr=0.3,0.1

Type RM Length L Ch R = 1 ,27215.55,560.05,578.28,594
XS GIS Cut Line= 2
   1361937.64531   787853.210362  1361864.280002   789065.484787
#Sta/Elev= 30
       0 1061.11   34.46 1059.06    51.5 1057.32  135.48 1053.13  215.09 1051.48
  245.37 1052.05     266  1049.9  335.83 1045.86  371.54 1042.02   404.4 1039.89
  491.89 1027.32  514.23 1025.76  534.42 1026.56   558.5 1025.42  562.47 1024.48
  575.61 1017.89  581.93  1016.9  588.85  1017.9  596.96  1022.3  602.15 1023.87
  675.77 1022.82  710.74 1024.12  746.87 1026.82  821.73 1048.31  856.09 1055.35
  875.09 1058.25  992.85 1069.31 1051.28    1074 1135.56 1077.79 1214.49  1080.2
#Mann= 3 , 0 , 0
       0     .08       0  562.47     .05       0  602.15      .1       0
Bank Sta=562.47,602.15
Exp/Cntr=0.3,0.1

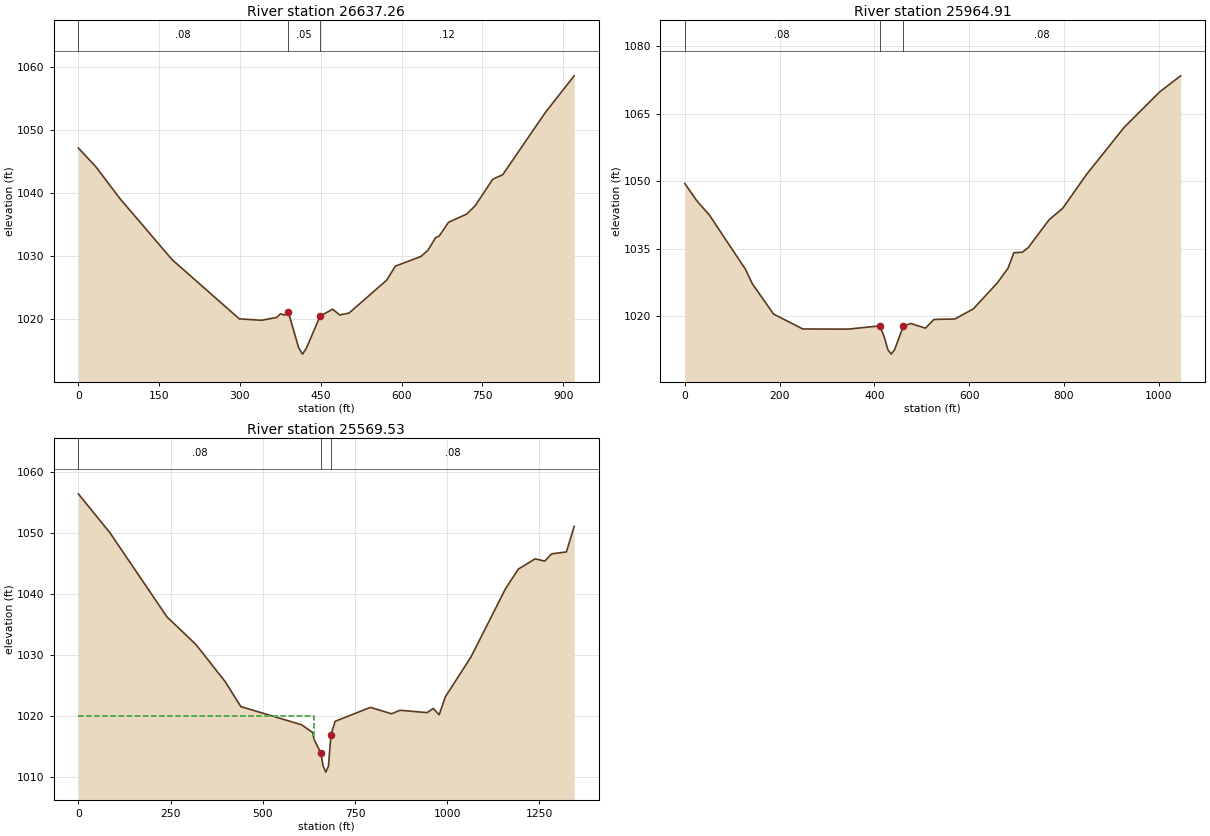
Type RM Length L Ch R = 1 ,26637.26,676.13,672.36,665.98
XS GIS Cut Line= 2
  1361668.639164    787863.69114  1361113.158938   788597.344225
#Sta/Elev= 30
       0 1047.14   32.51 1044.17   76.58 1039.19  173.98 1029.45  298.78 1020.07
  340.15 1019.84  368.01 1020.29  375.28 1020.88  382.79 1020.65  389.51 1021.21
     409 1015.47  416.15 1014.48  423.52 1015.48  448.81 1020.51  471.99  1021.6
  484.95 1020.69  502.34 1020.98  572.42 1026.21  588.42 1028.42  635.65 1029.95
  648.62  1030.9  663.08 1032.94  669.94 1033.21  686.98 1035.36  720.99 1036.68
  736.42 1037.97  769.04 1042.18  787.78 1042.92  866.88 1052.78  920.22 1058.57
#Mann= 3 , 0 , 0
       0     .08       0  389.51     .05       0  448.81     .12       0
Bank Sta=389.51,448.81
Exp/Cntr=0.3,0.1

Type RM Length L Ch R = 1 ,25964.91,390.06,395.38,397.16
XS GIS Cut Line= 3
  1361053.767985   787468.915887  1360767.293906     788048.8512
  1360735.851664   788447.120031
#Sta/Elev= 30
       0  1049.5   26.28 1045.54   51.72 1042.51   128.1 1030.41   142.7 1027.17
  187.22 1020.47  248.82 1017.14  344.09  1017.1  411.56 1017.82   421.1 1015.31
  428.54 1012.54  435.72 1011.54  442.82 1012.55  461.26 1017.79  476.99 1018.35
  507.71 1017.32  525.94 1019.26  569.88 1019.36  608.64 1021.59  659.32 1027.36
  682.26 1030.68  694.42  1034.1  712.59 1034.22  724.75 1035.24  768.95 1041.46
  797.56 1043.99  847.58 1051.49  927.43 1062.02 1002.73 1069.94 1046.34 1073.46
#Mann= 3 , 0 , 0
       0     .08       0  411.56     .05       0  461.26     .08       0
Bank Sta=411.56,461.26
Exp/Cntr=0.5,0.3

Type RM Length L Ch R = 1 ,25569.53,134.82,135.58,137.05
XS GIS Cut Line= 4
  1360948.949911   787221.428787  1360563.594473   787644.076662
  1360314.978051   788012.857678  1360310.834458   788340.202616
#Sta/Elev= 30
       0 1056.46   85.37 1050.11  240.35  1036.3  318.75 1031.78  398.36 1025.67
  440.48 1021.61  605.57 1018.62  635.49 1017.34  638.83 1016.28  657.57 1013.95
  663.54 1011.88  670.82 1010.87  678.07 1011.86  684.81 1016.97  696.01 1019.19
  791.66 1021.48  848.95 1020.43  871.71    1021  945.43 1020.62     962  1021.3
   978.2 1020.27  995.13 1023.23 1064.51 1029.75 1158.41 1040.96 1192.63 1044.12
 1238.22 1045.81  1264.5 1045.44 1282.77 1046.63 1323.07 1046.94 1344.08 1051.12
#Mann= 3 , 0 , 0
       0     .08       0  657.57     .05       0  684.81     .08       0
#XS Ineff= 2 , 0
       0     640    1020     700       0  1019.2
Permanent Ineff=
       F       F
Bank Sta=657.57,684.81
Exp/Cntr=0.5,0.3