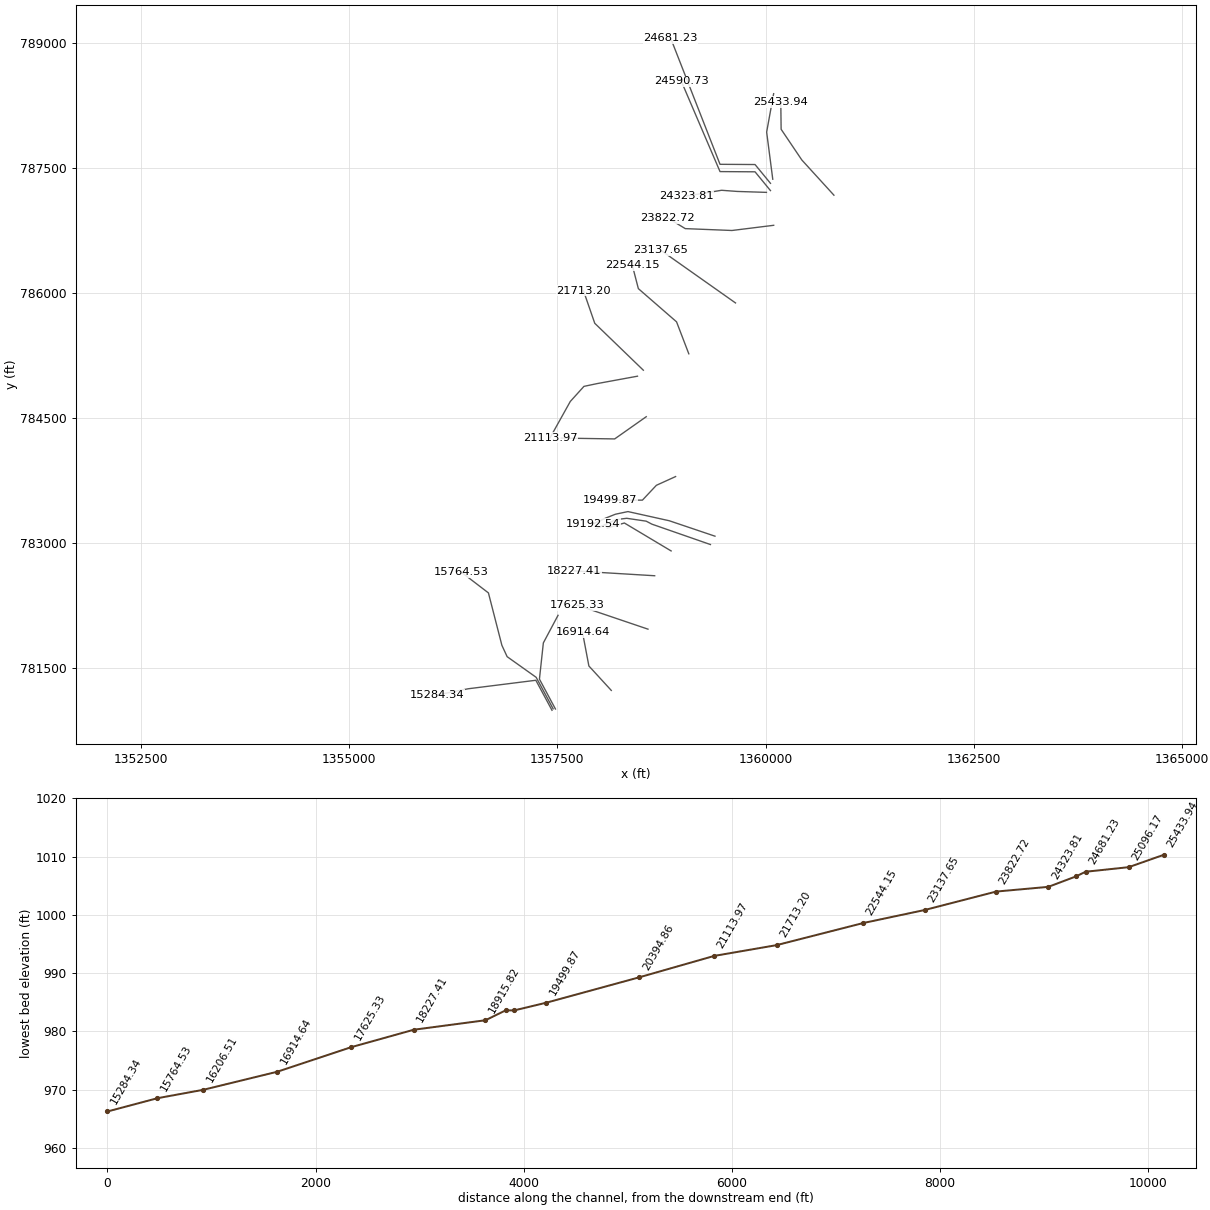
HEC-RAS study GladeCreek.prj: Glade Creek

--- GladeCreek.g01 (geometry) --- (continued)

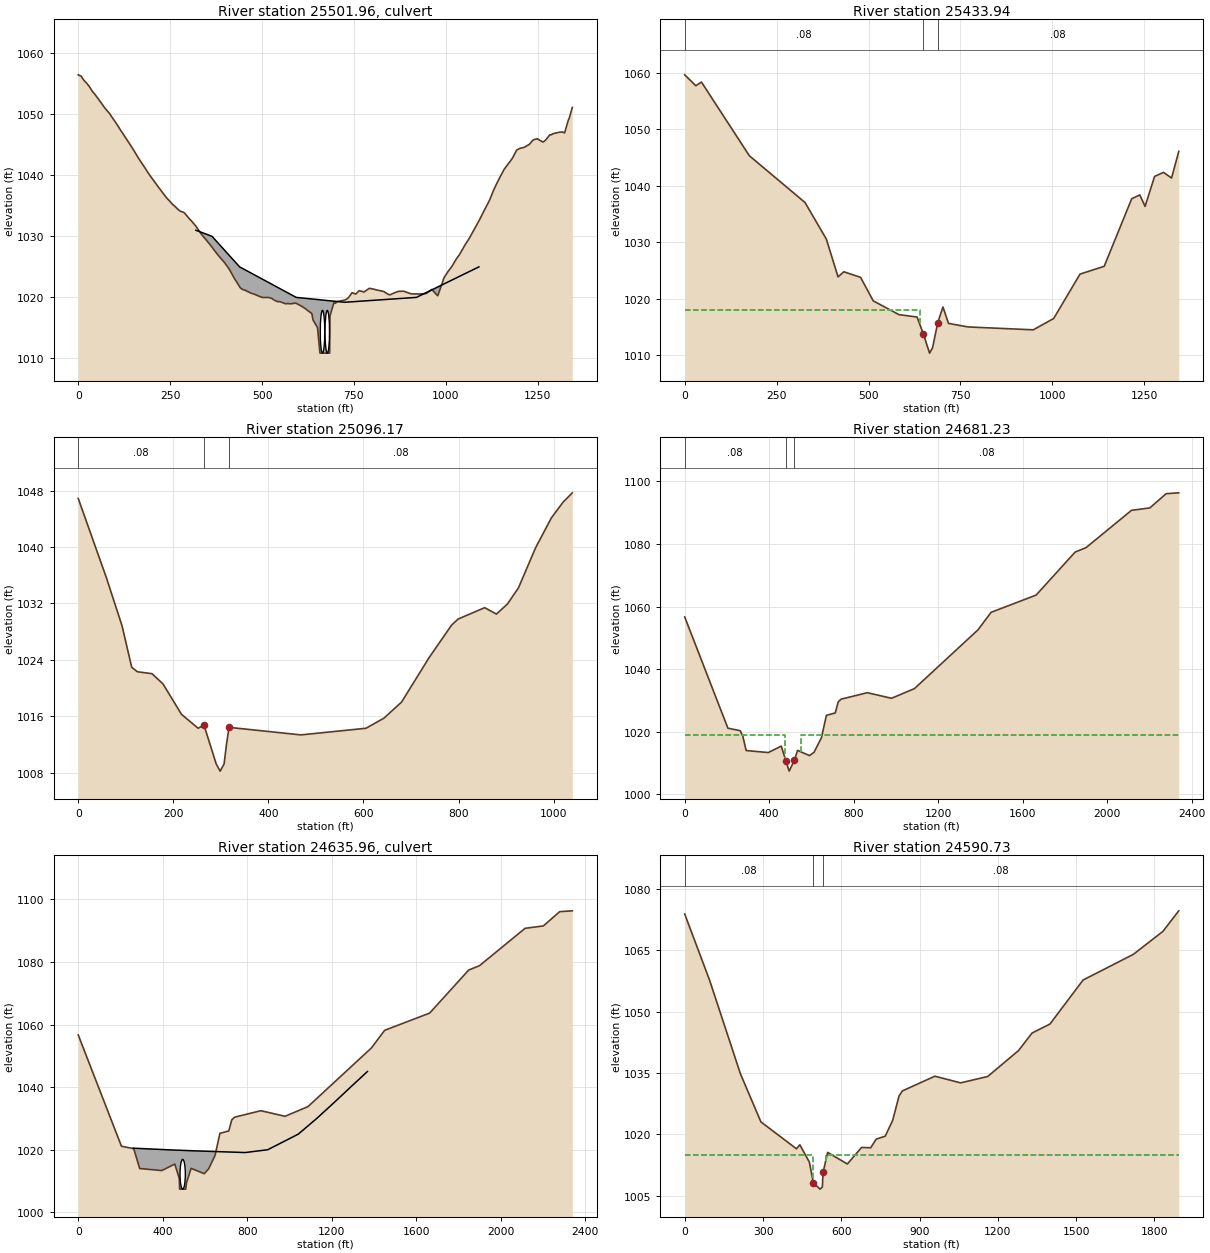
Type RM Length L Ch R = 2 ,25501.96,,,
BEGIN DESCRIPTION:
Paul Payne Store Road; SR 1605; 37003-0049
END DESCRIPTION:
Bridge Culvert--1,0,-1,-1, 0
Deck Dist Width WeirC Skew NumUp NumDn MinLoCord MaxHiCord MaxSubmerge Is_Ogee
48,30,2.6,0, 7, 7, , , 0.95, 0, 0,0,,
     320     364     439     593     725     920    1090
    1031    1030    1025    1020  1019.2    1020    1025
                                                        
     320     364     439     593     725     920    1090
    1031    1030    1025    1020  1019.2    1020    1025
                                                        
BR Coef=-1 , 0 , 0 ,, 0 ,,,0.8,-1,,0,
WSPro=,,,, 1 ,,,, 0 ,,,, 0 ,,,,-1 ,-1 ,-1 , 0 , 0 , 0 , 0 , 0
Multiple Barrel Culv=4,7,12,45,0.024,0.5,1,29,1,1010.87,1010.33, 2,Culvert #1  , 0 ,39
   664.5   659.5   677.5   672.5
Culvert Bottom n=0.024
BR U #Sta/Elev= 181
       0 1056.46     .47 1056.42    7.45 1056.28   15.43 1055.57   23.12 1055.09
   30.39 1054.51   38.69 1053.73    45.1 1053.28   54.36 1052.54   69.82 1051.23
   74.95 1050.84   85.37 1050.11   89.75  1049.7  100.97 1048.75  104.62 1048.41
  116.64 1047.25   119.6    1047  132.17 1045.85  134.44 1045.63  147.69 1044.41
  149.25 1044.28  163.31 1042.86  164.15 1042.78  178.96 1041.46  179.08 1041.44
  181.47 1041.22   193.1 1040.13  194.23 1040.04  220.99 1037.84  235.04 1036.74
  240.35  1036.3  248.99 1035.76  255.91 1035.29  263.26  1034.9  271.58 1034.41
  277.43 1034.13   287.2 1033.92  291.64 1033.65  302.87 1032.83  305.91 1032.67
  318.75 1031.78  320.38 1031.65  334.61 1030.38  334.85 1030.36  349.94  1029.3
  350.57 1029.23  365.09 1028.15  366.45    1028  380.19 1026.94  395.47 1025.88
  398.36 1025.67  410.37 1024.66  414.04 1024.28  425.38 1023.03  429.74 1022.65
  440.48 1021.61  445.69 1021.33  455.79 1021.12  461.77 1020.93  470.98 1020.67
  477.89 1020.55  493.97 1020.14  501.56 1019.98  516.98 1019.99  526.44 1019.84
  532.13 1019.59  542.52 1019.29  547.45 1019.31  558.58 1019.09  562.55 1018.97
  571.95 1018.99  574.75 1018.98  577.09 1018.94  591.03 1019.06   594.3 1018.99
  605.57 1018.62  617.63 1018.17  619.93 1018.05  635.49 1017.34  638.83 1016.28
  650.91 1015.06  657.57 1010.87  663.54 1010.87  669.63 1010.87  670.82 1010.87
  671.65 1010.87  678.07 1010.87     684 1010.87  684.81 1016.97  696.01 1019.19
  699.72 1019.04   704.9 1019.31  726.49 1019.59  733.48 1019.86  735.51 1019.99
  744.78 1020.77  754.88 1020.54  760.33 1020.86  764.25  1021.1  775.65 1020.92
  776.89 1020.87  790.62 1021.44  791.26 1021.47  791.66 1021.48  803.64 1021.36
  811.54 1021.22  829.69    1021  831.11 1020.97  843.79 1020.48  848.95 1020.43
  857.76 1020.69  871.71    1021  884.47 1021.02  885.61 1021.01  889.79 1020.92
  899.76 1020.69   905.2 1020.59  914.43 1020.56  927.76 1020.57  929.08 1020.56
  931.56 1020.56  945.43 1020.62  950.55 1020.81     962  1021.3     973 1020.56
   978.2 1020.27  991.75 1022.62  994.06 1023.04  995.13 1023.23 1006.21 1024.26
 1012.66 1024.76 1016.71 1025.11 1017.81  1025.2 1020.84 1025.53 1029.86 1026.42
 1036.71 1026.97 1041.53 1027.48 1047.27 1028.11 1051.98 1028.57 1064.26 1029.73
 1064.51 1029.75 1074.43 1030.83 1079.07 1031.31 1091.26 1032.67 1094.53 1033.07
 1102.67 1034.03 1103.15 1034.09 1117.62 1035.74 1119.06 1035.93 1127.89 1037.29
 1129.66 1037.52 1139.27 1038.74 1146.96 1039.65 1158.41 1040.96 1171.46 1042.02
 1175.07 1042.28 1181.32 1042.82 1192.63 1044.12 1200.59  1044.4  1213.4 1044.59
  1225.6 1045.01 1226.55 1045.04 1226.76 1045.05 1229.95 1045.28 1236.84 1045.75
 1237.25 1045.77 1238.22 1045.81    1249 1045.99 1253.61  1045.8  1264.5 1045.44
 1271.47 1045.77 1282.77 1046.63 1287.93 1046.64 1290.16 1046.79 1298.46 1046.92
 1309.26 1047.06  1317.4  1047.1 1323.07 1046.94 1333.14 1049.02 1335.84 1049.37
 1344.08 1051.12
BR U #Mann= 3
       0      .1  650.91    .045  684.81      .1
BR U Banks=650.91,684.81
BR D #Sta/Elev= 195
       0 1059.66     .71  1059.6    5.44 1058.95   15.34 1058.31    20.9 1058.04
   30.29 1057.73   36.74 1058.03   45.51 1058.38   52.55 1057.74   60.34  1057.1
   67.85 1056.08   75.02 1055.67   83.17 1054.22   89.65 1053.61   98.64 1053.28
  114.22 1050.89  119.36 1050.81  129.65 1050.36  134.04 1049.49  144.95 1048.44
  148.72 1047.77  152.25 1047.38  175.85 1045.32  178.36 1045.17   191.4 1044.48
  193.21  1044.4  207.09 1043.56  222.81 1042.82  223.13 1042.81  231.01 1042.06
  236.23 1041.89  250.87 1041.28  252.93  1041.2  253.48 1041.13  255.04 1041.12
  267.37  1040.4  271.07  1040.2  282.31 1039.55  287.41 1039.18  303.95 1038.32
  312.27 1037.82  320.25 1037.37   327.3 1037.03  336.54 1035.95  342.22 1035.43
  353.03  1034.7  357.41 1034.23   369.4 1032.75  372.47 1032.38  385.34 1030.54
  387.23 1030.24  401.15 1027.32  401.97 1027.19  413.72 1024.59  417.19 1023.84
  417.32 1023.84  432.83 1024.75  433.78 1024.72  447.94 1024.64  449.64  1024.6
  463.17 1024.24  465.58 1024.19  478.48 1023.76  481.59 1023.42  493.56 1021.92
  497.28 1021.49  508.42 1019.95  512.85  1019.6  523.63 1019.07  528.74 1018.89
  538.88 1018.46  544.81 1018.32  554.18 1018.03  560.83  1017.8  569.25 1017.61
  571.95 1017.51  576.83 1017.31   582.9 1017.15  593.05 1016.93  596.13 1016.88
  609.37 1016.52  609.67 1016.52  625.44 1016.58  632.07 1016.73   649.3 1013.73
     651 1010.33   658.1 1010.33  663.36 1010.33  666.14 1010.33  670.58 1010.33
  674.22 1010.33     684 1010.33  688.44 1015.74  699.08 1017.34  702.51 1018.51
  704.48 1018.41  705.69 1018.19  717.64  1015.6  717.97  1015.6   730.7 1015.53
  743.65 1015.37  756.62 1015.27  756.88 1015.27   757.4 1015.26  771.24 1014.97
  775.02 1015.04  785.63 1015.02  793.26 1015.04  799.69 1015.08  811.26 1015.12
  813.82 1015.15  828.14 1015.15  831.08 1015.14   842.6 1015.22  853.96 1015.36
  857.33 1015.36  863.43 1015.19  871.15  1014.9  873.15 1014.89  884.43 1014.61
  889.94  1014.5  897.67 1014.49  906.55 1014.38  910.71 1014.35  922.95 1014.33
  926.11 1014.35  935.96 1014.43  939.94 1014.47  948.34 1014.46  957.28 1014.68
  960.59 1014.79  969.02 1015.18     974 1015.38   975.6 1015.42  989.02 1015.81
 1003.74 1016.47 1014.99 1017.19 1016.71 1017.28 1018.54  1017.4 1020.31 1017.57
 1030.15 1018.73 1031.25 1018.87 1041.41 1020.03  1048.7 1020.84  1054.7 1021.49
 1059.12 1021.94 1073.41 1024.08 1075.45 1024.34 1083.07 1024.69 1086.66 1024.94
 1094.34 1025.14 1103.22 1025.27 1106.79  1025.3  1114.6 1025.24 1118.21 1025.11
 1123.72 1025.09 1128.47 1025.06 1131.55 1025.12 1141.07 1025.71  1141.2 1025.72
  1141.3 1025.74 1151.11 1027.47 1158.12 1028.67 1163.36 1029.47 1169.92 1030.53
 1181.95 1032.79  1185.8 1033.53 1192.95 1034.66 1197.13  1035.4 1204.18 1036.45
 1212.68 1037.39 1216.08  1037.7 1223.54 1038.17 1226.77 1038.38 1233.48 1038.39
  1238.1 1038.37 1240.32 1038.07 1247.84 1037.01 1251.01  1036.6 1252.42 1036.34
 1267.46 1038.96 1268.91 1039.09 1274.84 1040.89 1278.26 1041.65 1279.15 1041.71
 1290.78 1042.19 1295.24  1042.3 1302.62 1042.37 1306.28 1042.23 1313.55 1041.97
 1323.49 1041.37 1324.47 1041.37 1335.21  1043.9 1344.05 1046.09 1344.08 1046.09
BR D #Mann= 3
       0      .1   649.3    .045  688.44      .1
BR D Banks=649.3,688.44
BC Design=,, 0 ,, 0 ,,,,,,

Type RM Length L Ch R = 1 ,25433.94,352.59,337.77,322.02
XS GIS Cut Line= 4
  1360820.498083   787175.849115  1360435.142645    787598.49699
   1360186.52627   787967.278006  1360182.382676   788294.622944
#Sta/Elev= 30
       0 1059.66   30.29 1057.73   45.51 1058.38  175.85 1045.32   327.3 1037.03
  385.34 1030.54  417.19 1023.84  432.83 1024.75  478.48 1023.76  512.85  1019.6
   582.9 1017.15  632.07 1016.73   649.3 1013.73  666.14 1010.33  674.22 1011.26
  688.44 1015.74  702.51 1018.51  717.64  1015.6  771.24 1014.97  948.34 1014.46
 1003.74 1016.47 1075.45 1024.34  1141.2 1025.72 1216.08  1037.7  1238.1 1038.37
 1252.42 1036.34 1278.26 1041.65 1302.62 1042.37 1324.47 1041.37 1344.08 1046.09
#Mann= 3 , 0 , 0
       0     .08       0   649.3     .05       0  688.44     .08       0
#XS Ineff= 2 , 0
       0     640    1018     700       0    1018
Permanent Ineff=
       F       F
Bank Sta=649.3,688.44
Exp/Cntr=0.5,0.3

Type RM Length L Ch R = 1 ,25096.17,368.28,414.94,457.09
XS GIS Cut Line= 3
   1360086.04462   787367.601914  1360012.679311   787933.562872
  1360096.525352   788394.716232
#Sta/Elev= 30
       0 1046.88   59.07 1035.67   92.14 1028.82  112.47 1022.94  124.39  1022.3
   155.2 1022.02   178.5 1020.56  217.05 1016.27  252.28 1014.28  264.48 1014.74
  290.37  1009.2  298.56  1008.2  306.78  1009.2   311.7  1011.9  317.21 1014.41
  468.37 1013.34  605.32 1014.28  643.27 1015.72  680.24    1018  738.31 1024.32
   785.4 1028.91     799 1029.77   855.1 1031.39   879.8 1030.48  903.09 1031.92
  926.16  1034.2  962.29  1039.9  995.36 1044.12 1019.91 1046.35 1039.41 1047.68
#Mann= 3 , 0 , 0
       0     .08       0  264.48     .05       0  317.21     .08       0
Bank Sta=264.48,317.21
Exp/Cntr=0.5,0.3

Type RM Length L Ch R = 1 ,24681.23,92.51,90.5,90.48
XS GIS Cut Line= 4
  1360058.667974   787318.236742  1359873.269914   787543.986121
  1359452.676583   787546.651613  1358860.216239   789061.080609
#Sta/Elev= 30
       0 1056.69  204.51 1021.13  262.61 1020.34  274.74 1018.69  290.96 1013.99
  395.76 1013.35  457.09 1015.41  478.61 1010.75  494.41 1007.41  519.01 1010.84
  534.31 1014.04  590.73 1012.37  612.36 1013.43  647.53 1018.14  670.77 1025.24
  712.72 1026.01  726.72 1029.55  740.55 1030.41  864.52 1032.48  978.88 1030.69
 1087.72 1033.79 1388.43 1052.57 1450.51 1058.17 1663.52 1063.67 1848.48 1077.44
 1899.87 1078.84 2115.25 1090.77 2201.85 1091.53 2279.18 1096.09 2338.92 1096.36
#Mann= 3 , 0 , 0
       0     .08       0  478.61     .05       0  519.01     .08       0
#XS Ineff= 2 , 0
       0  474.74    1019     550       0    1019
Permanent Ineff=
       F       F
Bank Sta=478.61,519.01
Exp/Cntr=0.5,0.3

Type RM Length L Ch R = 2 ,24635.96,,,
BEGIN DESCRIPTION:
Macedonia Church Road, SR 1607; 37003-0050
END DESCRIPTION:
Bridge Culvert--1,0,-1,-1, 0
Deck Dist Width WeirC Skew NumUp NumDn MinLoCord MaxHiCord MaxSubmerge Is_Ogee
30,40,2.6,0, 10, 10, , , 0.95, 0, 0,0,,
     260     420     530     790     897    1042    1129    1210    1289    1369
  1020.5    1020  1019.7  1019.1    1020    1025    1030    1035    1040    1045
                                                                                
     260     420     530     790     897    1042    1129    1210    1289    1369
  1020.5    1020  1019.7  1019.1    1020    1025    1030    1035    1040    1045
                                                                                
BR Coef=-1 , 0 , 0 ,, 0 ,,,0.8,-1,,0,
WSPro=,,,, 1 ,,,, 0 ,,,, 0 ,,,,-1 ,-1 ,-1 , 0 , 0 , 0 , 0 , 0
Culvert=5,9.5,25,50,0.028,0.5,1,41,1,1007.41,494.4,1006.62,512,Culvert #1  , 0 ,25
Culvert Bottom n=0.028
BR U #Sta/Elev= 30
       0 1056.69  204.51 1021.13  262.61 1020.34  290.96 1013.99  395.76 1013.35
  457.09 1015.41  478.61 1010.75     480 1007.41     509 1007.41  512.26 1009.36
  534.31 1014.04  596.82 1012.35  617.58 1013.92  647.53 1018.14  670.77 1025.24
  712.72 1026.01  726.72 1029.55  740.55 1030.41  864.52 1032.48  978.88 1030.69
 1087.72 1033.79 1388.43 1052.57 1450.51 1058.17 1663.52 1063.67 1848.48 1077.44
 1899.87 1078.84 2115.25 1090.77 2201.85 1091.53 2279.18 1096.09 2338.92 1096.36
BR U #Mann= 3
       0     .06  478.61    .045     509     .06
BR U Banks=480,509
BR D #Sta/Elev= 30
       0 1073.82   95.27 1057.66  213.76 1034.74  292.12 1023.04  428.22 1016.47
  441.14 1017.45  477.58 1013.23  492.92 1008.17     495 1006.62  527.28 1006.62
  530.39 1010.74  547.67 1015.59  623.26 1012.76  677.67  1016.8  712.72 1016.72
  733.65 1018.83  768.36 1019.56  796.98 1023.43  821.19 1029.36  834.08 1030.61
  958.61  1034.2 1057.12 1032.57    1161 1034.13 1279.39 1040.48 1330.85 1044.74
 1399.53 1046.94  1526.5 1057.69 1719.14 1063.96 1832.33 1069.57 1893.12 1074.59
BR D #Mann= 3
       0     .07  492.92    .045  530.39     .06
BR D Banks=492.92,530.39
BC Design=,, 0 ,, 0 ,,,,,,

Type RM Length L Ch R = 1 ,24590.73,267.71,266.92,263.26
XS GIS Cut Line= 4
  1360058.667974   787230.872118  1359873.269914   787456.621498
  1359452.676583    787459.28699   1358987.81749   788544.295532
#Sta/Elev= 30
       0 1073.82   95.27 1057.66  213.76 1034.74  292.12 1023.04  428.22 1016.47
  441.14 1017.45  477.58 1013.23  492.92 1008.17  518.59 1006.62  527.28 1007.11
  530.39 1010.74  547.67 1015.59  623.26 1012.76  677.67  1016.8  712.72 1016.72
  733.65 1018.83  768.36 1019.56  796.98 1023.43  821.19 1029.36  834.08 1030.61
  958.61  1034.2 1057.12 1032.57    1161 1034.13 1279.39 1040.48 1330.85 1044.74
 1399.53 1046.94  1526.5 1057.69 1719.14 1063.96 1832.33 1069.57 1893.12 1074.59
#Mann= 3 , 0 , 0
       0     .08       0  492.92     .05       0  530.39     .08       0
#XS Ineff= 2 , 0
       0  490.08    1015   540.2       0    1015
Permanent Ineff=
       F       F
Bank Sta=492.92,530.39
Exp/Cntr=0.5,0.3

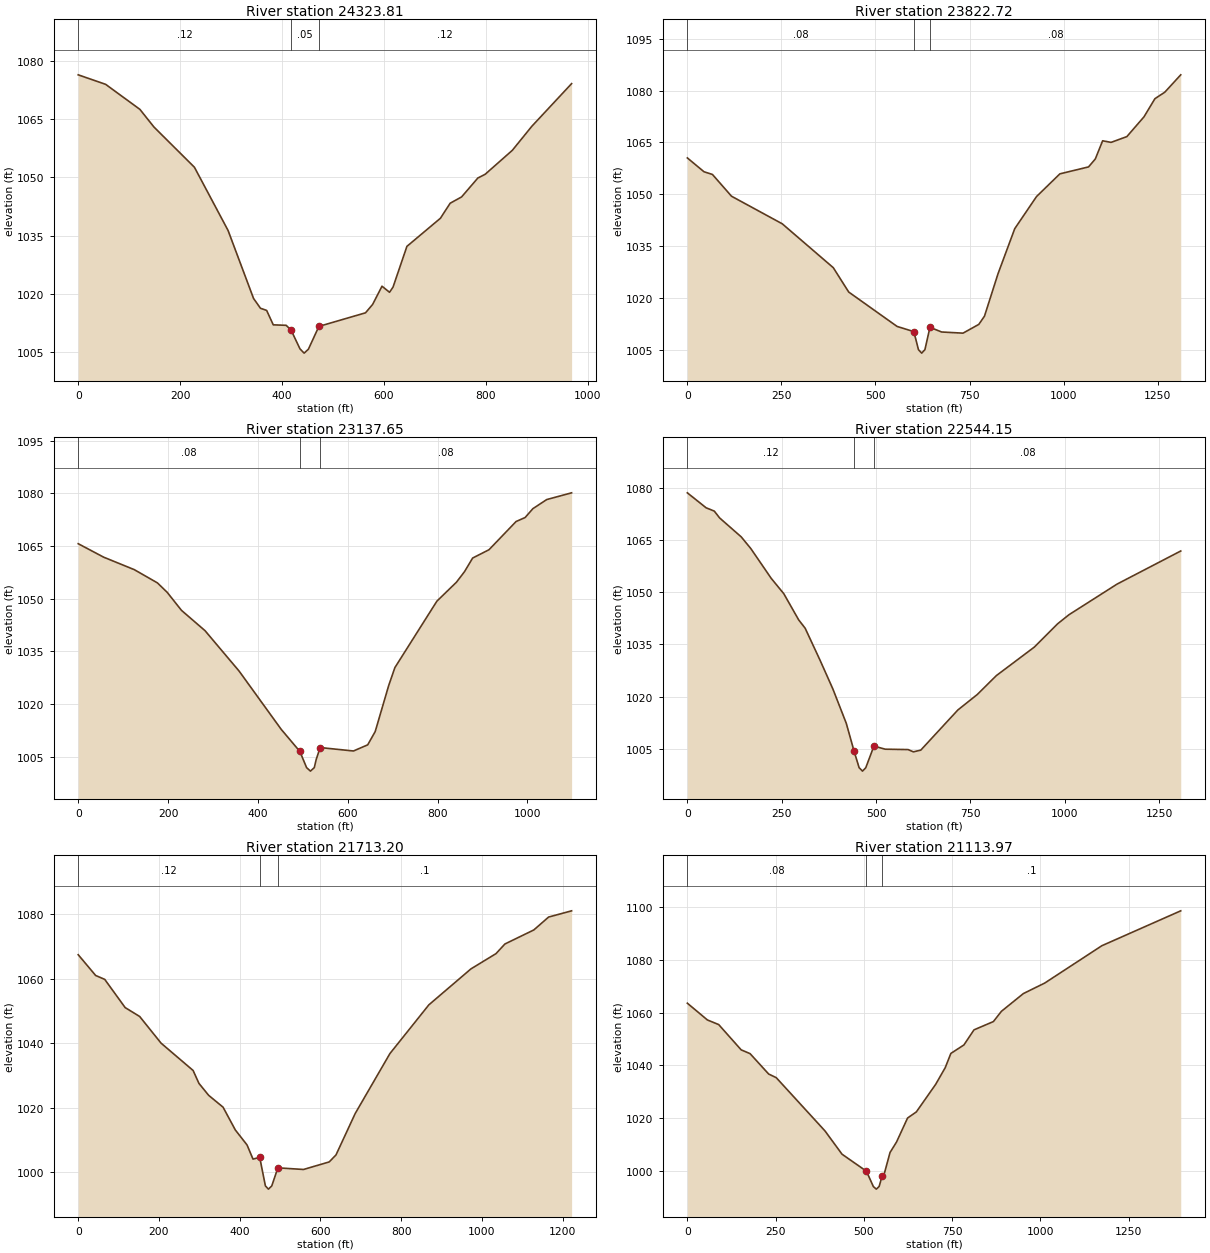
Type RM Length L Ch R = 1 ,24323.81,499.54,501.09,500.7
XS GIS Cut Line= 4
  1360010.146067   787209.673773  1359659.827078   787220.871297
  1359471.173441   787234.845606  1359048.449523   787164.973875
#Sta/Elev= 30
       0 1076.35   53.76 1073.91  121.08 1067.47  148.53 1062.95  228.06 1052.59
  294.05 1036.35  344.06 1018.87  357.63 1016.35  369.73  1015.8  382.75 1012.09
  408.02 1011.97  417.65 1010.75  435.13 1005.92  443.26 1004.82  451.66 1005.82
  472.27 1011.69  563.74 1015.18  577.67 1017.33  596.08 1022.02  610.87 1020.46
  617.71 1021.78  644.98 1032.26  710.68 1039.48  729.86 1043.35  752.29 1044.97
  784.13 1049.82  798.53 1050.79  851.79 1056.94  890.07 1063.12  968.13 1074.09
#Mann= 3 , 0 , 0
       0     .12       0  417.65     .05       0  472.27     .12       0
Bank Sta=417.65,472.27
Exp/Cntr=0.3,0.1

Type RM Length L Ch R = 1 ,23822.72,702.01,685.07,667.01
XS GIS Cut Line= 4
  1360097.365684   786814.341309  1359596.315721   786752.021673
  1359035.438854   786774.456768  1358826.044803   786901.588819
#Sta/Elev= 30
       0 1060.51   44.18 1056.51   66.75 1055.72  117.32 1049.43  252.36 1041.43
  387.84 1028.74  428.84 1021.69  557.34 1011.74  601.98 1010.23   614.2 1005.01
  622.73 1004.01  631.32 1005.01  644.76 1011.48   675.7 1010.13  732.57 1009.79
  774.58 1012.33  789.67 1014.72  825.53 1026.96  870.03 1040.03  927.96 1049.33
  990.02  1055.9 1066.24 1057.91 1084.21 1060.22 1103.64 1065.47  1126.1 1065.01
    1168 1066.68 1213.52  1072.4 1242.62 1077.66 1268.91 1079.54  1311.2 1084.56
#Mann= 3 , 0 , 0
       0     .08       0  601.98     .05       0  644.76     .08       0
Bank Sta=601.98,644.76
Exp/Cntr=0.3,0.1

Type RM Length L Ch R = 1 ,23137.65,596.37,593.5,590.28
XS GIS Cut Line= 2
  1359638.693087   785882.039355  1358741.290118   786515.207017
#Sta/Elev= 30
       0 1065.67   56.68 1061.83  124.76 1058.28  176.34  1054.5  197.94 1051.83
   229.9 1046.67   282.3 1040.88  358.18 1029.36  451.86 1012.76  493.45 1006.45
  508.33 1001.86  516.93 1000.85  525.54 1001.85  529.63 1004.11  538.57 1007.57
  612.69 1006.59  644.39 1008.34  661.08 1012.12  691.16 1025.26  704.93 1030.36
  798.38 1049.29  841.84 1054.68  859.89  1057.7  877.98 1061.58   914.4 1063.95
  974.67 1071.99  994.78 1073.13 1012.08 1075.65 1042.87 1078.25 1098.29 1080.17
#Mann= 3 , 0 , 0
       0     .08       0  493.45     .05       0  538.57     .08       0
Bank Sta=493.45,538.57
Exp/Cntr=0.3,0.1

Type RM Length L Ch R = 1 ,22544.15,830.64,830.95,827.5
XS GIS Cut Line= 4
   1359077.81622   785271.306741  1358930.741852   785655.195811
  1358472.069208   786054.041596  1358399.778413   786333.233617
#Sta/Elev= 30
       0 1078.54   49.71 1074.24    71.4 1073.29   85.51 1071.33  143.01 1065.86
  168.44 1062.49  222.24 1053.97  255.58 1049.56  295.08 1042.03  312.18 1039.65
  351.85  1030.4  385.62  1022.2  421.19 1012.31  441.56 1004.41  455.12   999.6
  464.16   998.6  472.77  999.58  494.36  1005.8  524.32  1004.9  584.89 1004.79
  598.92 1004.14   618.5 1004.63  716.84 1016.17  768.24 1020.61  818.68 1026.03
  919.13 1034.21  980.69 1040.88 1011.13 1043.52  1138.7 1052.33 1307.33 1061.83
#Mann= 3 , 0 , 0
       0     .12       0  441.56     .05       0  494.36     .08       0
Bank Sta=441.56,494.36
Exp/Cntr=0.3,0.1

Type RM Length L Ch R = 1 ,21713.20,568.15,599.24,627.88
XS GIS Cut Line= 3
  1358531.896067   785074.376673   1357948.58415   785637.746318
  1357813.973672   786026.620945
#Sta/Elev= 30
       0 1067.45   43.18 1061.02   65.78  1059.8  116.28 1051.07  152.26 1048.31
  205.34 1040.04  284.67 1031.58  299.06 1027.59  323.25 1023.87  358.86 1020.21
  389.29 1013.14  418.35 1008.49   433.1 1004.11   449.7 1004.67  463.78  995.81
  471.25  994.81  479.55   995.8  494.72 1001.41  558.19  1000.9  621.94 1003.24
  638.76 1005.42  686.26 1018.24  772.33 1036.82  868.74 1051.91  972.99 1063.05
 1035.05 1067.78 1057.31 1070.78 1128.79 1075.12 1165.46 1079.12 1222.46 1081.05
#Mann= 3 , 0 , 0
       0     .12       0   449.7     .05       0  494.72      .1       0
Bank Sta=449.7,494.72
Exp/Cntr=0.3,0.1

Type RM Length L Ch R = 1 ,21113.97,721.88,719.1,707.84
XS GIS Cut Line= 5
  1358461.527009   785002.444018  1357979.378145   784913.988536
  1357818.707166   784880.168535  1357654.508616   784698.502052
  1357411.941973   784263.273266
#Sta/Elev= 30
       0 1063.61   56.75 1057.25   88.84 1055.48  152.48 1045.88  177.74 1044.44
  230.22 1036.71  251.86 1035.31  389.98 1015.06  438.17 1006.23  507.32  999.76
  526.85  993.94   535.2  992.96  543.24  993.96  551.63  997.92  558.24  999.04
  574.15 1006.89  592.41 1010.83  623.79 1019.98  648.62  1022.3  703.34 1032.77
  730.48 1039.13  746.44 1044.53   783.3 1047.74  811.93 1053.48  866.91 1056.63
  889.62 1060.53  951.94 1067.28 1012.25 1071.26 1174.22 1085.46 1397.52 1098.71
#Mann= 3 , 0 , 0
       0     .08       0  507.32     .05       0  551.63      .1       0
Bank Sta=507.32,551.63
Exp/Cntr=0.3,0.1

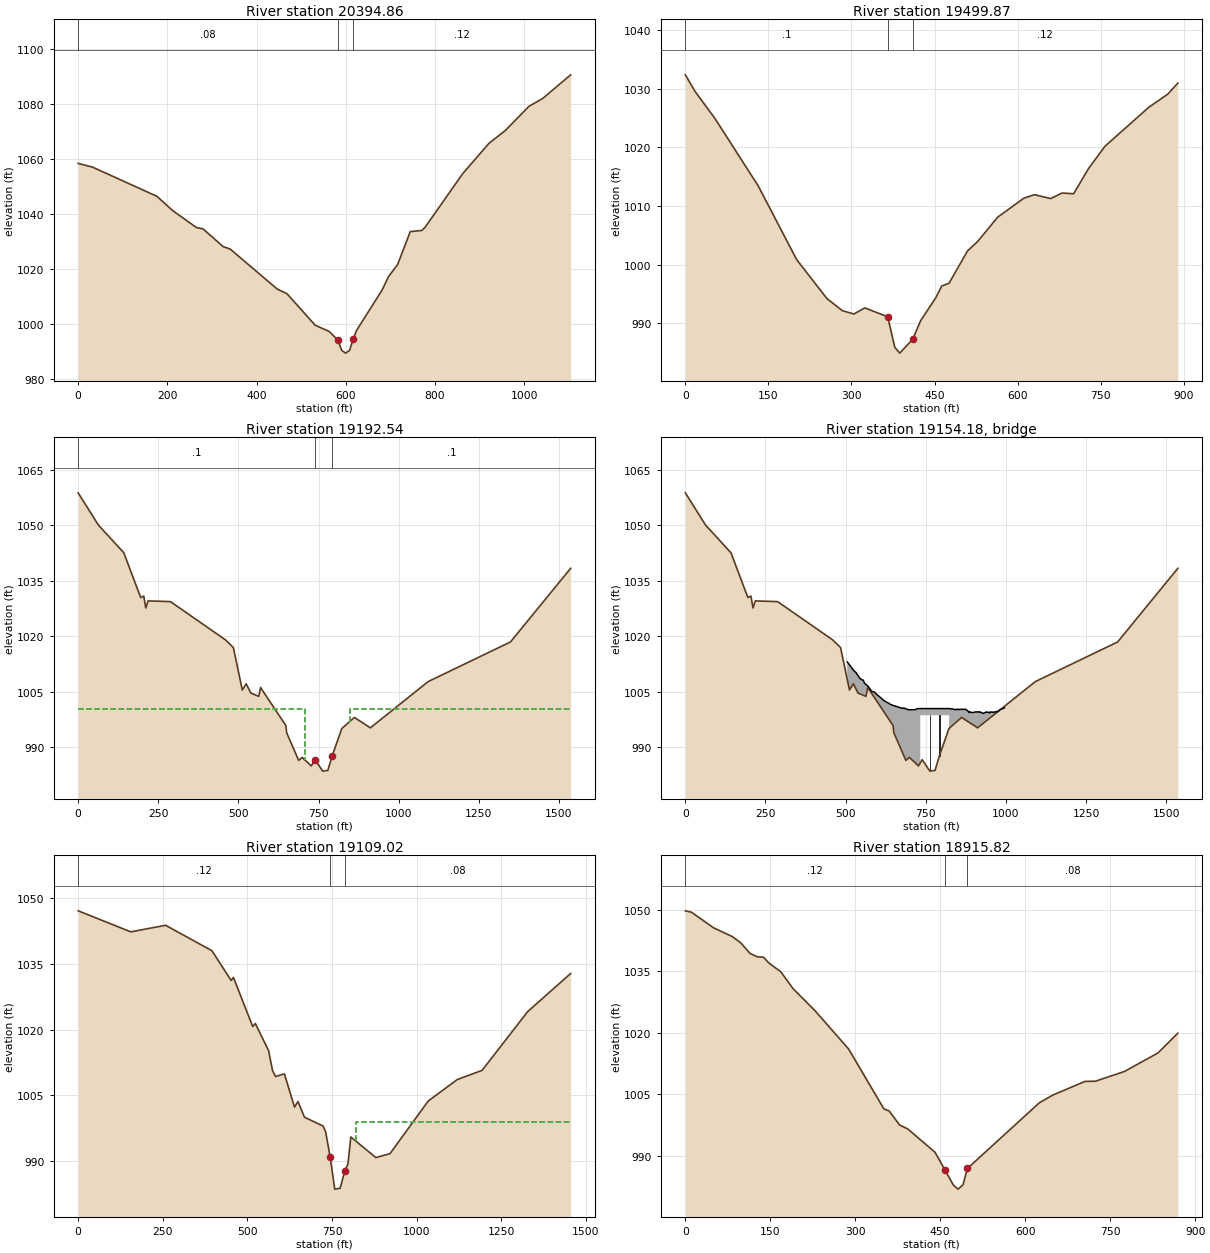
Type RM Length L Ch R = 1 ,20394.86,869.15,895,918.94
XS GIS Cut Line= 3
  1358566.795052   784515.992583  1358187.891584   784249.264498
  1357547.245588    784259.23561
#Sta/Elev= 30
       0 1058.32   31.89 1056.98  176.79 1046.32  211.94 1041.14  264.92    1035
  280.08 1034.48  325.23 1028.01  340.78 1027.16  446.03 1012.63  468.23  1010.9
  531.25  999.46  563.01  997.16  582.15  994.04  590.88  990.29  599.52  989.29
  608.42  990.28  616.91   994.6  624.22  997.57  681.39 1012.25  695.82 1017.13
  716.14 1021.51  744.57  1033.5  770.74 1033.93  778.03 1035.13   862.1 1054.59
  921.19 1065.65  957.94 1070.32 1010.37 1079.05 1041.62 1081.97 1104.09 1090.54
#Mann= 3 , 0 , 0
       0     .08       0  582.15     .05       0  616.91     .12       0
Bank Sta=582.15,616.91
Exp/Cntr=0.3,0.1

Type RM Length L Ch R = 1 ,19499.87,338.12,307.33,275.3
XS GIS Cut Line= 4
  1358919.186793   783797.156794  1358688.610136   783692.349198
  1358520.918009   783514.176292  1358129.636333   783514.176292
#Sta/Elev= 30
       0 1032.36   17.52 1029.53   53.46 1024.92  131.52 1013.43  201.01 1000.86
  255.67  994.22  283.57  992.15  304.37  991.59  324.09  992.63  365.41  991.11
  378.15  985.92   387.1  984.92  410.58   987.3  424.73  990.43  452.29  994.38
  463.05  996.37  476.15  996.83   509.5 1002.34  528.21 1003.99  563.77 1008.08
     611 1011.32  630.29 1011.93   659.6 1011.27  680.26 1012.21  701.16 1012.09
  727.81 1016.36  757.66 1020.18  836.48  1026.8  871.24 1029.08  889.24 1030.95
#Mann= 3 , 0 , 0
       0      .1       0  365.41     .05       0  410.58     .12       0
Bank Sta=365.41,410.58
Exp/Cntr=0.5,0.3

Type RM Length L Ch R = 1 ,19192.54,91.28,83.53,75.06
BEGIN DESCRIPTION:
Upstream xs of Bridge 37003-0059
END DESCRIPTION:
XS GIS Cut Line= 6
  1359392.348254   783081.380726  1358842.986445   783266.797086
  1358347.429889   783376.789355   1358197.10758   783345.145296
  1358086.030645   783301.177371  1357926.357578   783227.126097
#Sta/Elev= 30
       0  1058.8      63  1050.1   142.4  1042.6   195.1  1030.5   204.6  1030.9
     211  1027.7   218.4  1029.6     288  1029.4   459.1  1019.1   484.2    1017
   512.1  1005.5   524.2  1007.2   538.7  1004.7   563.6  1003.8     569  1006.2
   648.1   995.9   650.3     994     688   986.5     699   987.3   727.5     985
   738.9   986.7   762.9   983.6   778.9   983.8   792.9   987.8   822.4   995.1
   861.8   998.1   911.8   995.3    1092  1007.8  1348.7  1018.5  1536.5  1038.4
#Mann= 3 , 0 , 0
       0      .1       0   738.9     .05       0   792.9      .1       0
#XS Ineff= 2 , 0
       0   708.5  1000.4   847.3       0  1000.4
Permanent Ineff=
       F       F
Bank Sta=738.9,792.9
Exp/Cntr=0.5,0.3

Type RM Length L Ch R = 3 ,19154.18,,,
BEGIN DESCRIPTION:
Bridge : 37003-0059
END DESCRIPTION:
Bridge Culvert--1,0,-1,-1, 0
Deck Dist Width WeirC Skew NumUp NumDn MinLoCord MaxHiCord MaxSubmerge Is_Ogee
24.4,28,2.6,0, 78, 80, , , 0.95, 0, 0,0,,
   505.1     522   526.3   533.2   533.3   533.4   544.3   552.1     555   559.2
   568.2   569.4   573.7   580.8   591.2   592.8   601.2   604.6   611.2   618.7
   622.5     628   631.6   640.2   654.1     655   658.2     661   661.7   671.3
   680.2   682.2   684.3   689.5   694.2   698.7   707.8     716   718.6   725.2
   729.4   732.9   732.9   822.9   822.9   832.7   843.6   845.1   851.5   853.1
   856.7   869.2   874.7   878.8   883.9   885.8   887.3     896   905.5   905.8
   906.2   908.4   915.8   917.3   918.9   929.5   939.3   940.5   946.4   948.8
   951.5   961.8   970.5   972.8   979.1   980.1     982   995.5
  1013.1  1011.2  1010.7  1010.2  1010.2  1010.1  1008.7  1008.2  1008.2  1007.3
  1006.7  1006.6  1006.1  1005.2  1004.9  1004.7    1004  1003.8  1003.3  1002.7
  1002.5  1002.2  1002.1  1001.6  1001.2  1001.1  1001.1    1001    1001  1000.7
  1000.6  1000.5  1000.6  1000.4  1000.2  1000.2  1000.2  1000.2  1000.3  1000.5
  1000.5  1000.5  1000.5  1000.5  1000.5  1000.4  1000.2  1000.3  1000.3  1000.2
  1000.3  1000.3  1000.3    1000   999.7   999.4   999.6   999.4   999.6   999.6
   999.6   999.6   999.6   999.5   999.6   999.2   999.6   999.5   999.5   999.3
   999.6   999.5   999.7   999.6    1000  1000.1  1000.2  1000.7
                                                                                
                                                                                
                                                                                
                                                                                
                   998.7   998.7
                                                                                
                                                                                
                                                                
   502.7   519.6   523.9   530.8   530.9     531   541.9   549.7   552.6   556.8
   565.8     567   571.3   578.3   588.8   590.4   598.8   602.2   608.8   615.3
   616.3   620.1   625.6   629.2   637.8   651.7   652.6   655.8   658.5   659.3
   668.9   677.8   679.8   681.9   687.1   691.8   696.3   705.4   713.6   716.2
   722.8     727     728     728     818     818   830.3   841.2   842.7   849.1
   850.7   854.3   866.8   872.3   876.4   881.5   883.4   884.9   893.6   903.1
   903.4   903.8     906   913.4   914.9   916.4     927   936.9   938.1     944
   946.3     949   959.4   968.1   970.4   976.7   977.7   979.6   993.1  1000.2
  1013.1  1011.2  1010.7  1010.2  1010.2  1010.1  1008.7  1008.2  1008.2  1007.3
  1006.7  1006.6  1006.1  1005.2  1004.9  1004.7    1004  1003.8  1003.3  1001.2
  1002.7  1002.5  1002.2  1002.1  1001.6  1001.2  1001.1  1001.1    1001    1001
  1000.7  1000.6  1000.5  1000.6  1000.4  1000.2  1000.2  1000.2  1000.2  1000.3
  1000.5  1000.5  1000.5  1000.5  1000.5  1000.5  1000.4  1000.2  1000.3  1000.3
  1000.2  1000.3  1000.3  1000.3    1000   999.7   999.4   999.6   999.4   999.6
   999.6   999.6   999.6   999.6   999.5   999.6   999.2   999.6   999.5   999.5
   999.3   999.6   999.5   999.7   999.6    1000  1000.1  1000.2  1000.7  1000.9
                                                                                
                                                                                
                                                                                
                                                                                
                           998.7   998.7
                                                                                
                                                                                
                                                                                
Pier Skew, UpSta & Num, DnSta & Num=  ,762.87, 2 ,758, 2 , 0 , 0 , 0 ,,
       1       1
   982.6   999.2
       1       1
  982.62  999.22
Pier Skew, UpSta & Num, DnSta & Num=  ,792.87, 2 ,788, 2 , 0 , 0 , 0 ,,
       1       1
   986.8   999.2
       1       1
  986.82  999.22
Abutment Skew #Up #Dn= , 3 , 3
   732.9   746.9   761.9
   996.5   995.2   984.7
     728     742     757
   996.5   995.2   984.7
Abutment Skew #Up #Dn= , 3 , 3
   792.9   801.9   822.9
   987.8   989.3     997
     788     797     818
   987.8   989.3     997
BR Coef=-1 , 1 , 0 ,, 0 ,,,0.8,0,1.2,0,
WSPro=,,,, 1 ,,,, 0 ,,,, 0 ,,,,-1 ,-1 ,-1 , 0 , 0 , 0 , 0 , 0
BC Design=,, 0 ,, 0 ,,,,,,

Type RM Length L Ch R = 1 ,19109.02,192.83,193.2,190.83
BEGIN DESCRIPTION:
Down stream xs of Bridge 37003-0059
END DESCRIPTION:
XS GIS Cut Line= 6
  1359337.472633   782981.036772  1358635.064722   783225.625224
  1358566.078259   783261.686314  1358332.464932   783296.179568
  1358204.049891   783280.350437  1357961.069135   783169.273503
#Sta/Elev= 30
       0  1047.1   155.4  1042.3   258.2  1043.8   395.2    1038     452  1031.2
   458.8  1031.9   515.7  1020.7   523.4  1021.4   562.6  1015.2   574.4  1010.6
   583.3  1009.3   609.3  1009.9   639.2  1002.3   649.3  1003.6   668.7    1000
   723.7     998     731   996.7   744.4     991     758   983.6     774   983.8
     788   987.8     797   989.3   805.5   995.5   879.6   990.8   921.4   991.7
  1034.2  1003.7  1119.9  1008.6  1193.4  1010.7    1328  1024.1    1455  1032.8
#Mann= 3 , 0 , 0
       0     .12       0   744.4     .05       0     788     .08       0
#XS Ineff= 2 , 0
       0   696.9   998.9  820.24       0     999
Permanent Ineff=
       F       F
Bank Sta=744.4,788
Exp/Cntr=0.5,0.3

Type RM Length L Ch R = 1 ,18915.82,669.28,688.41,700.13
XS GIS Cut Line= 3
  1358865.542333   782904.210902  1358304.243157   783239.736111
  1358097.601164   783178.529918
#Sta/Elev= 30
       0  1049.7   10.83 1049.36   49.76 1045.57   82.92 1043.43   97.69 1041.92
   114.3 1039.31  127.08  1038.5  137.93 1038.42   147.2 1037.02  168.61 1034.84
  190.36 1030.71  229.17 1025.33   288.3 1016.03  350.47 1001.46  359.77 1000.95
  378.33  997.53  392.64  996.57  440.79  990.89  458.17  986.62  473.09  982.91
  481.33  981.91  489.96   982.9  497.99  986.95  624.96 1002.94  648.42  1004.8
  705.53 1008.15  723.75 1008.19  775.06 1010.56  834.37 1015.08  869.45  1019.9
#Mann= 3 , 0 , 0
       0     .12       0  458.17     .05       0  497.99     .08       0
Bank Sta=458.17,497.99
Exp/Cntr=0.3,0.1

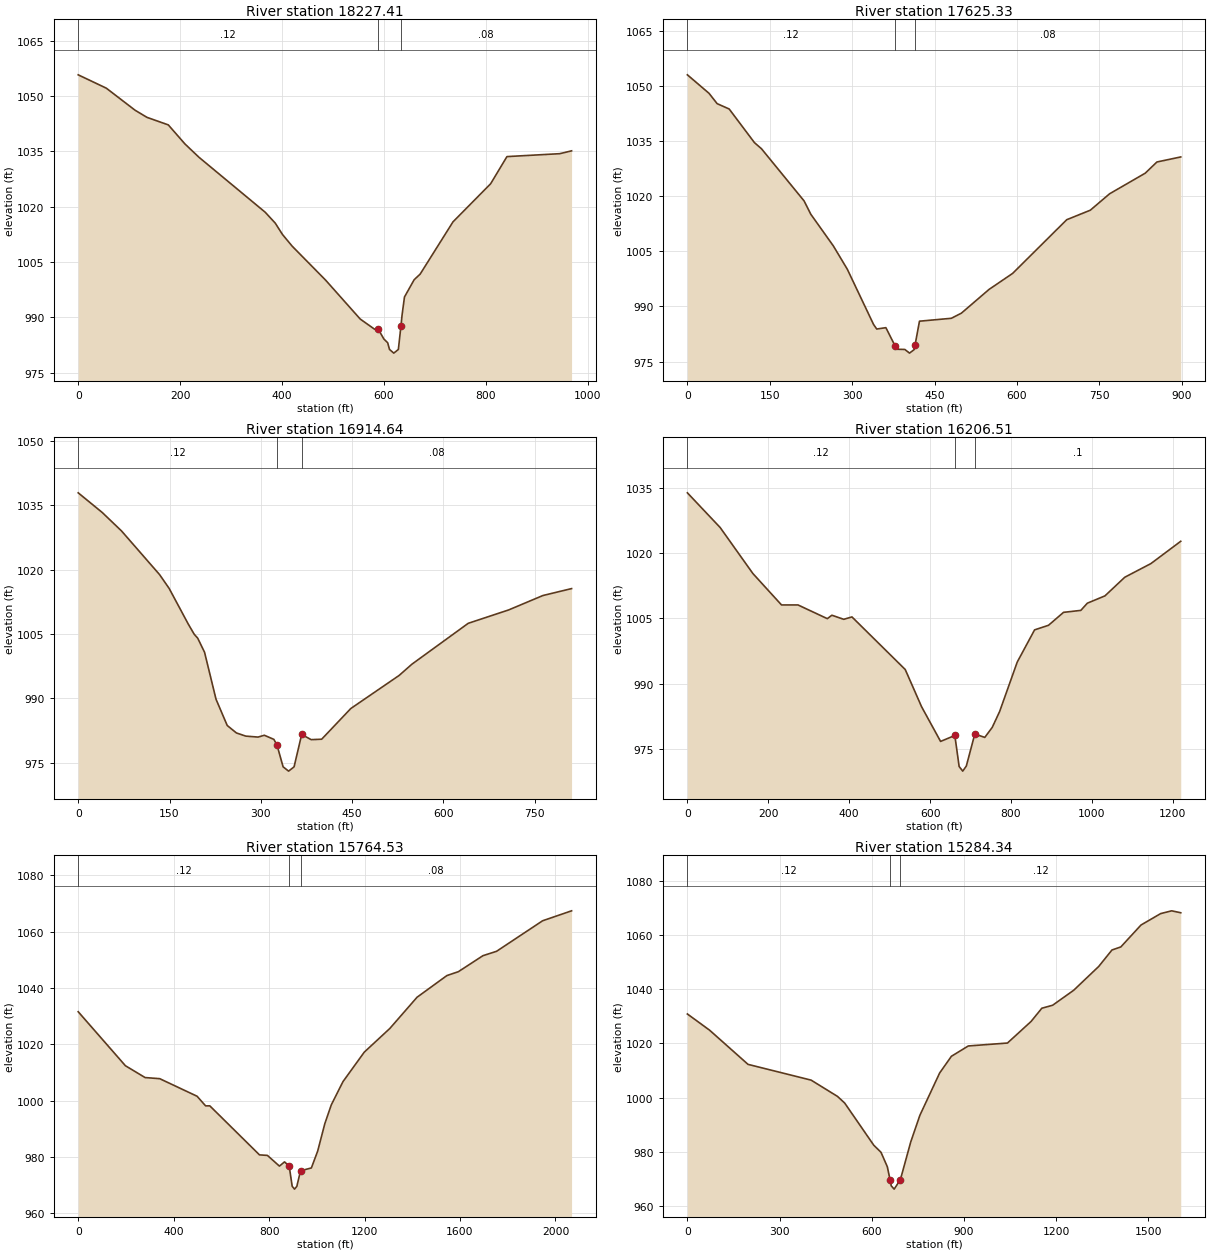
Type RM Length L Ch R = 1 ,18227.41,609.79,602.08,591.64
XS GIS Cut Line= 2
  1358667.990095    782606.31471    1357701.7873   782664.718042
#Sta/Elev= 30
       0 1055.77   55.14 1052.15  111.46 1046.18  135.01 1044.23  176.76 1042.19
   209.5 1037.01  236.89 1033.41  366.79 1018.51  386.57 1015.55   400.8 1012.46
  419.76  1009.3  485.47 1000.07  553.34  989.52  581.44  986.77  588.56  986.81
  599.73  984.11  607.23  983.09  610.78  981.28  619.18  980.28  628.15  981.28
   633.2  987.63  635.41  990.61   640.1   995.5  659.13 1000.19  670.87 1001.71
  735.29 1015.88  809.22 1026.23  841.21 1033.59  944.86 1034.38  967.97 1035.15
#Mann= 3 , 0 , 0
       0     .12       0  588.56     .05       0   633.2     .08       0
Bank Sta=588.56,633.2
Exp/Cntr=0.3,0.1

Type RM Length L Ch R = 1 ,17625.33,725.16,710.69,692.21
XS GIS Cut Line= 2
  1358587.636514   781965.053901  1357737.064495   782253.150903
#Sta/Elev= 30
       0 1053.02    39.4 1047.99   54.21 1045.17   76.08 1043.72  122.13 1034.56
  134.95 1032.89  212.45  1018.7  224.61 1015.09  265.64 1006.47  291.19 1000.09
  338.94  985.07  344.69  983.84   361.3  984.21   378.4  979.15  381.55  978.33
   395.8  978.28  404.41  977.28  413.02  978.28  414.47  979.52  422.46  985.97
   480.5  986.76  498.78  988.16  549.15  994.62  591.97  998.97  690.51 1013.59
  733.36 1016.17  768.59 1020.65  833.37 1026.25  854.72  1029.3  898.04 1030.67
#Mann= 3 , 0 , 0
       0     .12       0   378.4     .05       0  414.47     .08       0
Bank Sta=378.4,414.47
Exp/Cntr=0.3,0.1

Type RM Length L Ch R = 1 ,16914.64,731.34,708.12,681.9
XS GIS Cut Line= 3
  1358147.104265   781229.370906  1357878.098119   781522.832186
  1357801.239233   781928.088171
#Sta/Elev= 30
       0 1037.86   39.41 1033.29   71.26 1028.97  133.69 1018.82  149.38 1015.61
  180.84  1007.3  190.54 1004.94  196.37 1004.01  207.58 1000.74  226.43   989.8
  244.83  983.69   259.9  981.95  275.36  981.21  295.52  980.99  305.84  981.41
  321.43  980.46  326.54  979.15  336.66  974.06  345.65  973.06  354.67  974.06
  367.17   981.6  382.74  980.39     400  980.49  447.89  987.64  527.17  995.33
  548.38  997.97  640.83 1007.48  707.19 1010.59  763.53 1013.95  810.58 1015.56
#Mann= 3 , 0 , 0
       0     .12       0  326.54     .05       0  367.17     .08       0
Bank Sta=326.54,367.17
Exp/Cntr=0.3,0.1

Type RM Length L Ch R = 1 ,16206.51,425.48,441.99,458.3
XS GIS Cut Line= 4
  1357476.405281    781006.29852  1357284.340628   781364.949866
  1357331.376889   781800.035089  1357507.762772   782131.248647
#Sta/Elev= 30
       0 1033.84    81.1 1025.87  161.77 1015.34  232.69 1008.11  273.43 1008.11
  346.01 1004.96  357.18 1005.75  386.58 1004.81  406.84 1005.36  538.58  993.29
  579.09  984.73  625.97  976.79  661.22  978.15  671.85  971.03  680.74  969.97
  689.61  971.14   710.6  978.49  735.26  977.71  753.74  980.02  771.91  983.64
  815.42  994.99  858.36 1002.39  892.79 1003.44  929.92 1006.41   972.7 1006.86
  988.76 1008.51 1032.31 1010.19  1081.4 1014.47 1145.93  1017.6 1219.71 1022.72
#Mann= 3 , 0 , 0
       0     .12       0  661.22     .05       0   710.6      .1       0
Bank Sta=661.22,710.6
Exp/Cntr=0.3,0.1

Type RM Length L Ch R = 1 ,15764.53,430,480.18,517.51
XS GIS Cut Line= 6
  1357448.967493   781008.258349  1357245.143776   781386.508121
  1356896.400398   781634.626937  1356833.515868   781770.876776
   1356671.85466   782400.294887   1356346.47146   782649.117364
#Sta/Elev= 30
       0 1031.55  197.74 1012.37  280.32 1008.16  341.75 1007.76  498.18 1001.52
  533.89   998.1  551.49  998.11  759.72  980.69  792.94   980.5  843.27   976.7
  864.58  978.19  884.04  976.75  896.78  969.52  906.63  968.52  916.31  969.52
  931.59  975.03  977.17  976.05 1003.59  982.04 1033.57   991.8 1060.56  998.45
 1109.46  1006.7 1198.63 1017.17 1306.23 1025.63 1419.94 1036.69 1545.09  1044.4
 1593.07 1045.77 1696.06 1051.46 1753.22 1053.02 1946.26 1063.87 2067.53  1067.4
#Mann= 3 , 0 , 0
       0     .12       0  884.04     .05       0  931.59     .08       0
Bank Sta=884.04,931.59
Exp/Cntr=0.3,0.1

Type RM Length L Ch R = 1 ,15284.34,770.73,756.8,742.27
XS GIS Cut Line= 4
    1357435.2486   780990.619751  1357241.224072   781351.230926
  1356429.848905    781249.31909  1356059.368598   781175.322811
#Sta/Elev= 30
       0 1030.86   72.44 1024.87  197.27 1012.27  402.63 1006.45  488.37 1000.45
  511.71  998.01  606.26  982.46  629.95  979.82  650.45   974.5  659.79  969.48
  663.13  967.47  672.77  966.24  693.01  969.76  726.62  983.65  756.41  993.48
  820.63 1009.08  858.92 1015.25  913.85 1019.06 1041.28 1020.14 1118.03 1028.09
 1153.11 1032.98 1188.33 1034.09 1256.77 1039.61 1338.51 1048.43 1381.26 1054.47
 1410.11  1055.6 1475.81 1063.69 1539.72  1067.9 1575.53 1068.92 1605.04 1068.21
#Mann= 3 , 0 , 0
       0     .12       0  659.79     .05       0  693.01     .12       0
Bank Sta=659.79,693.01
Exp/Cntr=0.3,0.1