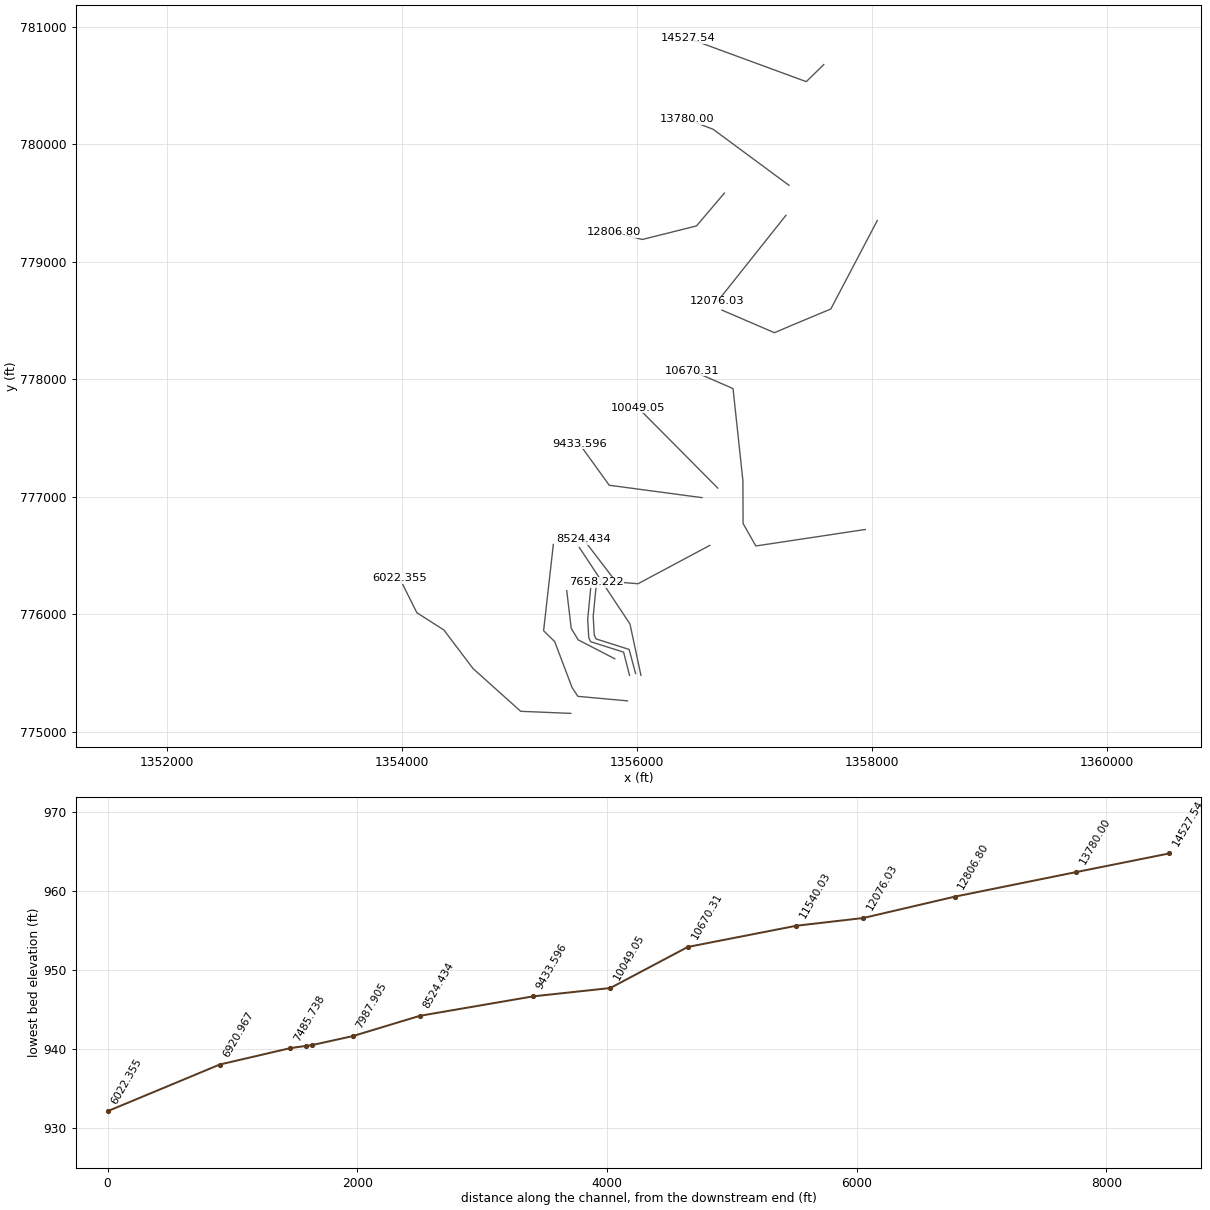
HEC-RAS study GladeCreek.prj: Glade Creek

--- GladeCreek.g01 (geometry) --- (continued)

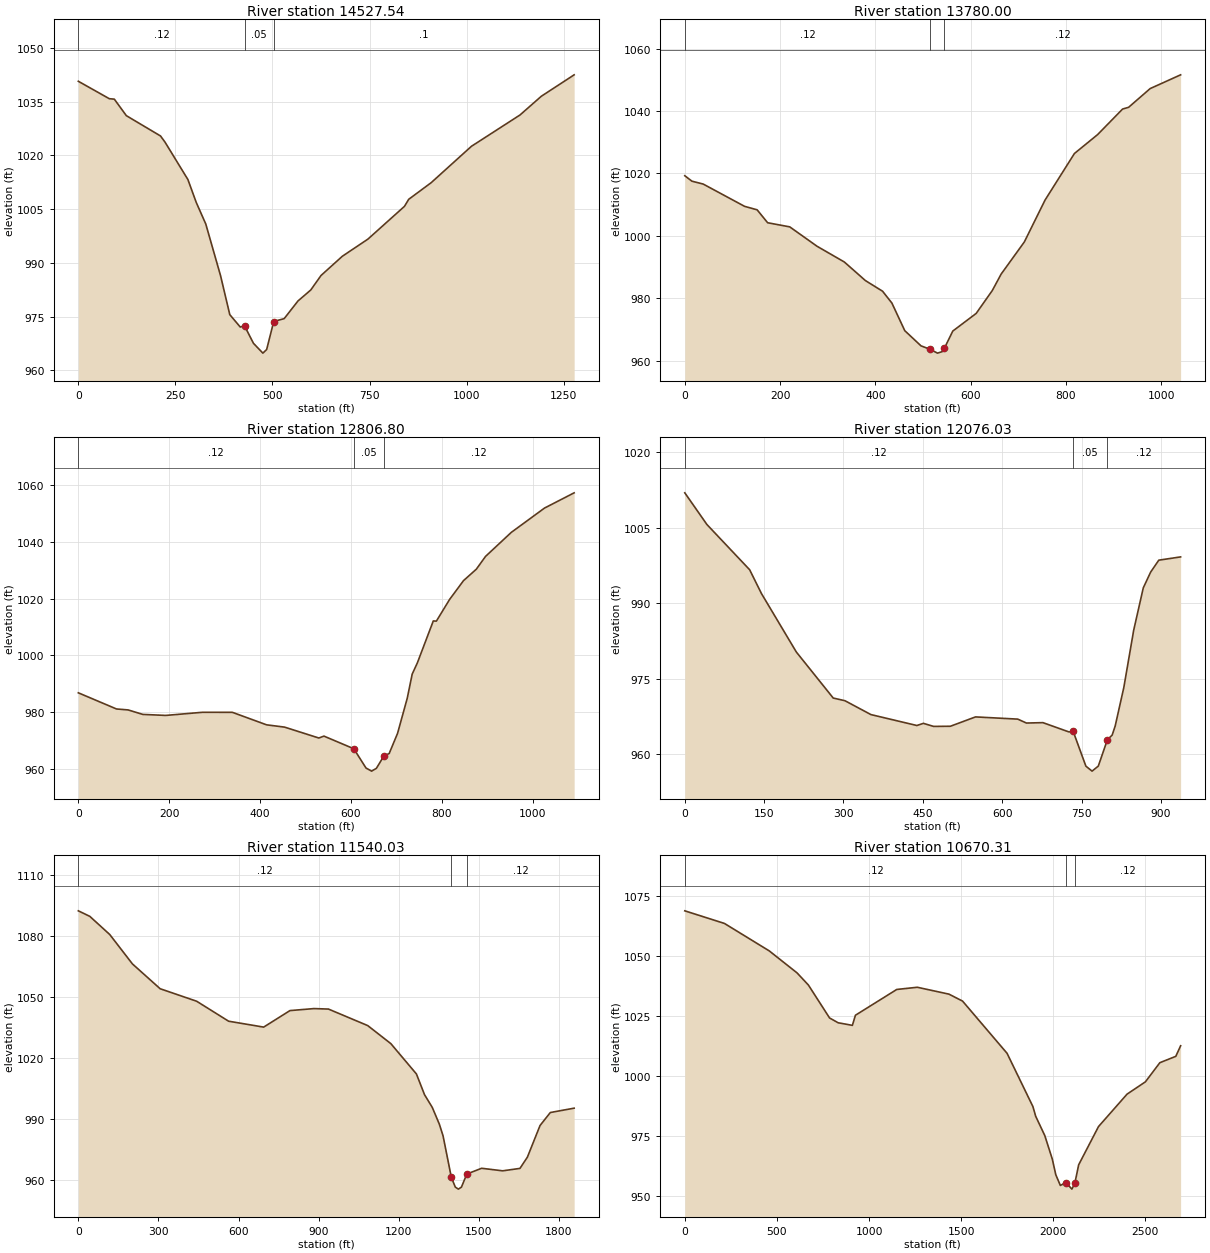
Type RM Length L Ch R = 1 ,14527.54,755.31,747.54,738.07
XS GIS Cut Line= 3
  1357588.116353    780677.04479  1357439.168257   780532.016398
  1356435.728438   780900.466934
#Sta/Elev= 30
       0 1040.72   79.86 1035.85   92.66 1035.73  123.62 1031.12   211.6 1025.45
  223.16 1023.74  282.19 1013.28  303.72 1006.87  328.19 1000.87  366.34   986.4
  390.07  975.55     417   972.1     428  972.43     451  967.55  475.23  964.81
  484.99  965.82   503.2  973.64  530.11  974.44  565.67  979.38  598.67  982.45
  624.99  986.49  679.89  991.86  745.79  996.65   839.9  1005.8  850.78 1007.76
   908.5 1012.39  1012.3 1022.56 1137.42 1031.31 1192.22 1036.53 1276.84 1042.52
#Mann= 3 , 0 , 0
       0     .12       0     428     .05       0   503.2      .1       0
Bank Sta=428,503.2
Exp/Cntr=0.3,0.1

Type RM Length L Ch R = 1 ,13780.00,944.79,973.21,999.62
XS GIS Cut Line= 3
  1357292.180036   779650.086841  1356647.391517   780126.328791
  1356423.969373   780212.561905
#Sta/Elev= 30
       0 1019.26   14.92 1017.52   38.66 1016.59  125.46 1009.46  151.87 1008.34
  173.96  1004.2  220.39 1002.88  277.68  996.67  334.96  991.63  379.21  985.68
  415.25  982.27  434.84  978.48   461.9  969.63  495.94  964.77  514.84  963.69
  530.61  962.44  542.07     963  545.12  964.03  562.73  969.51  611.82  975.16
  645.73  982.51  664.25  987.76  712.89  998.04  756.49 1011.48  818.09 1026.38
  866.76 1032.43  919.24 1040.62   931.9 1041.18  977.09 1047.17 1041.08 1051.58
#Mann= 3 , 0 , 0
       0     .12       0  514.84     .05       0  545.12     .12       0
Bank Sta=514.84,545.12
Exp/Cntr=0.3,0.1

Type RM Length L Ch R = 1 ,12806.80,711.71,730.77,750.19
XS GIS Cut Line= 4
  1356742.682627   779583.891831  1356505.118722   779304.404907
  1356043.965361   779189.116578  1355802.907926   779252.001108
#Sta/Elev= 30
       0  986.85   83.98  981.17  109.73  980.83  141.85  979.26  192.35   978.9
  273.01     980  339.07  979.99   414.4  975.59  453.94  974.79  529.37  970.96
  540.55  971.63   606.3  967.19  633.14  960.41  645.57  959.32  656.02  960.31
   672.7  964.69   684.1  965.49  702.55  972.57  723.88  984.92  734.83  993.43
  746.26   997.4  781.24 1012.11  788.05 1012.05  817.05 1019.65  847.75 1026.28
  876.04 1030.32   896.2 1034.79  952.89 1043.24 1026.03 1051.79 1091.28 1057.15
#Mann= 3 , 0 , 0
       0     .12       0   606.3     .05       0   672.7     .12       0
Bank Sta=606.3,672.7
Exp/Cntr=0.3,0.1

Type RM Length L Ch R = 1 ,12076.03,574.88,536,494.18
XS GIS Cut Line= 2
  1357266.702031   779395.307205  1356683.291627   778661.585063
#Sta/Elev= 30
       0 1011.95   41.83 1005.65  122.67  996.65  144.79  991.95  210.88   980.3
  280.61  971.15  302.76  970.62  351.91  967.86  438.75  965.69   451.1  966.12
  470.38  965.51  502.11  965.54  549.65   967.4  629.49  966.96  645.88  966.18
  677.05  966.26  726.34  964.41  734.18  964.55   758.3  957.61  769.96  956.62
  781.76  957.62  798.93  962.86  807.95  963.78  813.69  965.59  829.95  973.22
  848.64  984.62  866.81  993.06  880.84  996.21  896.14  998.56   937.4  999.21
#Mann= 3 , 0 , 0
       0     .12       0  734.18     .05       0  798.93     .12       0
Bank Sta=734.18,798.93
Exp/Cntr=0.3,0.1

Type RM Length L Ch R = 1 ,11540.03,900.99,869.72,827.05
XS GIS Cut Line= 5
  1358043.568203   779350.624816  1357648.004306    778597.77736
  1357310.198287   778456.628858  1357168.900122   778396.072494
   1356721.72107   778588.219755
#Sta/Elev= 30
       0 1092.32   42.91 1089.61  117.56  1080.7  202.54 1066.26  306.39 1054.06
   443.1 1047.92  562.82 1038.11  694.13 1035.21   792.6 1043.32  882.62 1044.31
  936.84 1044.07    1084 1035.95  1170.5 1027.09  1266.3 1012.19 1296.48 1002.06
 1325.61  995.78 1352.17  987.53 1366.07  981.77 1397.08  961.38  1411.9  956.64
 1423.39  955.64 1434.86  956.64 1455.06  963.06 1510.44  965.88 1589.23  964.63
 1653.97  965.82  1681.8  971.33 1729.24  986.89 1767.74  993.26 1856.99   995.4
#Mann= 3 , 0 , 0
       0     .12       0 1397.08     .05       0 1455.06     .12       0
Bank Sta=1397.08,1455.06
Exp/Cntr=0.3,0.1

Type RM Length L Ch R = 1 ,10670.31,599.48,621.26,640.68
XS GIS Cut Line= 6
  1357941.487193   776722.038884  1357009.998004   776581.677489
  1356901.536921   776773.079365  1356900.180497   777137.282279
  1356816.047935   777920.944778  1356470.182903   778071.168972
#Sta/Elev= 30
       0 1068.76  215.28 1063.51  458.43 1052.09   609.4 1042.93  671.04 1037.87
  785.89 1024.18  832.25 1022.18  909.61  1021.1  926.29 1025.31 1150.69 1036.04
 1262.21 1036.95 1433.88 1034.09 1507.72  1031.2 1749.33 1009.47 1889.56  987.32
 1904.94  983.24 1954.15  975.23 1994.88  965.46 2013.91  958.93 2038.57  954.49
 2069.48  955.66 2101.15  952.95 2117.15  955.37 2138.08  963.08 2245.75  978.98
 2400.77  992.48 2500.19  997.59 2578.71 1005.56 2665.31 1008.21 2691.46 1012.61
#Mann= 3 , 0 , 0
       0     .12       0 2069.48     .05       0 2117.15     .12       0
Bank Sta=2069.48,2117.15
Exp/Cntr=0.3,0.1

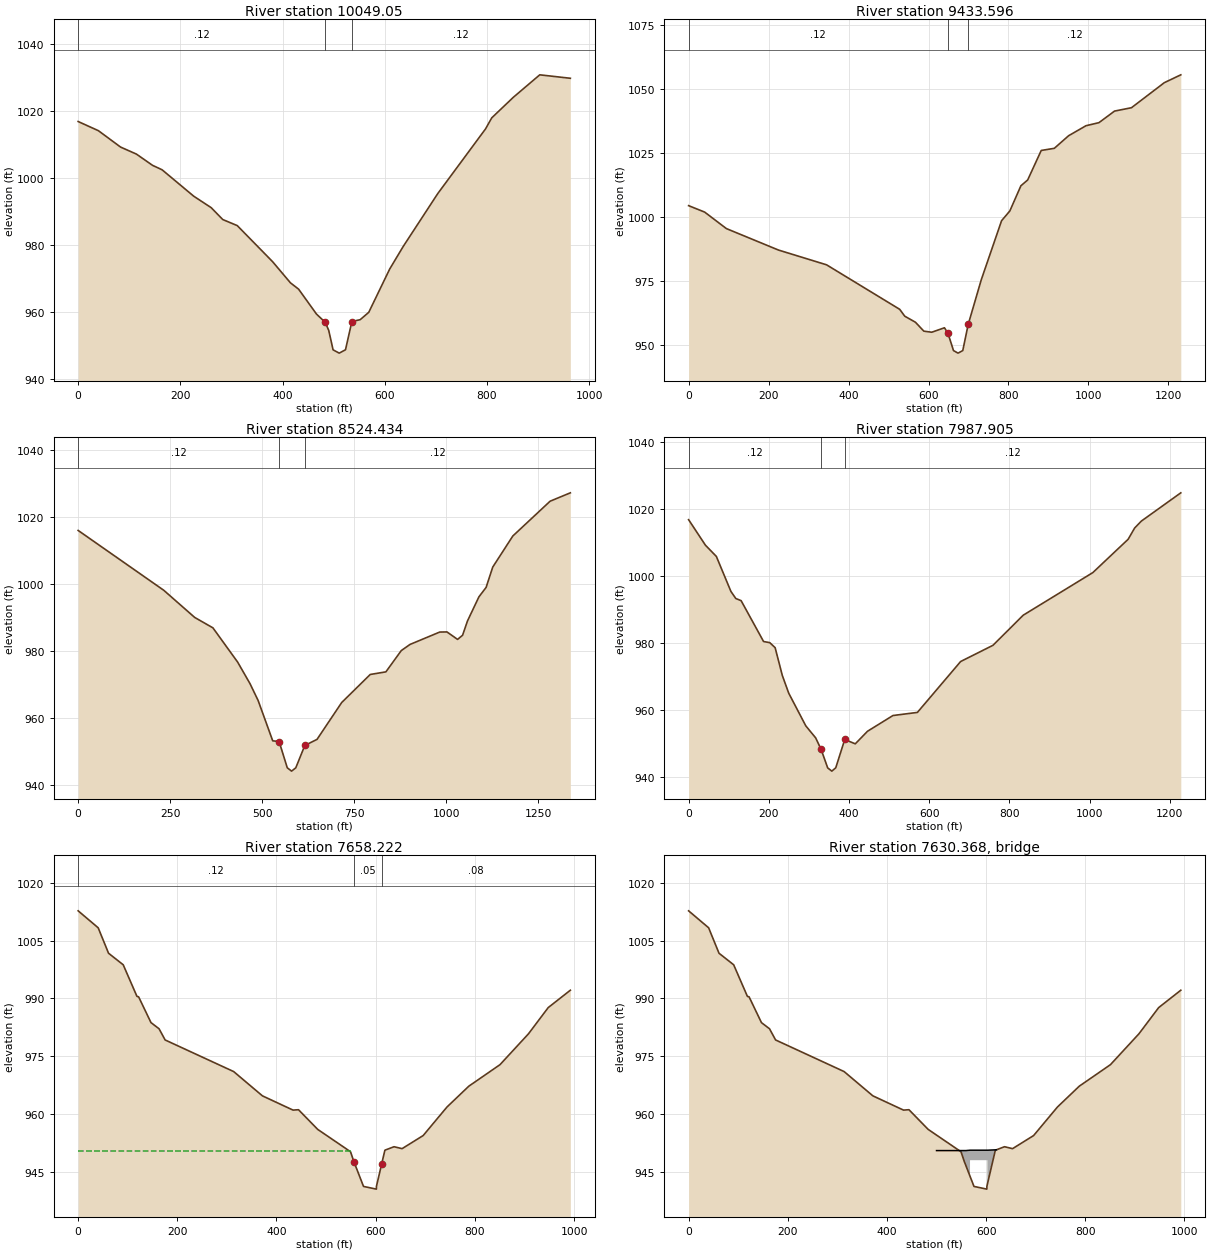
Type RM Length L Ch R = 1 ,10049.05,593.99,615.46,634.19
XS GIS Cut Line= 2
  1356686.588369   777073.872622  1356007.992608   777757.368026
#Sta/Elev= 30
       0 1016.89   39.67 1014.15   83.05 1009.26  114.07 1007.16  145.63  1003.8
  164.16 1002.49   226.3  994.58  260.33  991.17  282.94  987.63  311.39  985.81
  380.58  975.03  415.43  968.73  431.44  966.83  466.41   959.4  483.42  956.95
  490.35  954.52  498.87  948.72  510.84  947.74  523.15  948.74  535.61  957.16
  551.91  957.73  568.71  959.93  609.62  972.84  635.97  979.56  703.64  995.36
   797.2 1014.69  809.38 1017.99  851.65 1024.13  903.28 1030.83  963.15  1029.8
#Mann= 3 , 0 , 0
       0     .12       0  483.42     .05       0  535.61     .12       0
Bank Sta=483.42,535.61
Exp/Cntr=0.3,0.1

Type RM Length L Ch R = 1 ,9433.596,889.32,909.16,927.41
XS GIS Cut Line= 3
  1356551.849136   776993.029073  1355763.012162    777098.37069
  1355508.232527   777451.142504
#Sta/Elev= 30
       0 1004.39    40.1 1001.88   94.47  995.42  224.57  987.03  345.09  981.24
  528.04  963.82  540.61  961.14  567.32  958.78  588.29  955.29  608.17  954.87
  639.92  956.61  648.65  954.46  662.51  947.69   673.9  946.69  685.69  947.69
  699.28  957.91  731.97   975.4  782.71  998.49  803.45 1002.33  831.09 1012.17
  848.05 1014.45  881.95 1025.99   914.6 1026.82  950.49 1031.76  993.95 1035.67
 1026.35 1036.87 1065.25 1041.39 1107.61 1042.71 1189.87 1052.52    1231 1055.58
#Mann= 3 , 0 , 0
       0     .12       0  648.65     .05       0  699.28     .12       0
Bank Sta=648.65,699.28
Exp/Cntr=0.3,0.1

Type RM Length L Ch R = 1 ,8524.434,591.91,536.53,479.99
XS GIS Cut Line= 4
  1356617.993854   776586.361576  1356007.992608   776260.537627
  1355821.807488   776275.236412  1355542.529784    776640.25726
#Sta/Elev= 30
       0 1016.01  232.66  998.17  316.86  990.06  366.38  986.95  433.64  976.73
  467.29  970.28  489.19   965.3  528.91  953.26  546.36  953.05  568.41  945.22
  580.22  944.22  591.66  945.22  616.12  951.87  649.34  953.69  716.45  964.69
     794  973.05  836.54  973.83  878.33  980.17  901.96     982  982.89   985.7
 1002.51  985.74 1031.35  983.51 1044.98  984.75 1058.35  989.02 1089.49  996.22
  1108.9  999.01 1126.96 1005.08 1181.55 1014.35  1282.9 1024.73 1337.93 1027.23
#Mann= 3 , 0 , 0
       0     .12       0  546.36     .05       0  616.12     .12       0
Bank Sta=546.36,616.12
Exp/Cntr=0.3,0.1

Type RM Length L Ch R = 1 ,7987.905,334.32,329.68,324.92
XS GIS Cut Line= 3
  1356032.490629   775481.499843  1355939.398092   775917.565004
  1355508.232527   776569.212947
#Sta/Elev= 30
       0 1016.85   41.96 1009.22    69.2 1005.86  105.51  995.39  117.68  993.28
  130.95  992.63  186.94  980.41  202.43  980.07  215.76  978.57  233.68  970.25
  249.67  964.96  292.16   955.2  316.79   951.6  330.49  948.13  346.79  942.62
  357.07  941.65  366.89  942.64  389.36  951.11  415.57  949.81  446.19  953.58
  509.56  958.28  570.49  959.21  678.29  974.43  758.96  979.28  834.32  988.28
 1007.86 1001.02 1095.99 1010.99 1112.08 1014.34  1128.8 1016.42 1227.27 1024.88
#Mann= 3 , 0 , 0
       0     .12       0  330.49     .05       0  389.36     .12       0
Bank Sta=330.49,389.36
Exp/Cntr=0.5,0.3

Type RM Length L Ch R = 1 ,7658.222,48.13,48.12,48.11
BEGIN DESCRIPTION:
Upstream xs of Bridge 37003-0063
END DESCRIPTION:
XS GIS Cut Line= 6
  1355986.980061   775496.753836  1355931.996127   775701.657096
  1355651.418018   775790.799102  1355635.343204   775824.410068
  1355626.575128    775983.69659  1355654.340694   776271.581437
#Sta/Elev= 30
       0  1012.7    40.4  1008.3    61.3  1001.7    90.9   998.7   118.6   990.5
   121.9   990.4   146.9   983.7   163.2   982.1   175.4   979.2   313.6     971
   371.6   964.7   433.4     961   444.4   961.1   483.1     956   549.3   950.2
     556 947.653   575.5   941.2   601.5   940.5   601.5   941.2     612 946.972
   618.6   950.6   637.1   951.5   653.3     951   695.8   954.4   743.8   961.8
   787.8   967.2   850.8   972.8   908.2   980.8     948   987.6   992.6   992.1
#Mann= 3 , 0 , 0
       0     .12       0     556     .05       0     612     .08       0
#XS Ineff= 2 , 0
       0   549.6   950.5   620.4       0   950.5
Permanent Ineff=
       F       F
Bank Sta=556,612
Exp/Cntr=0.5,0.3

Type RM Length L Ch R = 3 ,7630.368,,,
BEGIN DESCRIPTION:
Bridge : 37003-0063
END DESCRIPTION:
Bridge Culvert--1,0,-1,-1, 0
Deck Dist Width WeirC Skew NumUp NumDn MinLoCord MaxHiCord MaxSubmerge Is_Ogee
17.9,20,2.6,0, 7, 8, , , 0.95, 0, 0,0,,
     500   558.7   567.5   567.5   602.5   602.5   620.9
   950.5   950.5   950.6   950.6   950.6   950.6   950.7
                             948     948
     500   568.6   577.3   577.3   612.3   612.3   630.7     700
   950.5   950.5   950.5   950.5   950.5   950.5   950.7   950.7
                           947.9   947.9
BR Coef=-1 , 1 , 0 ,, 0 ,,,0.8,0,1.2,0,
WSPro=,,,, 1 ,,,, 0 ,,,, 0 ,,,,-1 ,-1 ,-1 , 0 , 0 , 0 , 0 , 0
BC Design=,, 0 ,, 0 ,,,,,,

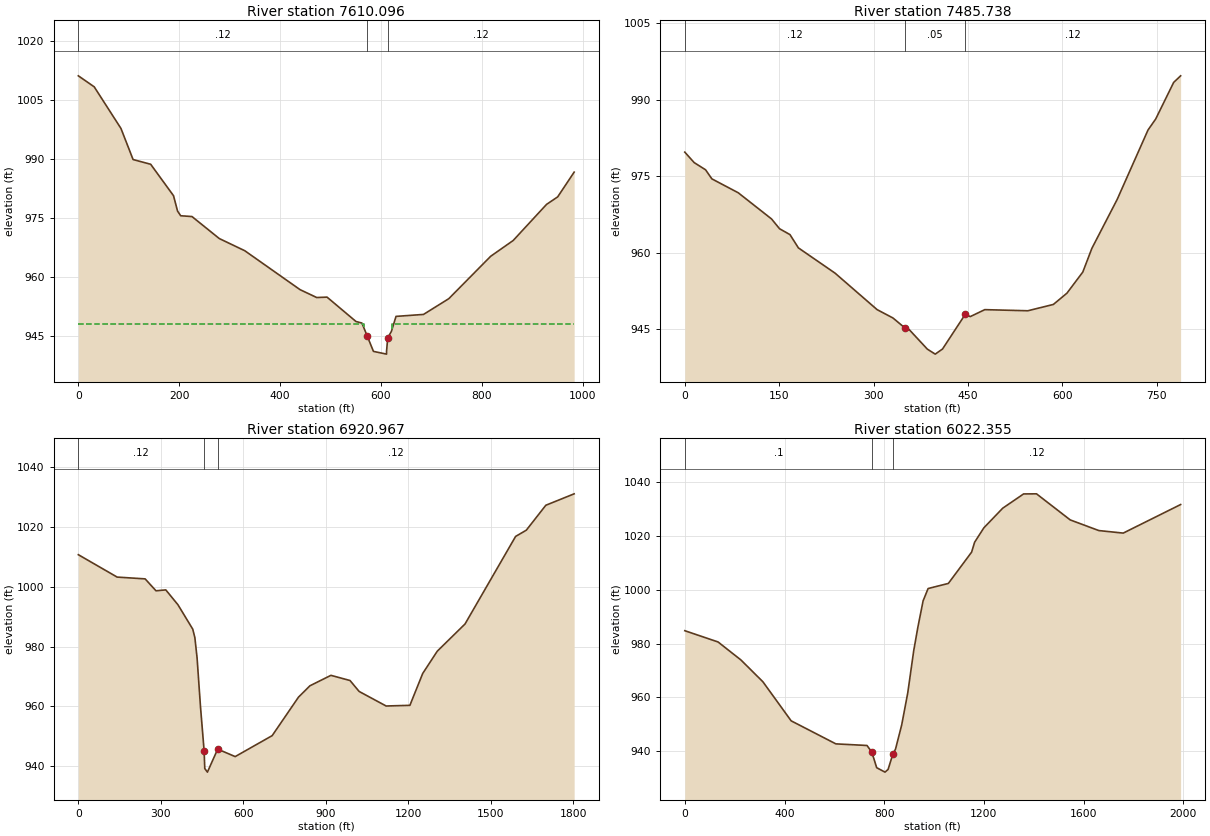
Type RM Length L Ch R = 1 ,7610.096,108.94,124.36,138.34
BEGIN DESCRIPTION:
Down stream xs of Bridge 37003-0063
END DESCRIPTION:
XS GIS Cut Line= 6
  1355935.362439   775481.572207  1355885.233116   775678.275591
  1355604.654961   775767.417597  1355588.580193   775801.028517
  1355579.812117   775960.315085  1355607.577684   776248.199931
#Sta/Elev= 30
       0  1011.2    31.5  1008.4    84.6   997.8   108.6   989.9   143.5   988.7
   188.8   980.7   196.8   976.8     203   975.6   225.4   975.4   279.6   969.8
   330.2   966.7   439.8   956.8   472.8   954.8   493.3   954.9   550.7   948.7
   562.5   948.3  572.92  945.02   585.3   941.1   611.3   940.4   611.3   941.1
   613.6   944.5     621   946.2   630.1     950   684.6   950.5   734.7   954.5
   817.9   965.3   862.4   969.3   928.7   978.5   950.7   980.4   983.4   986.7
#Mann= 3 , 0 , 0
       0     .12       0  572.92     .05       0   613.6     .12       0
#XS Ineff= 2 , 0
       0   567.1   948.1   622.6       0   948.1
Permanent Ineff=
       F       F
Bank Sta=572.92,613.6
Exp/Cntr=0.5,0.3

Type RM Length L Ch R = 1 ,7485.738,561.81,564.77,560.97
XS GIS Cut Line= 4
   1355809.89508   775622.165036  1355498.965914   775782.870008
  1355439.574961    775880.69045  1355401.145518   776202.100349
#Sta/Elev= 30
       0  979.72   14.89  977.67   33.01  976.26   43.05  974.48   84.99  971.75
   137.9  966.62  150.64   964.7  167.18  963.55  180.56  960.95   238.8     956
  305.62  948.85  330.96   947.2     350  945.24  356.54  944.95  385.54   941.1
  398.06  940.12  409.65  941.12  445.82  947.92  453.83  947.48  476.85  948.84
  545.23  948.62  585.86  949.86  607.44  952.07  632.65  956.21  647.13  960.87
  687.22  970.43   736.4  984.08   748.5  986.21   777.1  993.39  788.14  994.68
#Mann= 3 , 0 , 0
       0     .12       0     350     .05       0  445.82     .12       0
Bank Sta=350,445.82
Exp/Cntr=0.3,0.1

Type RM Length L Ch R = 1 ,6920.967,877.22,898.61,905.98
XS GIS Cut Line= 6
  1355918.113367   775263.984473  1355496.150153   775302.344765
  1355446.829777   775377.238653  1355298.868651   775768.148266
  1355204.440178   775860.730392  1355287.381019   776594.437632
#Sta/Elev= 30
       0 1010.67  141.03 1003.19  242.93 1002.59  282.35  998.61  318.05  998.91
  362.26  993.94  415.99   985.8   423.7  982.96  431.73  976.21  444.17  959.85
  457.34  945.14  459.72  939.24  469.32  938.04  506.65  945.72  570.31  943.23
  704.75  950.23  800.42  963.08  842.04  966.88  918.32  970.37  987.81  968.64
 1020.88  964.99 1119.03  960.13 1205.47  960.35 1252.09     971 1304.95  978.43
 1405.88  987.52  1589.8 1016.77 1628.78 1018.86 1699.66 1027.18 1802.67    1031
#Mann= 3 , 0 , 0
       0     .12       0  457.34     .05       0  506.65     .12       0
Bank Sta=457.34,506.65
Exp/Cntr=0.3,0.1

Type RM Length L Ch R = 1 ,6022.355,932.25,929.61,914.64
XS GIS Cut Line= 6
  1355436.081384   775157.518098  1355009.863842    775174.98603
  1354604.607857   775538.318995   1354355.89183   775867.110463
  1354126.209522   776013.851884  1353979.468102   776307.334771
#Sta/Elev= 30
       0  984.77  133.42  980.58  225.27  973.87  313.45  965.74  426.58  951.22
  605.91  942.64  730.78  942.04  749.95  939.64  769.76  933.77  803.12  932.12
   815.5  933.13  834.91   938.9  845.19  940.66  870.05  949.67  894.49  961.69
  918.24   977.3  934.67  985.93  955.85  995.86     976 1000.47 1057.24 1002.37
 1150.58 1014.03 1162.57 1017.71 1199.74 1023.08 1275.29 1030.38 1359.06 1035.69
 1410.79 1035.73 1546.08 1026.02 1660.82 1022.05 1758.71 1021.11 1988.94 1031.74
#Mann= 3 , 0 , 0
       0      .1       0  749.95     .05       0  834.91     .12       0
Bank Sta=749.95,834.91
Exp/Cntr=0.3,0.1