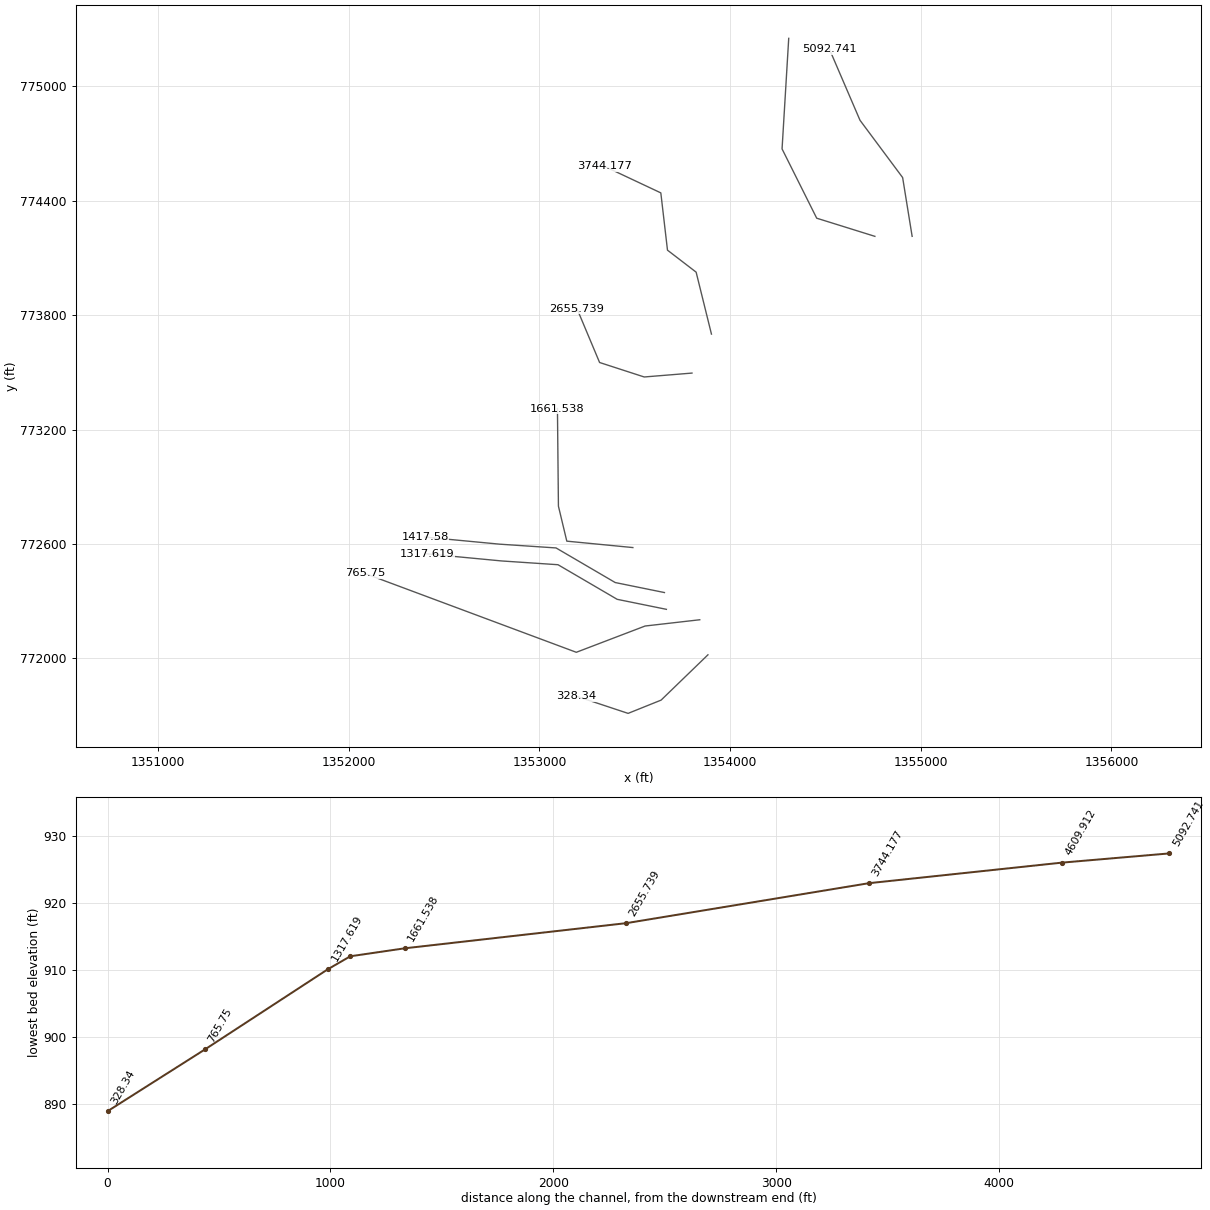
HEC-RAS study GladeCreek.prj: Glade Creek

--- GladeCreek.g01 (geometry) --- (continued)

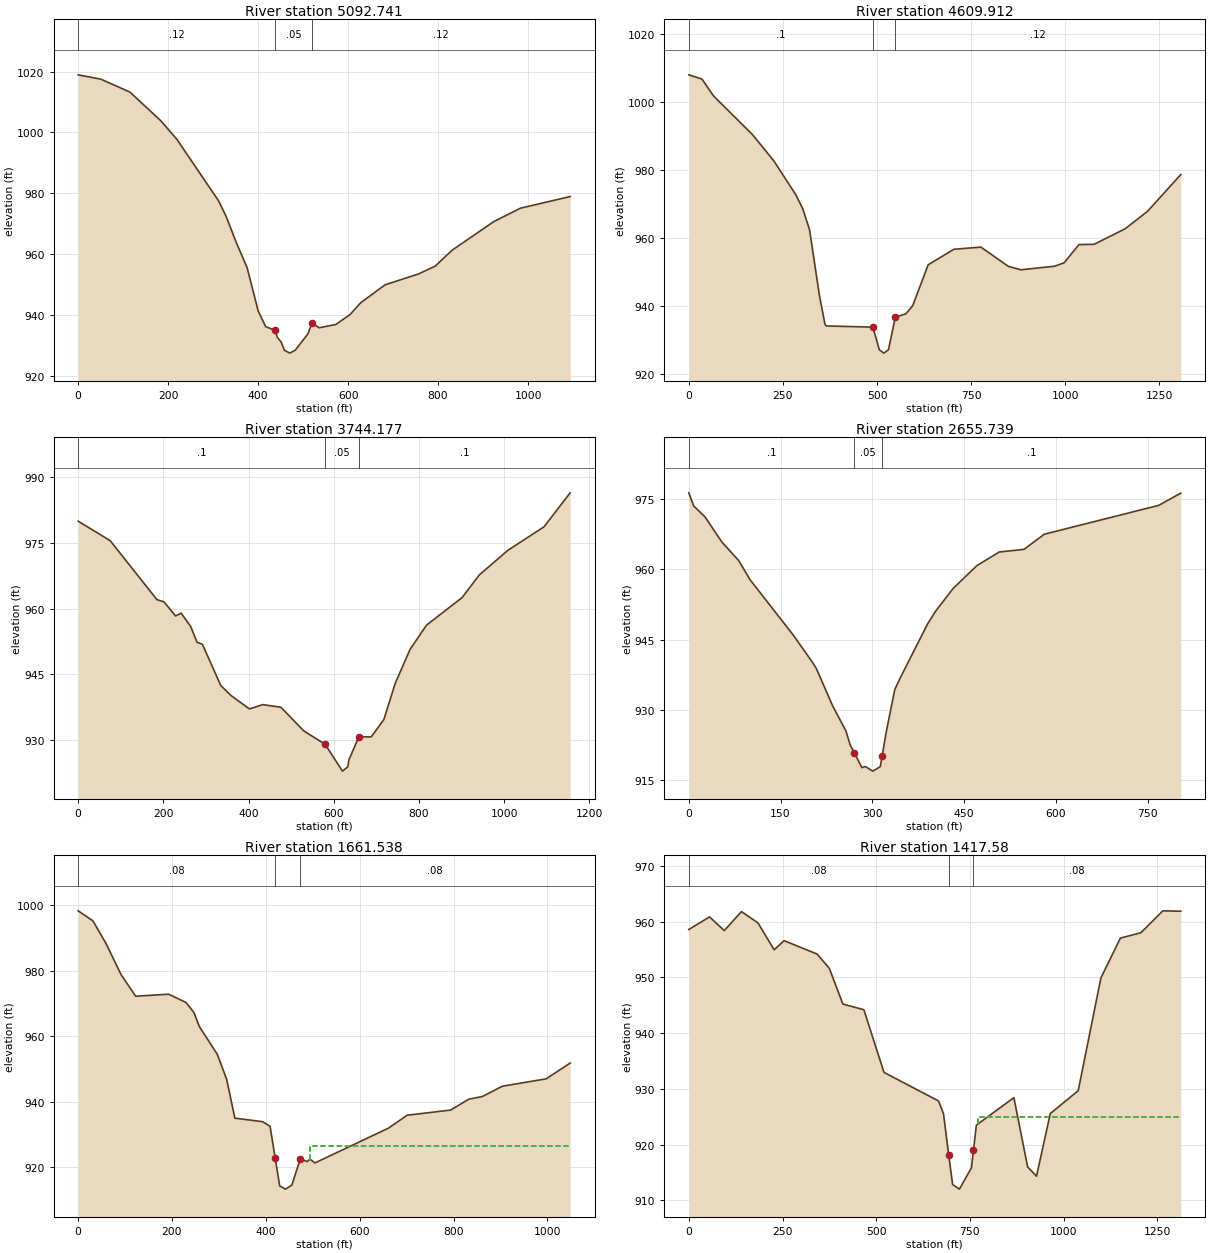
Type RM Length L Ch R = 1 ,5092.741,487.84,482.83,477.33
XS GIS Cut Line= 4
  1354954.889221   774213.422805  1354905.056245   774521.685409
  1354681.466742   774822.133797   1354520.76177    775195.94754
#Sta/Elev= 30
       0 1018.93   50.76 1017.49  115.24 1013.25  183.81 1003.81  219.79  997.66
  312.26  977.47  329.21  972.29  351.44  963.81  375.59  955.51  400.11  941.32
  416.69  936.13  438.34  934.85  442.73   932.6  451.42  931.04  458.28  928.39
  470.45   927.4   482.7  928.39  511.06  933.78  519.56  937.31  535.83  935.74
  572.68  936.82  603.98  940.03  628.05  943.97  682.29  949.87     757  953.47
  793.91  956.03  831.32  961.26  924.61  970.72  983.39  975.08 1093.67   978.9
#Mann= 3 , 0 , 0
       0     .12       0  438.34     .05       0  519.56     .12       0
Bank Sta=438.34,519.56
Exp/Cntr=0.3,0.1

Type RM Length L Ch R = 1 ,4609.912,874.98,865.74,854.76
XS GIS Cut Line= 4
   1354759.53509   774213.422805  1354454.383616   774308.576638
  1354272.717134   774671.909603  1354307.652999   775251.844916
#Sta/Elev= 30
       0 1007.97   34.98 1006.72   65.78 1001.75  169.41  990.34   226.4  982.55
  284.17  972.66  302.36  968.64  320.79  962.33  346.64  943.21  361.68  934.53
  364.71  934.03  488.98  933.67  506.04  927.01  518.17  926.02  530.29  927.02
  548.63  936.58  576.85  937.61  594.87  940.02  635.81  952.03  704.21  956.61
  775.97  957.23  848.93  951.56  882.09  950.56  971.62  951.61  997.02  952.63
 1036.38  957.99 1076.69  958.06 1158.89  962.63 1218.13  967.74 1306.85  978.61
#Mann= 3 , 0 , 0
       0      .1       0  488.98     .05       0  548.63     .12       0
Bank Sta=488.98,548.63
Exp/Cntr=0.3,0.1

Type RM Length L Ch R = 1 ,3744.177,1043.2,1088.44,1119.54
XS GIS Cut Line= 5
  1353902.397014    773700.69266  1353822.044551   774025.596136
   1353671.82031   774140.884511  1353636.884445   774441.332899
  1353339.929634   774581.076362
#Sta/Elev= 30
       0  979.97   75.23  975.52  184.87  962.07  201.33  961.57  228.74  958.35
  241.75  958.98  264.16  955.94  279.05  952.34  291.65  951.88  334.69  942.49
  358.47  940.22  402.01  937.13  432.99  938.12  475.95  937.52  529.46  932.13
  579.57  929.08  620.36  922.95  632.77  923.93  635.48  925.51  658.81   930.8
  687.77  930.75  717.52  934.71   744.1  942.96  779.12  950.74  817.71  956.26
   901.2  962.54  941.38  967.69 1008.75  973.33 1093.35  978.67 1154.72  986.43
#Mann= 3 , 0 , 0
       0      .1       0  579.57     .05       0  658.81      .1       0
Bank Sta=579.57,658.81
Exp/Cntr=0.3,0.1

Type RM Length L Ch R = 1 ,2655.739,1022.31,994.2,961.87
XS GIS Cut Line= 4
  1353800.385574   773496.298647  1353549.709206   773475.829574
  1353315.756085    773551.74815  1353196.974133   773834.728606
#Sta/Elev= 30
       0  976.28    8.01  973.48   26.43  971.17   54.26  965.76    81.6  961.85
  100.17  957.76  171.12  945.91   203.5  939.91  208.58  938.83  235.47   930.8
  256.83  925.56  263.98  922.51  270.45  920.93  282.97  917.73  288.76  917.96
  300.73  916.98  313.05  917.94  316.21  920.24  322.59   925.2  336.76  934.37
  345.52   936.8  390.44  948.36  402.71  950.92  432.12   955.9   470.7  960.74
   507.5  963.67  547.99  964.23   581.2  967.46  768.32  973.61  804.37  976.22
#Mann= 3 , 0 , 0
       0      .1       0  270.45     .05       0  316.21      .1       0
Bank Sta=270.45,316.21
Exp/Cntr=0.3,0.1

Type RM Length L Ch R = 1 ,1661.538,206.63,243.96,274.07
XS GIS Cut Line= 4
  1353490.185819   772581.209397  1353143.796126   772614.814402
  1353099.851158   772798.349211  1353094.681154   773310.178813
#Sta/Elev= 30
       0  998.34   31.42  995.29   59.69  988.28    91.4  978.85   122.6  972.23
  192.87  972.84  230.05   970.3  246.74  967.25  258.43  962.92  296.68  954.44
  316.58  946.78  334.03  934.92  393.03  933.85  409.01  932.44     420 922.732
  429.53  914.22  441.83  913.22  455.47  914.47  473.76  922.57  487.85  921.63
  494.27  922.38   504.6  921.23  661.35  931.87   701.1  935.82  793.75   937.4
   832.8  940.74   861.5  941.54  904.13   944.7  997.27  946.94 1048.59  951.77
#Mann= 3 , 0 , 0
       0     .08       0     420     .05       0  473.76     .08       0
#XS Ineff= 2 , 0
                          493.12          926.33
Permanent Ineff=
       F       F
Bank Sta=420,473.76
Exp/Cntr=0.5,0.3

Type RM Length L Ch R = 1 ,1417.58 ,93.3,99.96,107.39
XS GIS Cut Line= 5
  1353655.758162   772345.266086  1353397.647931   772397.763064
   1353087.32785    772579.23327  1352791.745203   772599.001523
  1352400.205131   772636.186905
#Sta/Elev= 30
       0   958.6   55.38  960.86    94.6  958.41  140.43  961.81  184.28   959.8
  227.67  954.96  254.15   956.6   342.4  954.19  374.88  951.63  411.02  945.23
  467.07  944.21   520.6  932.97  666.12  927.85  679.36  925.57  693.44  918.08
   703.7  912.85  721.96  912.03  753.99  915.87  759.41  919.04  767.05   923.5
  867.14  928.44   903.9     916  927.52  914.35  964.33  925.59 1038.74  929.69
 1099.23   949.9 1151.27  957.06 1205.97  958.02 1264.55  961.95 1312.43  961.88
#Mann= 3 , 0 , 0
       0     .08       0  693.44     .05       0  759.41     .08       0
#XS Ineff= 2 , 0
       0     680   924.7  771.36       0     925
Permanent Ineff=
       F       F
Bank Sta=693.44,759.41
Exp/Cntr=0.5,0.3

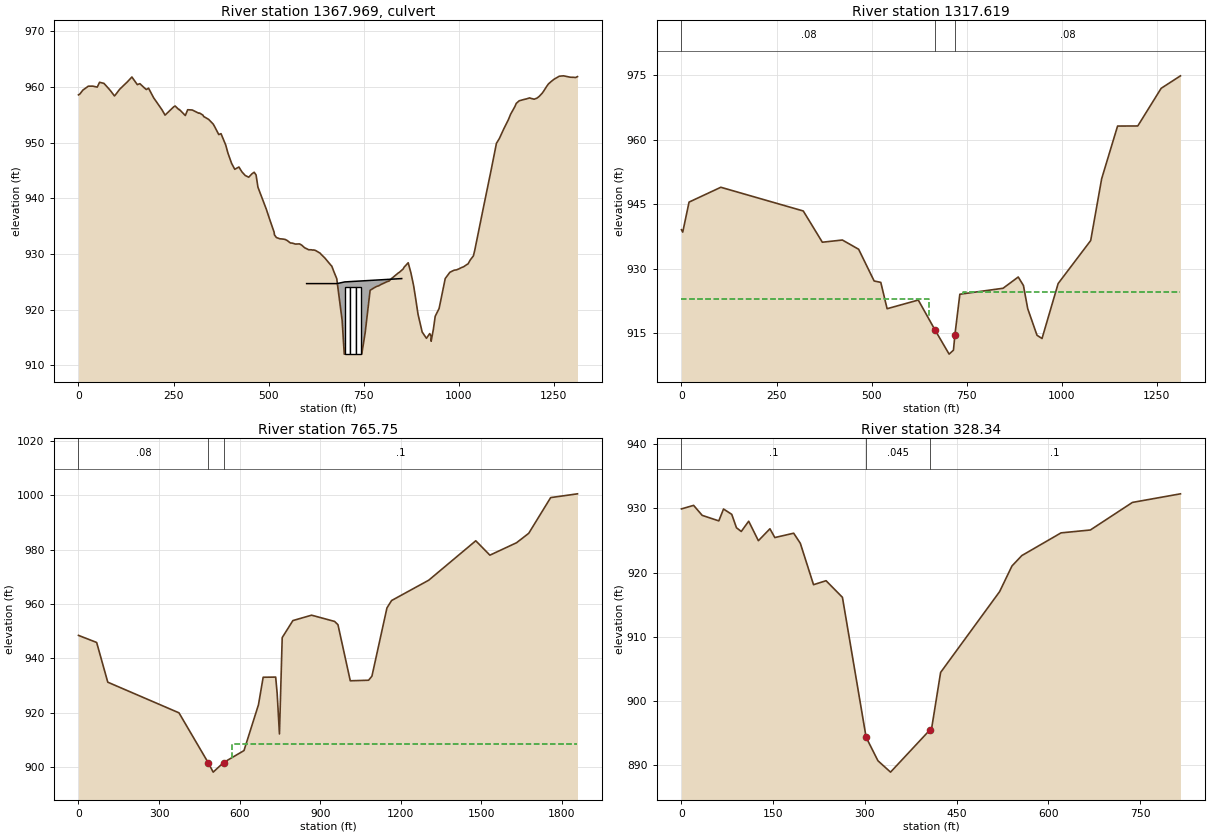
Type RM Length L Ch R = 2 ,1367.969,,,
BEGIN DESCRIPTION:
Millersville Road, SR 1610;  37003-0090
END DESCRIPTION:
Bridge Culvert--1,0,-1,-1, 0
Deck Dist Width WeirC Skew NumUp NumDn MinLoCord MaxHiCord MaxSubmerge Is_Ogee
28,50,2.6,0, 4, 4, , , 0.95, 0, 0,0,,
     600     680     700     850
   924.7   924.7     925   925.6
                                
     500     650     672     800
   924.7   924.7     925   925.6
                                
BR Coef=-1 , 0 , 0 ,, 0 ,,,0.8,-1,,0,
WSPro=,,,, 1 ,,,, 0 ,,,, 0 ,,,,-1 ,-1 ,-1 , 0 , 0 , 0 , 0 , 0
Multiple Barrel Culv=2,12,14,60,0.013,0.4,1,8,1,912.03,910.11, 3,Culvert #1  , 0 ,25
     707     679     722     694     737     709
Culvert Bottom n=0.013
BR U #Sta/Elev= 190
       0   958.6    3.59  958.75   11.51  959.45   25.73  960.16   25.84  960.16
    36.6  960.18   37.54  960.17   49.36  959.99   55.38  960.86   67.03  960.66
   80.52  959.64   85.49  959.23    94.6  958.41   97.03  958.59  108.48  959.62
  128.48  960.93  140.43  961.81  154.68  960.44  161.48  960.61  172.74  959.89
  178.46  959.56  184.28   959.8  197.52  958.09  219.69  955.91  227.67  954.96
  250.26  956.44  254.15   956.6  263.39  955.99  263.46  955.99  264.51  955.96
  265.11  955.98  265.66  955.95  281.01  954.89  287.18  955.93  299.35  955.88
  316.38   955.3   318.4  955.34  327.54  954.95  329.26   954.7  330.92  954.65
   342.4  954.19   354.8  953.32  355.91  953.14  356.47  953.11  368.97  951.47
  374.88  951.63   387.3  949.58  393.01  948.15  402.68   946.3  411.02  945.23
  421.88  945.64  429.98  944.76  438.53  944.12  447.74  943.81  456.09  944.41
  462.04   944.7  467.07  944.21  471.96  942.02  494.02  938.06  502.56  936.29
  514.49  933.94  515.39  933.46   520.6  932.97  529.54  932.75  538.84  932.69
  543.95  932.62  549.11  932.43  557.54  931.99  561.79  931.98  570.58   931.8
  581.24  931.83  583.37  931.76  587.45  931.59  594.64  931.14  599.99  930.97
  605.22  930.78   612.5  930.77  616.57  930.72  618.41  930.74  622.88  930.67
  635.43  930.17  637.56     930  647.35  929.34  647.93   929.3  648.06  929.29
  664.57  927.94  666.12  927.85  671.27  926.92  679.36  925.57   681.2  924.52
  693.44  918.08     699  912.03   703.7  912.03  713.93  912.03  721.96  912.03
  729.96  912.03  737.05  912.03  737.14  912.03     745  912.03  753.99  915.87
  754.08  915.91  766.92  923.47  767.05   923.5  780.03  924.04  784.48   924.2
  789.64   924.3  795.64  924.54  813.07  925.09  816.61  925.14  825.47  925.74
   826.2  925.76  841.75  926.65  843.48   926.7  853.89  927.33  856.49  927.65
  867.14  928.44  874.11  926.69  881.29  924.38   885.7   922.5  893.04  919.19
  902.61  916.32   903.9     916  915.18  914.87  919.12  915.27  923.75  915.72
  927.36  915.26  927.52  914.35  933.42   916.5  938.17  918.82  946.49  919.99
  948.48  920.24  964.27  925.57  964.33  925.59  964.58  925.61  976.16  926.68
  976.36  926.72  976.74  926.73  988.05  927.11  993.93  927.16  1000.8  927.35
 1006.99  927.57 1012.88  927.72 1021.19  928.11 1023.21  928.18 1024.63  928.24
 1030.21  928.93 1038.74  929.69 1042.26   930.7 1056.54  935.56 1058.05   936.1
 1063.28  937.79 1067.46  939.17 1068.68  939.57 1081.44  943.83 1085.95  945.32
 1099.23   949.9 1106.78  950.74 1116.52  952.19 1118.43  952.47 1130.56  954.13
 1136.66  955.14 1147.91  956.52 1151.27  957.06 1158.17   957.5 1159.25  957.55
 1159.77  957.55 1175.32  957.84 1176.54  957.84 1186.54  958.06    1189  957.99
  1198.5  957.82 1205.97  958.02 1211.29   958.3 1219.35  958.88 1223.55  959.28
 1230.66  960.05    1234  960.36 1235.95  960.56 1243.23     961 1248.51  961.28
 1250.86  961.41 1264.55  961.95 1275.48  962.02 1276.99     962 1277.37  961.99
 1290.29  961.82  1293.6  961.77 1303.28  961.75 1307.26  961.71 1312.43  961.88
BR U #Mann= 3
       0      .1  693.44    .045  753.99      .1
BR U Banks=693.44,753.99
BR D #Sta/Elev= 193
       0  939.06    3.37  938.51   19.99   945.5   22.71  945.56   27.98  945.85
   41.83   946.1    45.4  946.55   48.28  946.58   57.24  947.11   59.93  947.26
   60.81  947.43   61.65  947.44   81.17  947.35   81.75  947.41   82.97   947.4
   90.83  948.47  103.56  948.95  115.72  948.42  121.05  948.12  126.56   947.9
  129.24  948.25  147.13  948.37  152.98  947.87  161.79  947.92  172.68  947.41
  178.41  946.39  183.23  946.96  193.26  946.31  196.41  946.02  212.11   945.9
  217.35  945.76  224.28   946.1  231.51  945.42  235.45  945.37  245.81  944.63
  250.57  944.38   252.3  944.35  263.39  943.86  264.11   943.9  265.33  943.91
  277.97   944.3  284.05     944   291.3  943.41  303.81  943.73  304.48  943.68
  305.82  943.72  320.39  943.43  331.04  942.64  337.32  941.73  341.87  940.77
  354.11  938.59   370.2   936.2  370.55  936.16   370.8  936.15  381.89  935.73
  390.48   936.1  393.59  936.13  397.93  936.18  407.96  936.62   414.2   936.7
  423.27  936.67  437.01  936.15  437.95  936.12  439.31  936.04  451.92  935.32
  461.05  934.88  466.02  934.52  468.62  934.14  479.47  932.82  488.72  931.57
  492.41  931.14  499.52  929.66  506.74  927.14  520.68  927.04  524.27  926.81
  526.25   926.3  540.89  920.68  552.18  921.64  558.18  921.43  566.02  921.98
  573.34  922.54  580.13  921.73  586.88  921.39   594.4  920.83  600.77  921.38
  603.98  921.16   614.1  922.16  622.88   922.7  624.87   922.4  626.72     922
  627.65  921.94  629.27  921.48  638.56  918.94  648.49  918.56  655.73  917.94
  661.28  917.76  667.43  915.65  667.48     915     670  910.11  691.68  910.11
  692.42  910.11  703.97  910.11  705.49  910.11     717  910.11  719.24  914.63
  732.17  924.05  739.83   924.3  743.79  924.36  750.52  924.59  755.98  924.69
  762.22  924.87  774.16  925.27  777.31  925.43  786.91   925.6  803.27   925.6
  804.81  925.58  812.66  925.49   816.2  925.44  816.73  925.35  817.74  925.43
  828.11  925.34  833.47  925.46  842.26  925.44  845.84  925.44  860.47  926.16
  863.12  926.28  863.46   926.3  864.21  926.36  872.46   926.9   876.3  927.32
  885.76  928.06  893.79  927.25  899.47  926.08  904.97  923.57  910.71  920.69
  921.36  917.78  922.07  917.55  922.49  917.45  935.19  914.49  935.39  914.48
  948.33  913.75  949.11  913.98  955.52  915.51  959.42   917.7  967.01  918.91
  978.06  921.95  985.07  924.42  990.73  926.54  996.91   927.6 1001.69  928.24
 1014.46  929.53 1015.87  929.66 1027.39   931.1 1028.44  931.21 1030.18   931.4
 1039.42  932.73 1044.92  933.19 1053.64  934.16 1058.72  934.76 1072.51   935.8
 1076.31  936.55    1083  940.37 1088.01  942.97 1094.63  946.51  1105.2  950.95
 1109.36  952.48 1117.46  954.91 1120.54  955.92 1129.05  958.66 1133.21  960.01
 1134.76  960.48 1147.04   963.2 1150.95  963.17 1164.78  962.88 1169.99   962.8
 1177.03   962.8 1187.26  962.75  1193.4  962.87 1200.17  963.22 1205.96  963.82
 1211.72  964.59 1222.46  966.34 1225.12  966.66 1235.97  968.29 1237.77   968.6
 1240.95  969.16  1253.2  971.09  1257.5  971.42 1259.88  971.77 1261.61  971.98
 1264.67  972.19 1292.99  973.85 1312.43  974.89
BR D #Mann= 3
       0      .1  667.48    .045  719.24      .1
BR D Banks=667.48,719.24
BC Design=,, 0 ,, 0 ,,,,,,

Type RM Length L Ch R = 1 ,1317.619,536.74,551.87,564
XS GIS Cut Line= 5
  1353666.089184   772257.252704  1353407.978953   772309.749681
  1353097.658871   772491.219887  1352802.076224    772510.98814
  1352410.536153   772548.173522
#Sta/Elev= 30
       0  939.06    3.37  938.51   19.99   945.5  103.56  948.95  320.39  943.43
  370.55  936.16  423.27  936.67  466.02  934.52  506.74  927.14  524.27  926.81
  540.89  920.68  622.88   922.7  667.43  915.65  703.97  910.11   715.4  911.04
  719.24  914.63  732.17  924.05  845.84  925.44  885.76  928.06  899.47  926.08
  910.71  920.69  935.19  914.49  948.33  913.75  990.73  926.54 1076.31  936.55
  1105.2  950.95 1147.04   963.2 1200.17  963.22 1261.61  971.98 1312.43  974.89
#Mann= 3 , 0 , 0
       0     .08       0  667.43     .05       0  719.24     .08       0
#XS Ineff= 2 , 0
       0     650     923     741       0   924.5
Permanent Ineff=
       F       F
Bank Sta=667.43,719.24
Exp/Cntr=0.5,0.3

Type RM Length L Ch R = 1 ,765.75  ,430,437.41,450
XS GIS Cut Line= 4
  1353841.079108   772202.568329  1353554.533038   772169.757695
  1353193.616249   772031.953106  1352084.617349   772445.366918
#Sta/Elev= 30
       0  948.48   67.64  945.87  109.07  931.24  374.15  919.96  483.19  901.57
  501.61  898.12  540.16  901.64  616.33  906.06  670.22  922.93  687.75  933.06
   734.3  933.12  739.85  927.14  748.38  912.18  758.63  947.66   798.4  953.93
  868.09  955.92  953.66  953.62  966.29  952.41 1012.16  931.76 1080.23  931.96
 1092.76  933.46 1148.68  958.59 1165.95  961.31 1304.42  968.81  1479.5  983.32
 1532.11  978.02 1631.19  982.59  1676.7  986.07 1758.34  999.22  1858.3 1000.61
#Mann= 3 , 0 , 0
       0     .08       0  483.19     .05       0  540.16      .1       0
#XS Ineff= 2 , 0
       0                  571.22       0  908.61
Permanent Ineff=
       F       F
Bank Sta=483.19,540.16
Exp/Cntr=0.3,0.1

Type RM Length L Ch R = 1 ,328.34  ,324,328.34,332
XS GIS Cut Line= 4
   1353884.04656   772018.797477  1353638.284781   771781.119951
  1353465.281415   771711.595277  1353192.033141   771802.139063
#Sta/Elev= 30
       0  929.93   19.89  930.48   33.93  928.92   61.09  928.06   68.82  929.91
   82.28  929.08   89.98  926.99   97.83  926.41  109.96  928.01  125.84  924.97
  144.74  926.83  152.71  925.46  183.55  926.14  194.41  924.57  216.03  918.11
   236.5  918.73   263.3  916.14  302.05  894.31  321.41  890.65  341.99  888.88
  405.88  895.41  408.75  895.43   423.9  904.43   520.4  917.03   540.6  921.03
   556.7  922.65  620.84  926.19  668.83  926.64  737.63  930.94   816.2  932.28
#Mann= 3 , 0 , 0
       0      .1       0  302.05    .045       0  405.88      .1       0
Bank Sta=302.05,405.88
Exp/Cntr=0.3,0.1
Stream Node=GladeCreek      ,Main            , 0 , 0 ,Upstream end
Stream Node=GladeCreek      ,Main            , 0 , 1 ,Downstream end

Chan Stop Cuts=-1
Use User Specified Reach Order=0
User Specified Reach Order=GladeCreek      ,Main