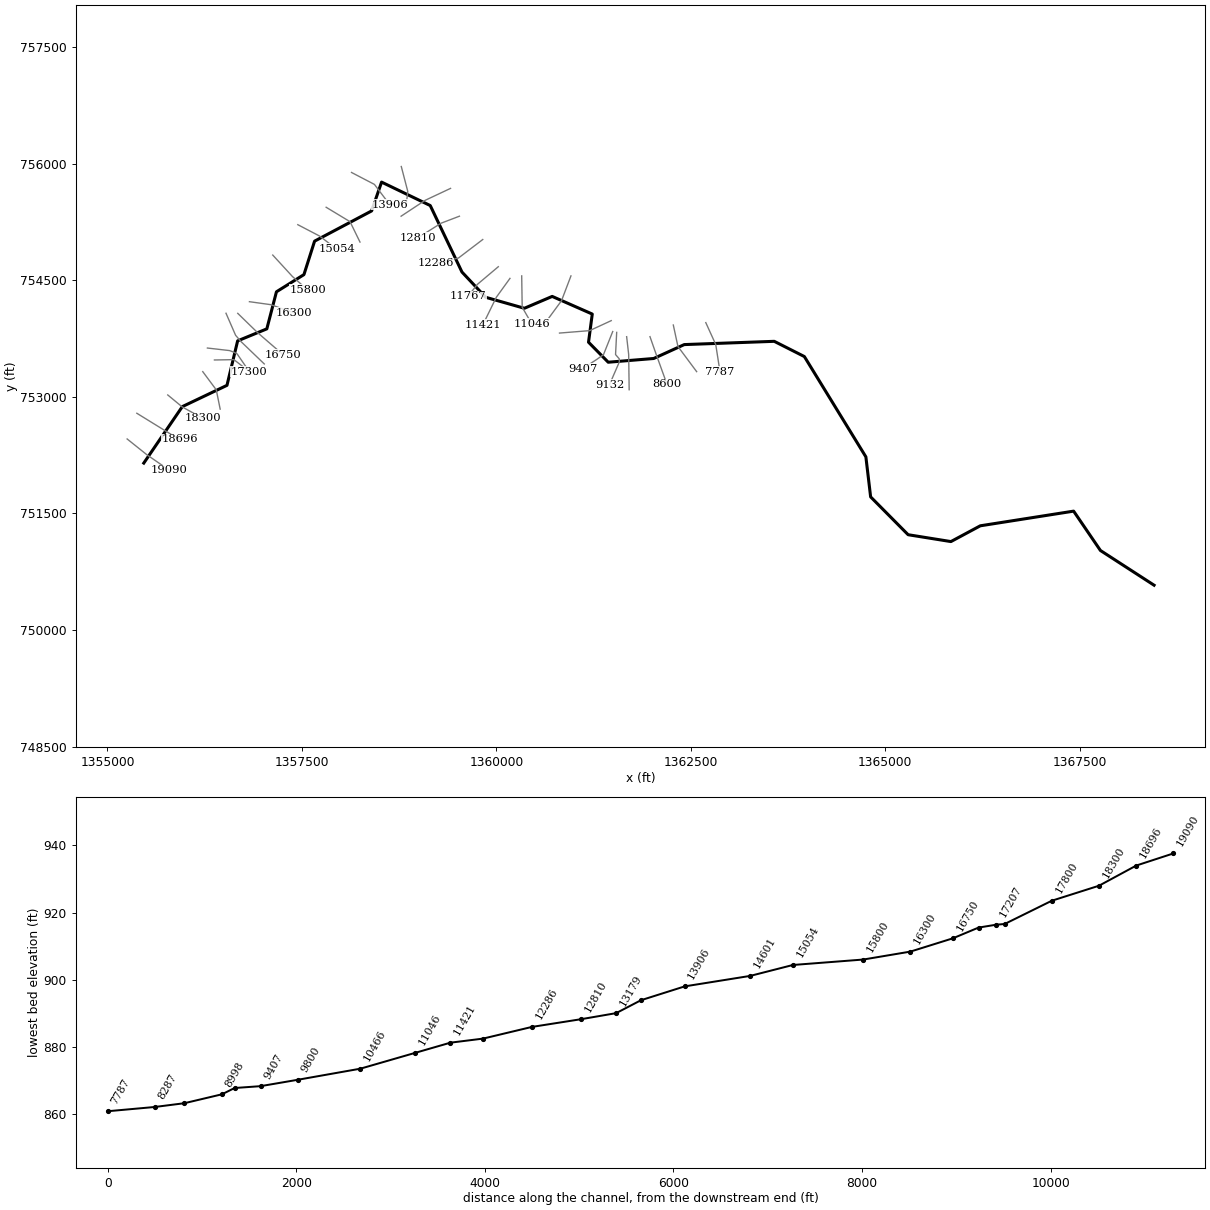
--- Elk Shoal Creek.prj (project) ---

Proj Title=Elk Shoal Creek Detailed Study
Current Plan=p02
Default Exp/Contr=0.3,0.1
English Units
Geom File=g01
Flow File=f01
Flow File=f02
Plan File=p01
Plan File=p02
Y Axis Title=Elevation
X Axis Title(PF)=Main Channel Distance
X Axis Title(XS)=Station
BEGIN DESCRIPTION:
Elk Shoal Creek
END DESCRIPTION:
DSS Export Rating Curves= 0
DSS Export Rating Curve Sorted= 0
DSS Export Volume Flow Curves= 0
DXF OffsetX= 0
DXF OffsetY= 0
DXF ScaleX= 1
DXF ScaleY= 10

--- Elk Shoal Creek.p02 (plan) ---

Plan Title=Floodway Run
Program Version=3.12
Short Identifier=Floodway
Geom File=g01
Flow File=f02
Subcritical Flow
K Sum by GR= 0
Std Step Tol= 0.01
Critical Tol= 0.01
Num of Std Step Trials= 20
Max Error Tol= 0.3
Flow Tol Ratio= 0.001
Split Flow NTrial= 30
Split Flow Tol= 0.02
Split Flow Ratio= 0.02
Log Output Level= 0
Friction Slope Method= 1
Unsteady Friction Slope Method= 2
Unsteady Bridges Friction Slope Method= 1
Parabolic Critical Depth
Global Vel Dist= 0 , 0 , 0
Global Log Level= 0
CheckData=True
Encroach Param=-1 ,0,0, 2
Encroach River=Elk Shoal Creek
Encroach Reach=Reach-1
Encroach Node=19090
       1    4992    5009
Encroach Node=18696
       1    4992    5009
Encroach Node=18300
       1    4992    5009
Encroach Node=17800
       1    4992    5009
Encroach Node=17300
       1    4982    5009
Encroach Node=17207
       1    4978    5011
Encroach Node=17023
       1    4978    5011
Encroach Node=16750
       1    4990    5015
Encroach Node=16300
       1    4990    5012
Encroach Node=15800
       1    4990    5012
Encroach Node=15054
       1    4990    5012
Encroach Node=14601
       1    4990    5015
Encroach Node=13906
       1    4990    5015
Encroach Node=13442
       1    4990    5010
Encroach Node=13179
       1    4985    5015
Encroach Node=12810
       1    4990    5010
Encroach Node=12286
       1    4975  5010.6
Encroach Node=11767
       1    4985    5020
Encroach Node=11421
       1    4980    5015
Encroach Node=11046
       1    4980    5015
Encroach Node=10466
       1    4985    5010
Encroach Node=9800
       1    4980    5040
Encroach Node=9407
       1    4985    5050
Encroach Node=9132
       1    4975    5030
Encroach Node=8998
       1    4975    5030
Encroach Node=8600
       1    4975    5055
Encroach Node=8287
       1    4975    5055
Encroach Node=7787
       1    4970    5040
Encroach Node=7304
       1    4985    5040
Encroach Node=6817
       1    4985    5050
Encroach Node=6202
       1    4982    5020
Encroach Node=5824
       1    4977    5035
Encroach Node=5409
       1    4991    5008
Encroach Node=5001
       1    4973    5030
Encroach Node=4398
       1    4975    5060
Encroach Node=4034
       1    4990    5010
Encroach Node=3554
       1    4985    5020
Encroach Node=3000
       1    4972    5020
Encroach Node=2579
       1    4965    5040
Encroach Node=2374
       1    4964    5025
Encroach Node=2206
       1    4964    5025
Encroach Node=2000
       1    4968    5025
Encroach Node=1640
       1    4965    5020
Encroach Node=946
       1    4952    5020
Encroach Node=418
       1  4958.7    5033
BEGIN DESCRIPTION:
Floodway Run
END DESCRIPTION:
Computation Interval=1HOUR
Output Interval=1HOUR
Run HTab= 0
Run UNet= 0
Run PostProcess= 0
UNET Theta= 1
UNET Theta Warmup= 1
UNET ZTol= 0.02
UNET ZSATol= 0.05
UNET MxIter= 20
UNET MaxInSteps= 0
UNET DtIC= 0
UNET DtMin= 0
UNET MaxCRTS= 20
UNET WFStab= 2
UNET SFStab= 1
UNET WFX= 1
UNET SFX= 1
UNET DSS MLevel= 4
UNET DZMax Abort= 100
UNET Convert EG Bridges=-1
UNET Use Existing IB Tables=-1
UNET Froude Reduction=False
UNET Froude Limit= 1
UNET Froude Power= 10
Instantaneous Interval=1HOUR
Write IC File= 0
Echo Input=False
Echo Output=False
Write Detailed= 0
Detailed Automatic Start=False, 10

--- Elk Shoal Creek.p01 (plan) ---

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Plan Title=Multiple Run
Short Identifier=Multiple
Geom File= g01
Flow File= f01
Encroach Param= -1, 0, 0, 0
Multiple Run

--- Elk Shoal Creek.f02 (steady flow) ---

Flow Title=Floodway
Number of Profiles=2
Profile Names=100-year,100-FW
River Rch & RM= Elk Shoal Creek,Reach-1,19090
     483     483
River Rch & RM= Elk Shoal Creek,Reach-1,18300
     572     572
River Rch & RM= Elk Shoal Creek,Reach-1,17023
    1024    1024
River Rch & RM= Elk Shoal Creek,Reach-1,11767
    1206    1206
River Rch & RM= Elk Shoal Creek,Reach-1,9800
    1299    1299
River Rch & RM= Elk Shoal Creek,Reach-1,6817
    1375    1375
River Rch & RM= Elk Shoal Creek,Reach-1,3554
    2116    2116
Boundary for River Rch & Prof#=Elk Shoal Creek,Reach-1,1
Up Type=0
Dn Type=3
Dn Slope=0.001
Boundary for River Rch & Prof#=Elk Shoal Creek,Reach-1,2
Up Type=0
Dn Type=3
Dn Slope=0.001

--- Elk Shoal Creek.f01 (steady flow) ---

Flow Title=Multiple
Number of Profiles=4
Profile Names=10-year,50-year,100-year,500-year
River Rch & RM= Elk Shoal Creek,Reach-1,19090
     211     387     483     762
River Rch & RM= Elk Shoal Creek,Reach-1,18300
     253     460     572     899
River Rch & RM= Elk Shoal Creek,Reach-1,17023
     468     831    1024    1578
River Rch & RM= Elk Shoal Creek,Reach-1,11767
     556     982    1206    1850
River Rch & RM= Elk Shoal Creek,Reach-1,9800
     602    1059    1299    1986
River Rch & RM= Elk Shoal Creek,Reach-1,6817
     639    1122    1375    2100
River Rch & RM= Elk Shoal Creek,Reach-1,3554
    1009    1738    2116    3186
Boundary for River Rch & Prof#=Elk Shoal Creek,Reach-1,1
Up Type=0
Dn Type=3
Dn Slope=0.001
Boundary for River Rch & Prof#=Elk Shoal Creek,Reach-1,2
Up Type=0
Dn Type=3
Dn Slope=0.001
Boundary for River Rch & Prof#=Elk Shoal Creek,Reach-1,3
Up Type=0
Dn Type=3
Dn Slope=0.001
Boundary for River Rch & Prof#=Elk Shoal Creek,Reach-1,4
Up Type=0
Dn Type=3
Dn Slope=0.001

--- Elk Shoal Creek.g01 (geometry) ---

Geom Title=Existing Conditions

River Reach=Elk Shoal Creek,Reach-1
Reach XY= 30
      1355466.78       752148.33      1355962.13       752874.94
      1356536.38       753148.81      1356673.38       753720.88
      1357048.75       753875.44      1357172.50       754352.50
      1357525.88       754573.38      1357662.75       755004.06
      1358396.00       755392.75      1358524.13       755763.81
      1359149.87       755462.14      1359557.75       754606.50
      1359862.50       754281.81      1360360.00       754140.19
      1360717.88       754292.94      1361233.00       754065.94
      1361184.88       753703.69      1361438.13       753446.19
      1362023.00       753494.19      1362415.75       753673.13
      1363572.71       753715.08      1363959.98       753519.15
      1364750.88       752228.44      1364812.00       751713.44
      1365293.95       751226.75      1365844.33       751138.48
      1366221.92       751341.40      1367422.00       751530.13
      1367766.75       751023.81      1368456.25       750577.13

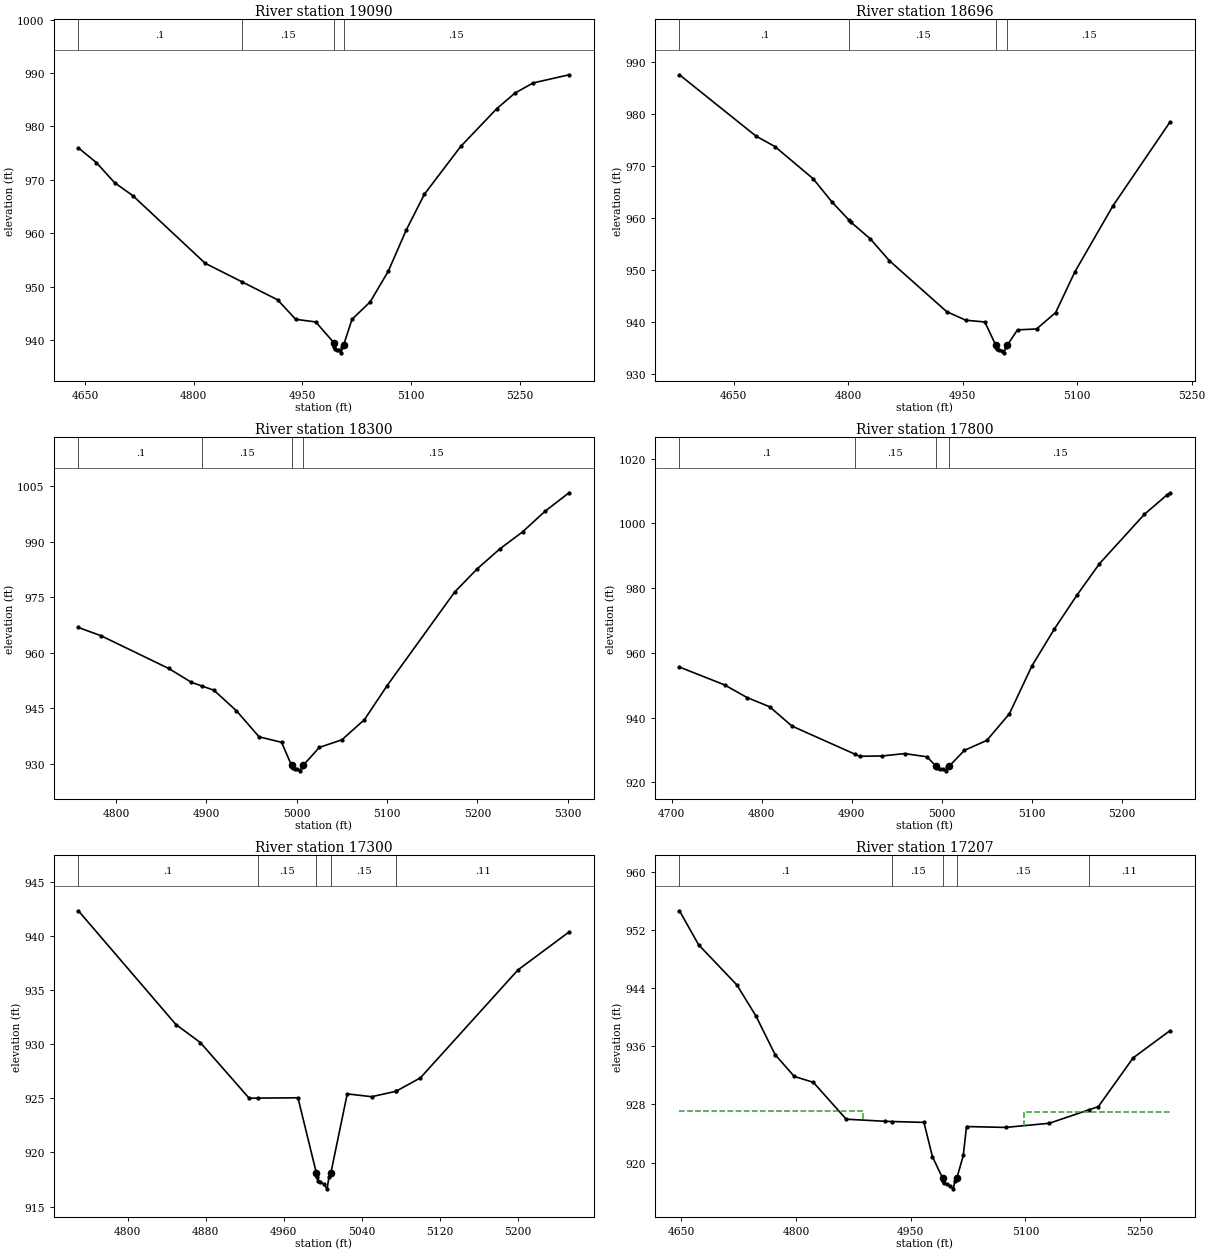
Type RM Length L Ch R = 1,19090,394,394,394
BEGIN DESCRIPTION:
Elk Shoal Creek 38.0
END DESCRIPTION:
XS GIS Cut Line= 3
      1355252.76       752458.78      1355508.64       752254.07
      1355796.52       752055.76
#Sta/Elev= 28
  4641.0  975.99  4666.0  973.22  4691.0  969.47  4716.0  967.07  4816.0  954.40
  4866.8  950.93  4916.0  947.56  4941.0  943.91  4968.7  943.42  4993.7  939.52
  4994.3  939.09  4994.5  938.71  4995.7  938.41  4997.9  938.25  5000.8  938.08
  5003.9  937.64  5005.5  938.69  5007.1  939.09  5018.7  943.92  5043.7  947.15
  5068.7  952.89  5093.7  960.66  5118.7  967.33  5168.7  976.25  5218.7  983.35
  5243.7  986.25  5268.7  988.14  5318.3  989.67
#Mann=4,-1,0
  4641.0     0.1       0  4866.8    0.15       0  4993.7   0.046       0
  5007.1    0.15       0
Bank Sta=4993.7,5007.1
XS Rating Curve= 0
Exp/Cntr=0.3,0.1

Type RM Length L Ch R = 1,18696,396,396,396
BEGIN DESCRIPTION:
Elk Shoal Creek 37.5
END DESCRIPTION:
XS GIS Cut Line= 3
      1355377.41       752789.51      1355733.01       752570.15
      1355924.66       752452.39
#Sta/Elev= 26
  4579.0  987.62  4679.0  975.83  4704.0  973.79  4754.0  967.60  4779.0  963.07
  4801.4  959.57  4804.0  959.16  4829.0  955.99  4854.0  951.79  4929.0  941.97
  4954.0  940.32  4979.0  939.98  4993.4  935.48  4993.8  935.10  4995.1  934.80
  4997.6  934.64  5000.9  934.47  5004.4  934.03  5006.2  935.08  5008.2  935.48
  5021.8  938.46  5046.8  938.63  5071.8  941.80  5096.8  949.60  5146.8  962.36
  5221.7  978.55
#Mann=4,-1,0
  4579.0     0.1       0  4801.4    0.15       0  4993.4   0.046       0
  5008.2    0.15       0
Bank Sta=4993.4,5008.2
XS Rating Curve= 0
Exp/Cntr=0.3,0.1

Type RM Length L Ch R = 1,18300,500,500,500
BEGIN DESCRIPTION:
Elk Shoal Creek 37.0
END DESCRIPTION:
XS GIS Cut Line= 3
      1355775.00       753025.00      1355961.20       752870.93
      1356225.00       752725.00
#Sta/Elev= 27
  4758.3  966.80  4783.3  964.57  4858.3  955.71  4883.3  951.98  4895.5  950.93
  4908.3  949.83  4933.3  944.27  4958.3  937.23  4983.3  935.73  4994.3  929.47
  4994.5  929.09  4995.7  928.79  4997.9  928.63  5000.8  928.46  5003.9  928.02
  5005.5  929.07  5007.1  929.47  5025.0  934.35  5050.0  936.41  5075.0  941.87
  5100.0  951.04  5175.0  976.42  5200.0  982.70  5225.0  988.08  5250.0  992.65
  5275.0  998.26  5301.5 1003.24
#Mann=4,-1,0
  4758.3     0.1       0  4895.5    0.15       0  4994.3   0.046       0
  5007.1    0.15       0
Bank Sta=4994.3,5007.1
XS Rating Curve= 0
Exp/Cntr=0.3,0.1

Type RM Length L Ch R = 1,17800,500,500,500
BEGIN DESCRIPTION:
Elk Shoal Creek 36.0
END DESCRIPTION:
XS GIS Cut Line= 3
      1356225.00       753325.00      1356398.59       753091.05
      1356449.02       752842.61
#Sta/Elev= 28
  4708.7  955.60  4758.7  950.11  4783.7  946.20  4808.7  943.36  4833.7  937.37
  4903.1  928.76  4908.7  928.06  4933.7  928.15  4958.7  928.89  4983.7  927.88
  4993.4  925.01  4993.8  924.63  4995.1  924.33  4997.6  924.17  5000.9  924.00
  5004.4  923.56  5006.2  924.61  5008.2  925.01  5025.0  929.87  5050.0  932.97
  5075.0  941.16  5100.0  955.94  5125.0  967.37  5150.0  977.79  5175.0  987.51
  5225.0 1002.79  5250.0 1008.75  5253.5 1009.42
#Mann=4,-1,0
  4708.7     0.1       0  4903.1    0.15       0  4993.4   0.047       0
  5008.2    0.15       0
Bank Sta=4993.4,5008.2
XS Rating Curve= 0
Exp/Cntr=0.3,0.1

Type RM Length L Ch R = 1,17300,93,93,93
BEGIN DESCRIPTION:
Elk Shoal Creek 35.0
END DESCRIPTION:
XS GIS Cut Line= 3
      1356375.00       753475.00      1356625.50       753479.41
      1356825.00       753325.00
#Sta/Elev= 21
  4749.5  942.32  4849.5  931.81  4874.5  930.15  4924.5  925.01  4933.7  925.02
  4974.5  925.05  4993.4  918.09  4993.8  917.71  4995.1  917.41  4997.6  917.25
  5000.9  917.08  5004.4  916.64  5006.2  917.69  5008.2  918.09  5025.0  925.41
  5050.0  925.15  5075.0  925.65  5075.2  925.66  5100.0  926.89  5200.0  936.86
  5252.3  940.36
#Mann=5,-1,0
  4749.5     0.1       0  4933.7    0.15       0  4993.4   0.047       0
  5008.2    0.15       0  5075.2    0.11       0
Bank Sta=4993.4,5008.2
XS Rating Curve= 0
Exp/Cntr=0.5,0.3

Type RM Length L Ch R = 1,17207,184,184,184
BEGIN DESCRIPTION:
Elk Shoal Creek 34.2
END DESCRIPTION:
XS GIS Cut Line= 5
      1356284.76       753628.72      1356570.22       753595.93
      1356630.02       753572.78      1356666.67       753553.49
      1356807.47       753349.04
#Sta/Elev= 28
  4647.8  954.62  4672.8  949.95  4722.8  944.43  4747.8  940.15  4772.8  934.85
  4797.8  931.86  4822.8  931.04  4865.7  925.98  4916.9  925.69  4926.0  925.66
  4967.3  925.54  4978.4  920.82  4991.8  917.86  4992.2  917.48  4993.9  917.18
  4997.0  917.02  5001.1  916.85  5005.5  916.41  5007.8  917.46  5010.2  917.86
  5018.7  921.00  5022.9  924.97  5074.0  924.85  5131.0  925.42  5182.4  927.25
  5195.2  927.71  5240.7  934.41  5289.0  938.16
#Mann=5,-1,0
  4647.8     0.1       0  4926.0    0.15       0  4991.8   0.047       0
  5010.2    0.15       0  5182.4    0.11       0
#XS Ineff=2,0
    0.00 4887.70  927.17 5098.40    0.00  926.99
Bank Sta=4991.8,5010.2
XS Rating Curve= 0
Exp/Cntr=0.5,0.3

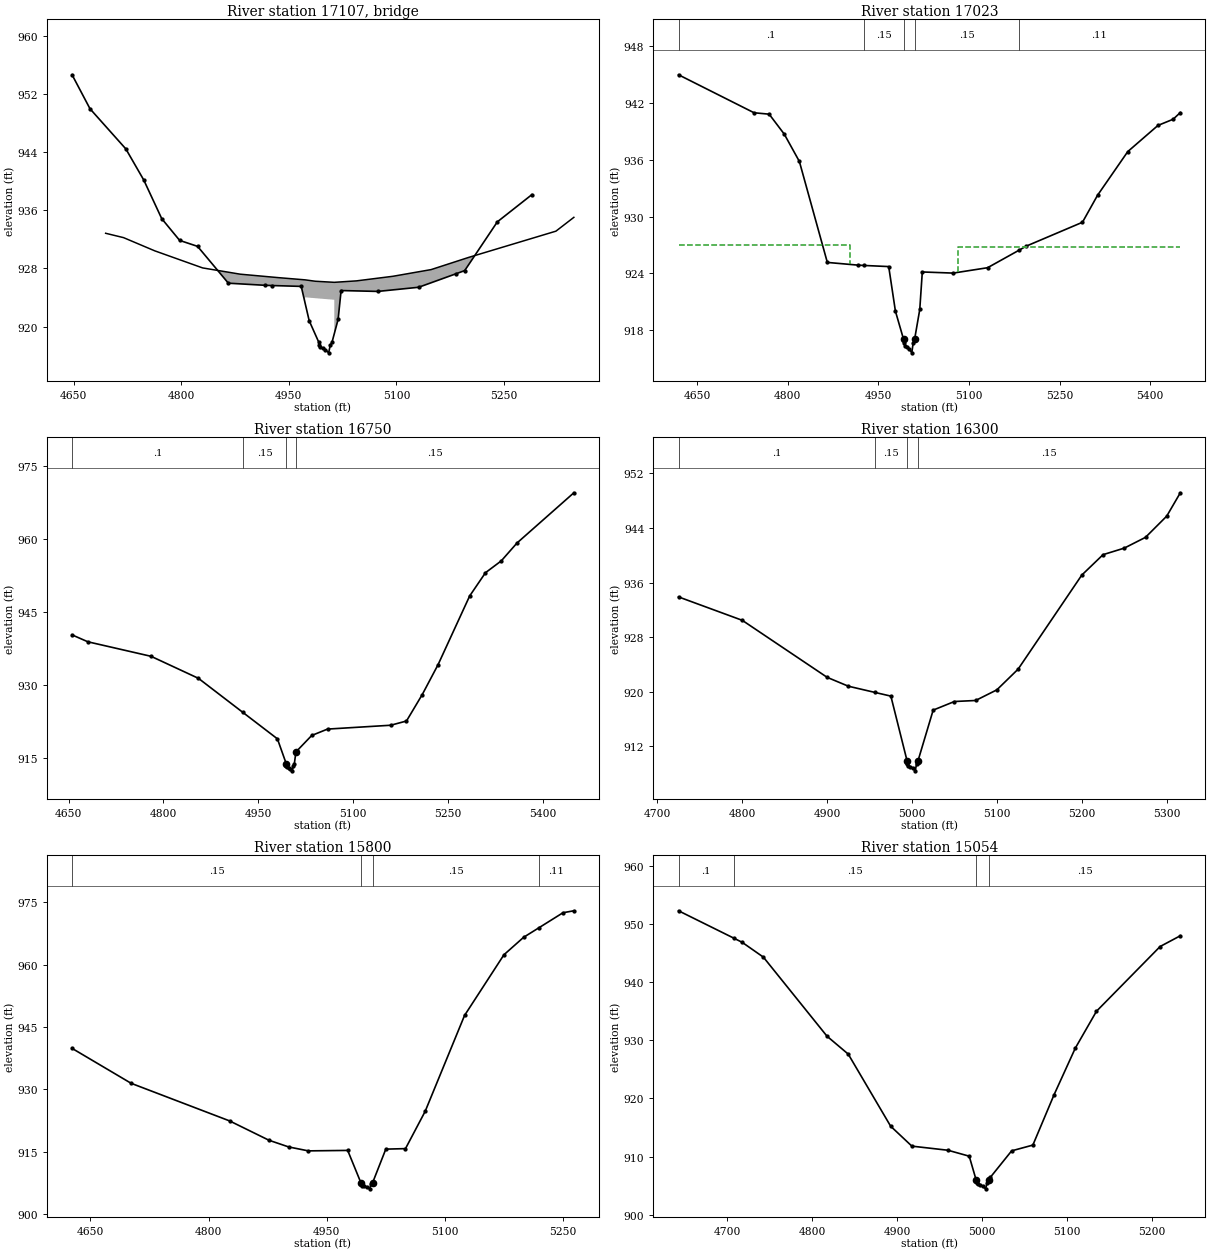
Type RM Length L Ch R =3,17107,,,
BEGIN DESCRIPTION:
ESC-3-TOR
Structure ID: UC_ESC_04
Detailed Survey Structure
END DESCRIPTION:
Bridge Culvert--1,0,-1,-1,0
Deck Dist Width WeirC Skew NumUp NumDn MinLoCord MaxHiCord MaxSubmerge Is_Ogee
85,30,3,,17,17,,,,0,1,1,,,
  4694.6  4719.6  4763.0  4829.8  4882.2  4934.8  4972.7  4972.7  4986.8  5013.4
  5013.4  5044.3  5095.1  5148.4  5200.9  5322.4  5347.4
  932.84  932.24  930.43  928.08  927.22  926.75  926.44  926.44  926.25  926.10
  926.10  926.30  926.93  927.85  929.53  933.13  935.03
  896.41  896.41  896.41  896.41  896.41  896.41  896.41  924.04  923.92  923.70
  896.41  896.41  896.41  896.41  896.41  896.41  896.41
  4694.6  4719.6  4763.0  4829.8  4882.2  4934.8  4972.7  4972.7  4986.8  5013.4
  5013.4  5044.3  5095.1  5148.4  5200.9  5322.4  5347.4
  932.84  932.24  930.43  928.08  927.22  926.75  926.44  926.44  926.25  926.10
  926.10  926.30  926.93  927.85  929.53  933.13  935.03
  896.41  896.41  896.41  896.41  896.41  896.41  896.41  924.04  923.92  923.70
  896.41  896.41  896.41  896.41  896.41  896.41  896.41
Abutment Skew #Up #Dn=,2,2
  4972.7  4978.4
  924.04  920.82
  4972.7  4978.4
  924.04  921.39
BR Coef=1,1,0,1.25,0,,,0.8,0,2,0,
WSPro=,,,, 1 ,,,, 0 ,,,, 0 ,,,,-1 ,-1 ,-1 , 0 , 0 , 0 , 0 , 0
BC Design=,,0,,0,,,,,,

Type RM Length L Ch R = 1,17023,273,273,273
BEGIN DESCRIPTION:
Elk Shoal Creek 34.1
END DESCRIPTION:
XS GIS Cut Line= 4
      1356523.93       754076.20      1356647.38       753792.67
      1356718.74       753709.73      1357015.78       753424.26
#Sta/Elev= 30
  4619.4  945.00  4744.4  940.98  4769.4  940.83  4794.4  938.72  4819.4  935.83
  4865.7  925.14  4916.9  924.85  4926.0  924.82  4967.3  924.70  4978.4  919.98
  4991.8  917.02  4992.2  916.64  4993.9  916.34  4997.0  916.18  5001.1  916.01
  5005.5  915.57  5007.8  916.62  5010.2  917.02  5018.7  920.16  5022.9  924.13
  5074.0  924.01  5131.0  924.58  5182.4  926.41  5195.2  926.87  5288.0  929.39
  5313.0  932.25  5363.0  936.87  5413.0  939.64  5438.0  940.29  5450.0  941.00
#Mann=5,-1,0
  4619.4     0.1       0  4926.0    0.15       0  4991.8   0.047       0
  5010.2    0.15       0  5182.4    0.11       0
#XS Ineff=2,0
    0.00 4903.70  927.03 5082.40    0.00  926.77
Bank Sta=4991.8,5010.2
XS Rating Curve= 0
Exp/Cntr=0.5,0.3

Type RM Length L Ch R = 1,16750,450,450,450
BEGIN DESCRIPTION:
Elk Shoal Creek 34.0
END DESCRIPTION:
XS GIS Cut Line= 3
      1356675.00       754075.00      1356928.81       753827.77
      1357261.46       753539.90
#Sta/Elev= 26
  4655.3  940.28  4680.3  938.86  4780.3  935.88  4855.3  931.36  4925.4  924.39
  4980.3  918.94  4994.3  913.82  4994.5  913.44  4995.7  913.14  4997.9  912.98
  5000.8  912.81  5003.9  912.37  5005.5  913.42  5007.1  913.82  5009.6  916.25
  5034.6  919.63  5059.6  920.94  5159.6  921.73  5184.6  922.60  5209.6  928.04
  5234.6  934.17  5284.6  948.27  5309.6  953.04  5334.6  955.47  5359.6  959.15
  5449.5  969.45
#Mann=4,-1,0
  4655.3     0.1       0  4925.4    0.15       0  4994.3   0.047       0
  5009.6    0.15       0
Bank Sta=4994.3,5009.6
XS Rating Curve= 0
Exp/Cntr=0.3,0.1

Type RM Length L Ch R = 1,16300,500,500,500
BEGIN DESCRIPTION:
Elk Shoal Creek 33.0
END DESCRIPTION:
XS GIS Cut Line= 3
      1356825.00       754225.00      1357097.17       754187.07
      1357395.80       754083.65
#Sta/Elev= 25
  4725.2  933.91  4800.2  930.48  4900.2  922.12  4925.2  920.82  4956.5  919.91
  4975.2  919.37  4994.3  909.87  4994.5  909.49  4995.7  909.19  4997.9  909.03
  5000.8  908.86  5003.9  908.42  5005.5  909.47  5007.1  909.87  5025.0  917.32
  5050.0  918.58  5075.0  918.73  5100.0  920.29  5125.0  923.32  5200.0  937.11
  5225.0  940.10  5250.0  941.06  5275.0  942.64  5300.0  945.75  5316.0  949.17
#Mann=4,-1,0
  4725.2     0.1       0  4956.5    0.15       0  4994.3   0.047       0
  5007.1    0.15       0
Bank Sta=4994.3,5007.1
XS Rating Curve= 0
Exp/Cntr=0.3,0.1

Type RM Length L Ch R = 1,15800,746,746,746
BEGIN DESCRIPTION:
Elk Shoal Creek 32.0
END DESCRIPTION:
XS GIS Cut Line= 3
      1357125.00       754825.00      1357377.37       754549.75
      1357575.00       754375.00
#Sta/Elev= 24
  4626.6  939.84  4701.6  931.44  4826.6  922.40  4876.6  917.75  4901.6  916.14
  4926.6  915.19  4976.6  915.30  4993.4  907.51  4993.8  907.13  4995.1  906.83
  4997.6  906.67  5000.9  906.50  5004.4  906.06  5006.2  907.11  5008.2  907.51
  5025.0  915.61  5050.0  915.73  5075.0  924.70  5125.0  947.76  5175.0  962.35
  5200.0  966.55  5218.9  968.78  5250.0  972.46  5263.8  972.93
#Mann=4,-1,0
  4626.6    0.15       0  4993.4   0.047       0  5008.2    0.15       0
  5218.9    0.11       0
Bank Sta=4993.4,5008.2
XS Rating Curve= 0
Exp/Cntr=0.3,0.1

Type RM Length L Ch R = 1,15054,453,453,453
BEGIN DESCRIPTION:
Elk Shoal Creek 31.0
END DESCRIPTION:
XS GIS Cut Line= 3
      1357446.98       755215.95      1357728.45       755068.81
      1357945.96       754902.49
#Sta/Elev= 26
  4642.5  952.30  4707.9  947.57  4717.5  946.87  4742.5  944.32  4817.5  930.71
  4842.5  927.63  4892.5  915.22  4917.5  911.79  4960.1  911.08  4985.1  910.06
  4993.4  905.89  4993.8  905.51  4995.1  905.21  4997.6  905.05  5000.9  904.88
  5004.4  904.44  5006.2  905.49  5008.2  905.89  5010.1  906.44  5035.1  910.98
  5060.1  911.97  5085.1  920.64  5110.1  928.65  5135.1  935.01  5210.1  946.15
  5233.9  948.00
#Mann=4,-1,0
  4642.5     0.1       0  4707.9    0.15       0  4993.4   0.047       0
  5008.2    0.15       0
Bank Sta=4993.4,5008.2
XS Rating Curve= 0
Exp/Cntr=0.3,0.1

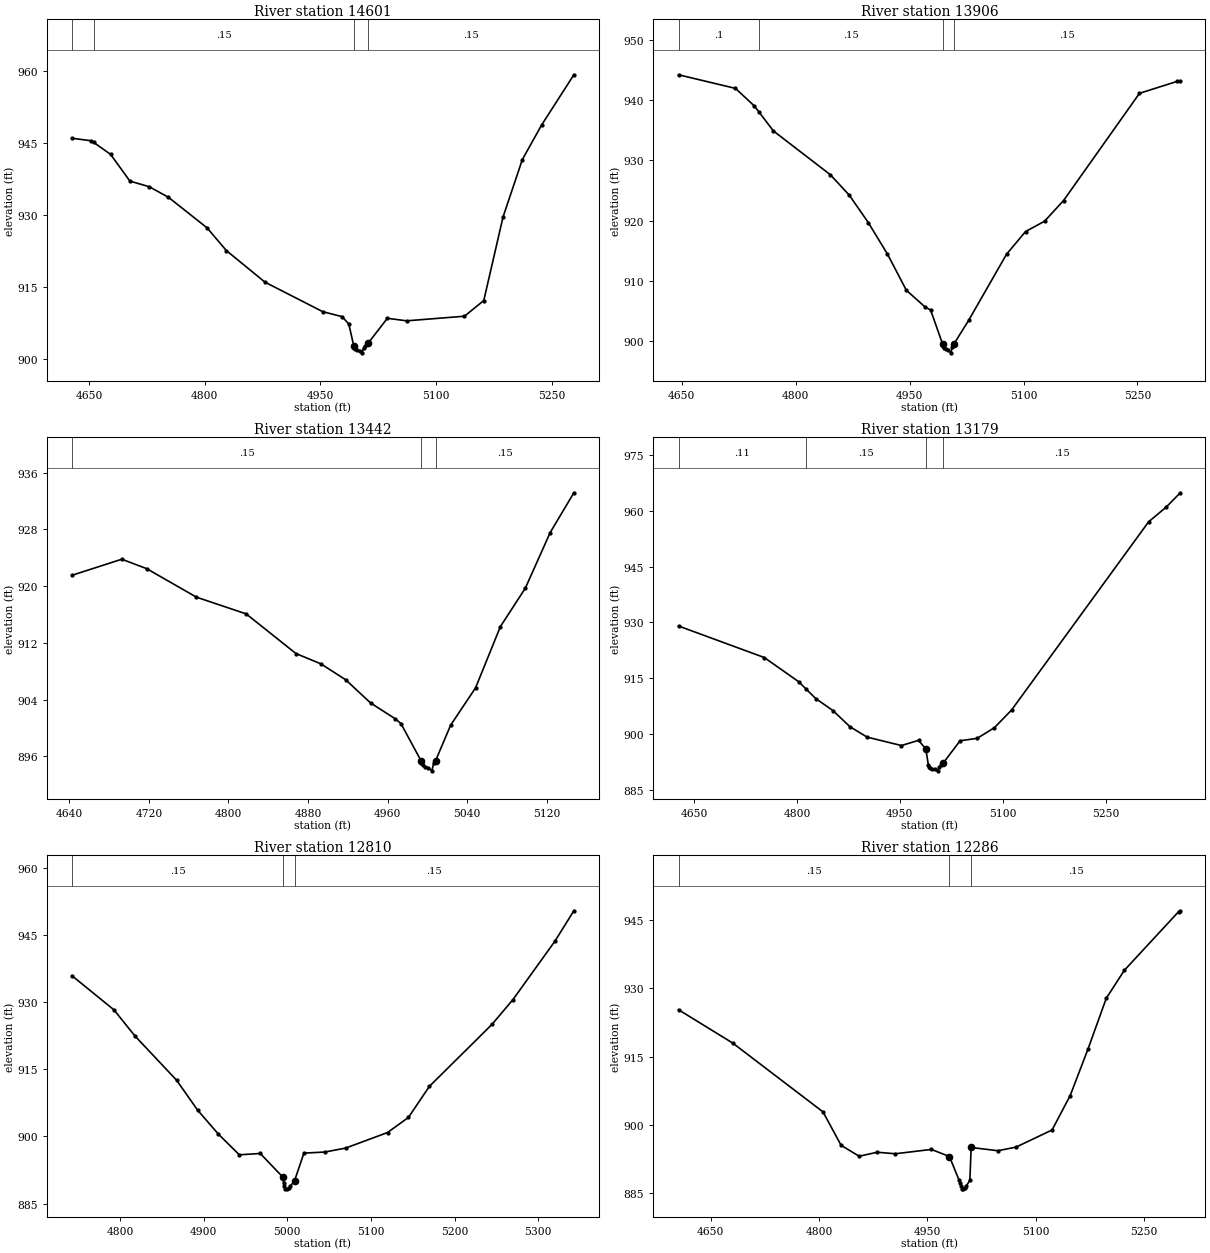
Type RM Length L Ch R = 1,14601,695,695,695
BEGIN DESCRIPTION:
Elk Shoal Creek 30.0
END DESCRIPTION:
XS GIS Cut Line= 3
      1357811.62       755439.85      1358118.68       755254.33
      1358246.62       754992.05
#Sta/Elev= 30
  4628.2  945.90  4653.2  945.38  4656.0  945.06  4678.2  942.54  4703.2  936.97
  4728.2  935.81  4753.2  933.60  4803.2  927.24  4828.2  922.51  4878.2  915.93
  4953.2  909.77  4978.2  908.73  4987.0  907.21  4993.4  902.64  4993.8  902.26
  4995.1  901.96  4997.6  901.80  5000.9  901.63  5004.4  901.19  5006.2  902.24
  5008.2  902.64  5012.0  903.19  5037.0  908.39  5062.0  907.86  5137.0  908.82
  5162.0  912.09  5187.0  929.51  5212.0  941.46  5237.0  948.67  5278.8  959.13
#Mann=4,-1,0
  4628.2     0.1       0  4656.0    0.15       0  4993.4   0.047       0
  5012.0    0.15       0
Bank Sta=4993.4,5012
XS Rating Curve= 0
Exp/Cntr=0.3,0.1

Type RM Length L Ch R = 1,13906,464,464,464
BEGIN DESCRIPTION:
Elk Shoal Creek 29.0
END DESCRIPTION:
XS GIS Cut Line= 3
      1358137.87       755887.65      1358432.14       755734.12
      1358630.45       755471.83
#Sta/Elev= 28
  4645.7  944.22  4720.7  941.96  4745.7  939.02  4752.1  937.96  4770.7  934.89
  4845.7  927.62  4870.7  924.21  4895.7  919.66  4920.7  914.48  4945.7  908.45
  4970.7  905.64  4977.6  905.18  4993.4  899.52  4993.8  899.14  4995.1  898.84
  4997.6  898.68  5000.9  898.51  5004.4  898.07  5006.2  899.12  5008.2  899.52
  5027.6  903.44  5077.6  914.44  5102.6  918.20  5127.6  919.91  5152.6  923.34
  5252.6  941.14  5302.6  943.14  5306.4  943.11
#Mann=4,-1,0
  4645.7     0.1       0  4752.1    0.15       0  4993.4   0.047       0
  5008.2    0.15       0
Bank Sta=4993.4,5008.2
XS Rating Curve= 0
Exp/Cntr=0.3,0.1

Type RM Length L Ch R = 1,13442,263,263,263
BEGIN DESCRIPTION:
Elk Shoal Creek 28.0
END DESCRIPTION:
XS GIS Cut Line= 3
      1358777.58       755964.41      1358860.75       755644.56
      1358841.56       755471.83
#Sta/Elev= 25
  4642.8  921.53  4692.8  923.79  4717.8  922.46  4767.8  918.44  4817.8  916.08
  4867.8  910.49  4892.8  909.04  4917.8  906.79  4942.8  903.52  4967.8  901.27
  4973.3  900.62  4993.4  895.40  4993.8  895.02  4995.1  894.72  4997.6  894.56
  5000.9  894.39  5004.4  893.95  5006.2  895.00  5008.2  895.40  5023.3  900.40
  5048.3  905.65  5073.3  914.30  5098.3  919.70  5123.3  927.55  5147.1  933.16
#Mann=3,-1,0
  4642.8    0.15       0  4993.4   0.047       0  5008.2    0.15       0
Bank Sta=4993.4,5008.2
XS Rating Curve= 0
Exp/Cntr=0.3,0.1

Type RM Length L Ch R = 1,13179,369,369,369
BEGIN DESCRIPTION:
Elk Shoal Creek 27.0
END DESCRIPTION:
XS GIS Cut Line= 3
      1359410.90       755682.94      1359084.65       755529.41
      1358775.00       755325.00
#Sta/Elev= 27
  4627.4  929.03  4752.4  920.56  4802.4  914.08  4813.6  912.05  4827.4  909.54
  4852.4  906.32  4877.4  901.96  4902.4  899.17  4952.4  896.91  4977.4  898.31
  4987.9  895.98  4991.8  891.56  4992.2  891.18  4993.9  890.88  4997.0  890.72
  5001.1  890.55  5005.5  890.11  5007.8  891.16  5010.2  891.56  5012.9  892.11
  5037.9  898.19  5062.9  898.85  5087.9  901.70  5112.9  906.44  5312.9  957.06
  5337.9  960.90  5359.0  964.83
#Mann=4,-1,0
  4627.4    0.11       0  4813.6    0.15       0  4987.9   0.047       0
  5012.9    0.15       0
Bank Sta=4987.9,5012.9
XS Rating Curve= 0
Exp/Cntr=0.3,0.1

Type RM Length L Ch R = 1,12810,524,524,524
BEGIN DESCRIPTION:
Elk Shoal Creek 26.0
END DESCRIPTION:
XS GIS Cut Line= 3
      1359525.00       755325.00      1359289.36       755235.14
      1358995.09       755049.62
#Sta/Elev= 26
  4742.7  935.85  4792.7  928.27  4817.7  922.47  4867.7  912.55  4892.7  905.91
  4917.7  900.52  4942.7  895.91  4967.7  896.21  4994.9  890.90  4995.6  889.59
  4996.5  888.89  4997.9  888.32  4999.5  888.38  5002.6  888.50  5003.6  888.88
  5008.8  890.17  5019.9  896.29  5044.9  896.53  5069.9  897.42  5119.9  900.88
  5144.9  904.25  5169.9  911.17  5244.9  925.03  5269.9  930.55  5319.9  943.53
  5342.7  950.36
#Mann=3,-1,0
  4742.7    0.15       0  4994.9   0.047       0  5008.8    0.15       0
Bank Sta=4994.9,5008.8
XS Rating Curve= 0
Exp/Cntr=0.3,0.1

Type RM Length L Ch R = 1,12286,519,519,519
BEGIN DESCRIPTION:
Elk Shoal Creek 25.0
END DESCRIPTION:
XS GIS Cut Line= 3
      1359825.00       755025.00      1359513.26       754787.34
      1359218.99       754716.97
#Sta/Elev= 27
  4605.6  925.26  4680.6  917.96  4805.6  902.87  4830.6  895.55  4855.6  893.16
  4880.6  894.03  4905.6  893.70  4955.6  894.65  4980.6  893.08  4993.6  888.01
  4995.6  887.28  4996.5  886.58  4997.9  886.01  4999.5  886.07  5002.6  886.19
  5003.6  886.57  5008.8  887.86  5010.6  895.08  5047.6  894.36  5072.6  895.15
  5122.6  898.91  5147.6  906.43  5172.6  916.76  5197.6  927.77  5222.6  933.90
  5297.6  946.73  5300.1  946.95
#Mann=3,-1,0
  4605.6    0.15       0  4980.6   0.047       0  5010.6    0.15       0
Bank Sta=4980.6,5010.6
XS Rating Curve= 0
Exp/Cntr=0.3,0.1

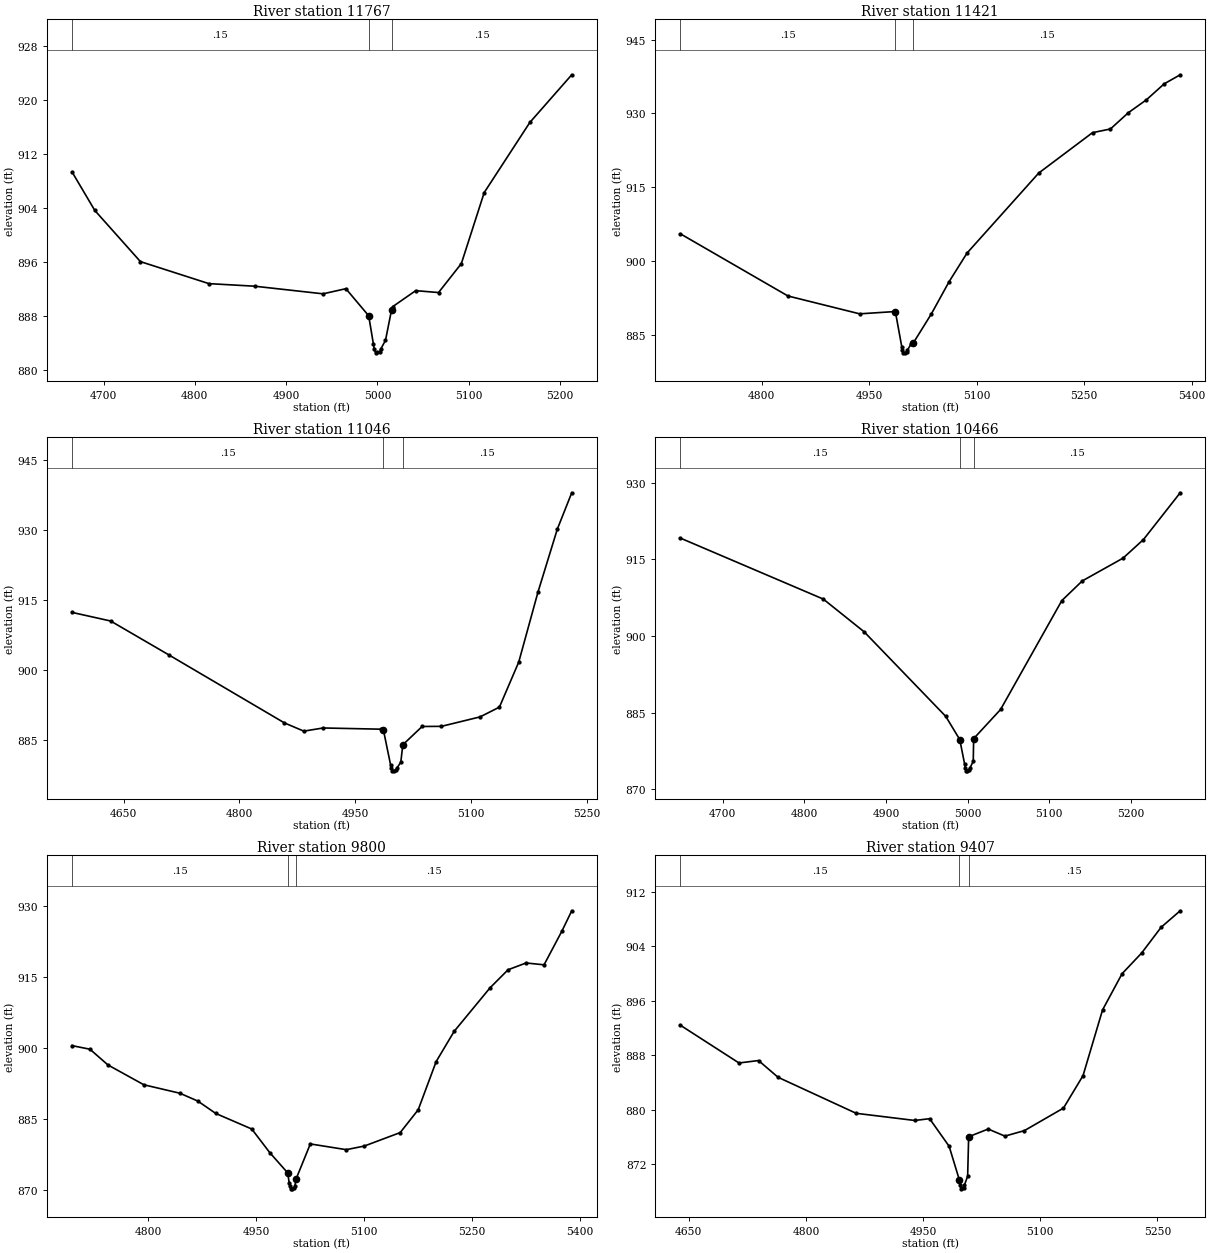
Type RM Length L Ch R = 1,11767,346,346,346
BEGIN DESCRIPTION:
Elk Shoal Creek 24.0
END DESCRIPTION:
XS GIS Cut Line= 3
      1360025.00       754675.00      1359756.35       754448.29
      1359634.80       754294.76
#Sta/Elev= 23
  4665.4  909.34  4690.4  903.62  4740.4  896.04  4815.4  892.78  4865.4  892.40
  4940.4  891.27  4965.4  892.03  4990.4  888.02  4995.6  883.80  4996.5  883.10
  4997.9  882.53  4999.5  882.59  5002.6  882.71  5003.6  883.09  5008.8  884.38
  5015.4  888.86  5016.9  889.39  5041.9  891.74  5066.9  891.46  5091.9  895.75
  5116.9  906.26  5166.9  916.65  5212.8  923.71
#Mann=3,-1,0
  4665.4    0.15       0  4990.4   0.047       0  5015.4    0.15       0
Bank Sta=4990.4,5015.4
XS Rating Curve= 0
Exp/Cntr=0.3,0.1

Type RM Length L Ch R = 1,11421,375,375,375
BEGIN DESCRIPTION:
Elk Shoal Creek 23.0
END DESCRIPTION:
XS GIS Cut Line= 3
      1360175.00       754525.00      1359999.44       754281.96
      1359825.00       753925.00
#Sta/Elev= 22
  4686.9  905.52  4836.9  892.88  4936.9  889.25  4986.7  889.72  4995.6  882.59
  4996.5  881.89  4997.9  881.32  4999.5  881.38  5002.6  881.50  5003.6  881.88
  5008.8  883.17  5011.7  883.32  5036.7  889.18  5061.7  895.80  5086.7  901.61
  5186.7  917.88  5261.7  926.09  5286.7  926.84  5311.7  930.15  5336.7  932.75
  5361.7  936.02  5384.0  937.86
#Mann=3,-1,0
  4686.9    0.15       0  4986.7   0.047       0  5011.7    0.15       0
Bank Sta=4986.7,5011.7
XS Rating Curve= 0
Exp/Cntr=0.3,0.1

Type RM Length L Ch R = 1,11046,580,580,580
BEGIN DESCRIPTION:
Elk Shoal Creek 22.0
END DESCRIPTION:
XS GIS Cut Line= 3
      1360325.69       754557.04      1360332.09       754154.02
      1360453.64       753942.92
#Sta/Elev= 24
  4583.3  912.29  4633.3  910.44  4708.3  903.20  4858.3  888.56  4883.3  886.80
  4908.3  887.48  4983.3  887.22  4986.4  886.97  4995.6  879.55  4996.5  878.85
  4997.9  878.28  4999.5  878.34  5002.6  878.46  5003.6  878.84  5008.8  880.13
  5011.4  883.87  5036.4  887.80  5061.4  887.83  5111.4  889.86  5136.4  891.95
  5161.4  901.62  5186.4  916.70  5211.4  930.19  5230.0  937.96
#Mann=3,-1,0
  4583.3    0.15       0  4986.4   0.047       0  5011.4    0.15       0
Bank Sta=4986.4,5011.4
XS Rating Curve= 0
Exp/Cntr=0.3,0.1

Type RM Length L Ch R = 1,10466,666,666,666
BEGIN DESCRIPTION:
Elk Shoal Creek 21.0
END DESCRIPTION:
XS GIS Cut Line= 3
      1360959.01       754557.04      1360837.46       754237.18
      1360677.54       754019.68
#Sta/Elev= 19
  4648.3  919.16  4823.3  907.22  4873.3  900.82  4973.3  884.25  4990.5  879.70
  4996.5  874.85  4997.2  874.15  4998.3  873.58  4999.6  873.64  5002.1  873.76
  5002.9  874.14  5007.0  875.43  5007.5  879.89  5040.5  885.60  5115.5  906.92
  5140.5  910.77  5190.5  915.24  5215.5  918.88  5260.5  928.04
#Mann=3,-1,0
  4648.3    0.15       0  4990.5   0.047       0  5007.5    0.15       0
Bank Sta=4990.5,5007.5
XS Rating Curve= 0
Exp/Cntr=0.3,0.1

Type RM Length L Ch R = 1,9800,393,393,393
BEGIN DESCRIPTION:
Elk Shoal Creek 20.0
END DESCRIPTION:
XS GIS Cut Line= 3
      1361477.18       753981.30      1361199.12       753852.61
      1360811.88       753821.37
#Sta/Elev= 30
  4693.6  900.51  4718.6  899.75  4743.6  896.43  4793.6  892.24  4843.6  890.46
  4868.6  888.80  4893.6  886.18  4943.6  882.90  4968.6  877.92  4993.6  873.63
  4995.6  871.54  4996.5  870.84  4997.9  870.27  4999.5  870.33  5002.6  870.45
  5003.6  870.83  5005.0  872.27  5025.0  879.75  5075.0  878.54  5100.0  879.30
  5150.0  882.15  5175.0  886.96  5200.0  897.15  5225.0  903.52  5275.0  912.73
  5300.0  916.53  5325.0  917.96  5350.0  917.57  5375.0  924.74  5388.5  928.98
#Mann=3,-1,0
  4693.6    0.15       0  4993.6   0.046       0  5005.0    0.15       0
Bank Sta=4993.6,5005
XS Rating Curve= 0
Exp/Cntr=0.3,0.1

Type RM Length L Ch R = 1,9407,275,275,275
BEGIN DESCRIPTION:
Elk Shoal Creek 19.5
END DESCRIPTION:
XS GIS Cut Line= 4
      1361496.00       753841.07      1361377.83       753544.73
      1361299.66       753488.37      1361112.40       753364.74
#Sta/Elev= 26
  4639.3  892.40  4714.3  886.86  4739.3  887.22  4764.3  884.76  4864.3  879.47
  4939.3  878.42  4958.3  878.68  4983.3  874.63  4996.5  869.65  4997.2  868.95
  4998.3  868.38  4999.6  868.44  5002.1  868.56  5002.9  868.94  5007.0  870.23
  5008.3  876.03  5033.3  877.16  5054.7  876.12  5079.7  876.93  5129.7  880.24
  5154.7  885.00  5179.7  894.65  5204.7  899.97  5229.7  903.00  5254.7  906.79
  5279.1  909.21
#Mann=3,-1,0
  4639.3    0.15       0  4996.5   0.046       0  5008.3    0.15       0
Bank Sta=4996.5,5008.3
XS Rating Curve= 0
Exp/Cntr=0.5,0.3

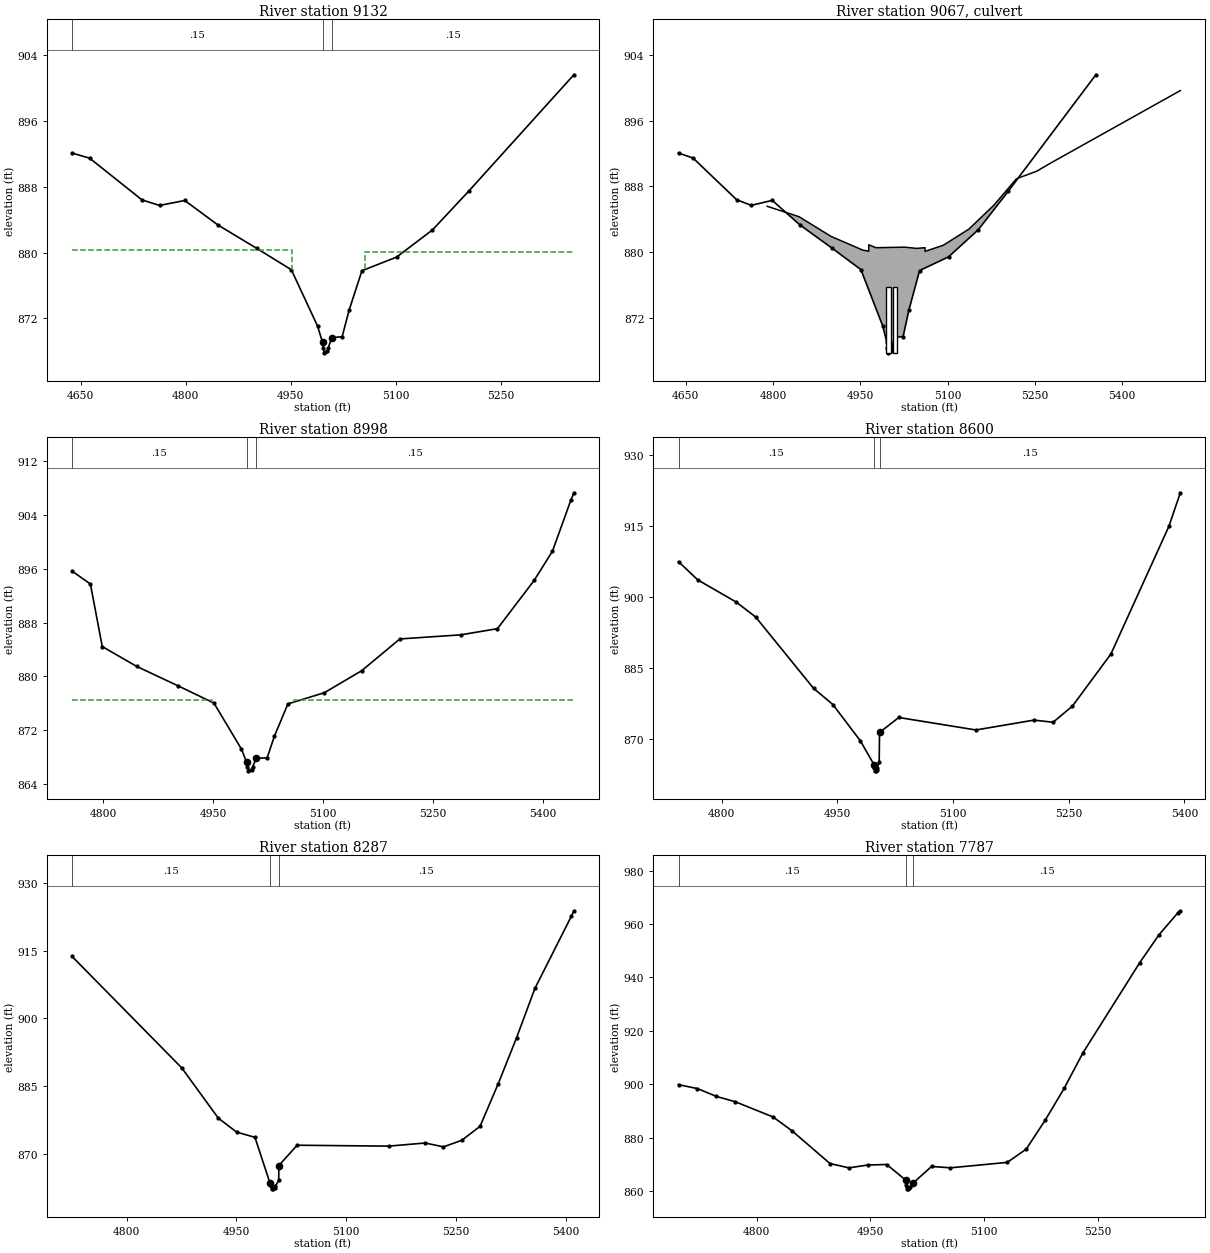
Type RM Length L Ch R = 1,9132,134,134,134
BEGIN DESCRIPTION:
Elk Shoal Creek 19.1
END DESCRIPTION:
XS GIS Cut Line= 5
      1361546.91       753830.16      1361532.36       753544.73
      1361579.63       753490.19      1361581.45       753450.19
      1361454.19       753157.48
#Sta/Elev= 23
  4637.6  892.06  4662.6  891.45  4737.6  886.38  4762.6  885.71  4798.7  886.31
  4845.9  883.35  4901.4  880.51  4951.0  877.91  4988.4  871.09  4995.6  869.10
  4996.5  868.40  4997.9  867.83  4999.5  867.89  5002.6  868.01  5003.6  868.39
  5008.8  869.68  5023.6  869.78  5033.5  872.99  5051.9  877.79  5101.6  879.45
  5152.7  882.74  5204.6  887.45  5354.8  901.56
#Mann=3,-1,0
  4637.6    0.15       0  4995.6   0.046       0  5008.8    0.15       0
#XS Ineff=2,0
    0.00 4951.80  880.35 5056.70    0.00  880.01
Bank Sta=4995.6,5008.8
XS Rating Curve= 0
Exp/Cntr=0.5,0.3

Type RM Length L Ch R =2,9067,,,
BEGIN DESCRIPTION:
ESC-2-TOR
Structure ID: UC_ESC_03
Detailed Survey Structure
END DESCRIPTION:
Bridge Culvert--1,0,-1,-1,0
Deck Dist Width WeirC Skew NumUp NumDn MinLoCord MaxHiCord MaxSubmerge Is_Ogee
43,44,3,,19,19,,,,0,1,1,,,
  4790.0  4844.7  4899.9  4954.1  4964.5  4964.5  4976.9  4989.1  5026.4  5047.1
  5061.2  5061.2  5092.6  5136.4  5179.5  5218.3  5253.1  5278.1  5500.0
  885.59  884.33  881.93  880.28  880.14  880.92  880.56  880.58  880.63  880.48
  880.57  880.12  880.86  882.81  885.72  888.93  889.85  890.88  899.64
  847.83  847.83  847.83  847.83  847.83  847.83  847.83  847.83  847.83  847.83
  847.83  847.83  847.83  847.83  847.83  847.83  847.83  847.83  847.83
  4790.0  4844.7  4899.9  4954.1  4964.5  4964.5  4976.9  4989.1  5026.4  5047.1
  5061.2  5061.2  5092.6  5136.4  5179.5  5218.3  5253.1  5278.1  5500.0
  885.59  884.33  881.93  880.28  880.14  880.92  880.56  880.58  880.63  880.48
  880.57  880.12  880.86  882.81  885.72  888.93  889.85  890.88  899.64
  847.62  847.62  847.62  847.62  847.62  847.62  847.62  847.62  847.62  847.62
  847.62  847.62  847.62  847.62  847.62  847.62  847.62  847.62  847.62
Culvert=2,8,7.5,44,0.015,0.4,1,8,1,867.8,4998.6,867.6,4998.6,Culvert #1,0,43
Culvert Bottom n=0.015
Culvert Bottom Depth=0
Culvert Depth Blocked=0
Culvert=2,8,7.5,44,0.015,0.4,1,8,1,867.8,5010,867.6,5010,Culvert #2,0,43
Culvert Bottom n=0.015
Culvert Bottom Depth=0
Culvert Depth Blocked=0
BC Design=,,0,,0,,,,,,

Type RM Length L Ch R = 1,8998,398,398,398
BEGIN DESCRIPTION:
Elk Shoal Creek 19.0
END DESCRIPTION:
XS GIS Cut Line= 3
      1361675.00       753775.00      1361701.08       753546.29
      1361707.48       753092.10
#Sta/Elev= 26
  4757.5  895.67  4782.5  893.75  4798.7  884.44  4845.9  881.48  4901.4  878.64
  4951.0  876.04  4988.4  869.22  4995.6  867.23  4996.5  866.53  4997.9  865.96
  4999.5  866.02  5002.6  866.14  5003.6  866.52  5008.8  867.81  5023.6  867.91
  5033.5  871.12  5051.9  875.92  5101.6  877.58  5152.7  880.87  5204.6  885.58
  5287.7  886.19  5337.7  887.11  5387.7  894.28  5412.7  898.63  5437.7  906.19
  5441.9  907.32
#Mann=3,-1,0
  4757.5    0.15       0  4995.6   0.046       0  5008.8    0.15       0
#XS Ineff=2,0
    0.00 4947.80  876.50 5060.70    0.00  876.50
Bank Sta=4995.6,5008.8
XS Rating Curve= 0
Exp/Cntr=0.5,0.3

Type RM Length L Ch R = 1,8600,313,313,313
BEGIN DESCRIPTION:
Elk Shoal Creek 18.0
END DESCRIPTION:
XS GIS Cut Line= 3
      1361975.00       753775.00      1362052.92       753552.69
      1362193.66       753162.46
#Sta/Elev= 23
  4744.3  907.42  4769.3  903.57  4819.3  898.88  4844.3  895.74  4919.3  880.71
  4944.3  877.30  4979.8  869.68  4997.8  864.58  4998.3  863.88  4999.0  863.31
  4999.8  863.37  5001.3  863.49  5001.8  863.87  5004.4  865.16  5004.8  871.40
  5029.8  874.56  5129.8  871.93  5204.8  874.00  5229.8  873.56  5254.8  876.95
  5304.8  887.97  5379.8  914.84  5394.7  921.95
#Mann=3,-1,0
  4744.3    0.15       0  4997.8   0.046       0  5004.8    0.15       0
Bank Sta=4997.8,5004.8
XS Rating Curve= 0
Exp/Cntr=0.3,0.1

Type RM Length L Ch R = 1,8287,500,500,500
BEGIN DESCRIPTION:
Elk Shoal Creek 17.0
END DESCRIPTION:
XS GIS Cut Line= 3
      1362275.00       753925.00      1362334.40       753648.65
      1362575.00       753325.00
#Sta/Elev= 24
  4725.4  913.71  4875.4  889.00  4925.4  877.85  4950.4  874.77  4975.4  873.61
  4996.0  863.46  4996.9  862.76  4998.1  862.19  4999.6  862.25  5002.3  862.37
  5003.2  862.75  5007.9  864.04  5008.1  867.36  5033.1  871.86  5158.1  871.66
  5208.1  872.35  5233.1  871.50  5258.1  872.94  5283.1  876.04  5308.1  885.53
  5333.1  895.70  5358.1  906.61  5408.1  922.67  5411.4  923.84
#Mann=3,-1,0
  4725.4    0.15       0  4996.0   0.046       0  5008.1    0.15       0
Bank Sta=4996,5008.1
XS Rating Curve= 0
Exp/Cntr=0.3,0.1

Type RM Length L Ch R = 1,7787,483,483,483
BEGIN DESCRIPTION:
Elk Shoal Creek 16.0
END DESCRIPTION:
XS GIS Cut Line= 3
      1362692.64       753955.71      1362820.58       753674.24
      1362875.00       753325.00
#Sta/Elev= 30
  4696.7  899.90  4721.7  898.42  4746.7  895.50  4771.7  893.49  4821.7  887.79
  4846.7  882.59  4896.7  870.38  4921.7  868.77  4946.7  869.84  4971.7  870.02
  4996.7  864.17  4997.4  862.19  4997.9  861.49  4998.7  860.92  4999.7  860.98
  5001.6  861.10  5002.2  861.48  5005.3  862.77  5005.8  862.92  5030.8  869.29
  5055.8  868.79  5130.8  870.82  5155.8  875.77  5180.8  886.56  5205.8  898.46
  5230.8  911.84  5305.8  945.58  5330.8  955.85  5355.8  964.12  5359.3  964.95
#Mann=3,-1,0
  4696.7    0.15       0  4996.7   0.046       0  5005.8    0.15       0
Bank Sta=4996.7,5005.8
XS Rating Curve= 0
Exp/Cntr=0.3,0.1