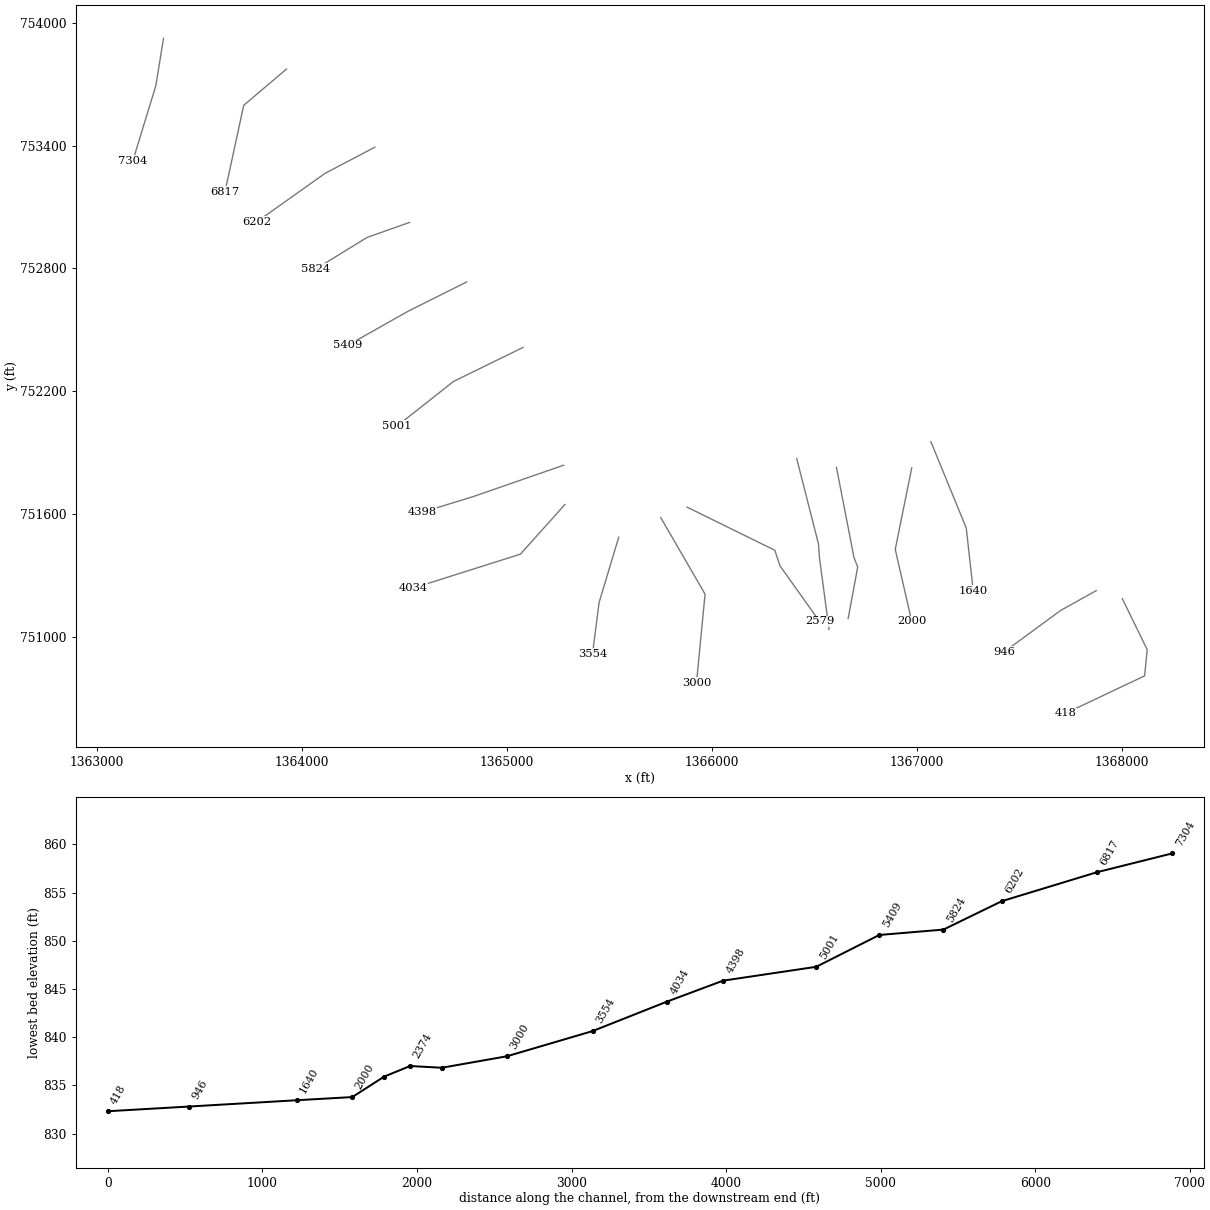
HEC-RAS study Elk Shoal Creek.prj: Elk Shoal Creek Detailed Study

--- Elk Shoal Creek.g01 (geometry) --- (continued)

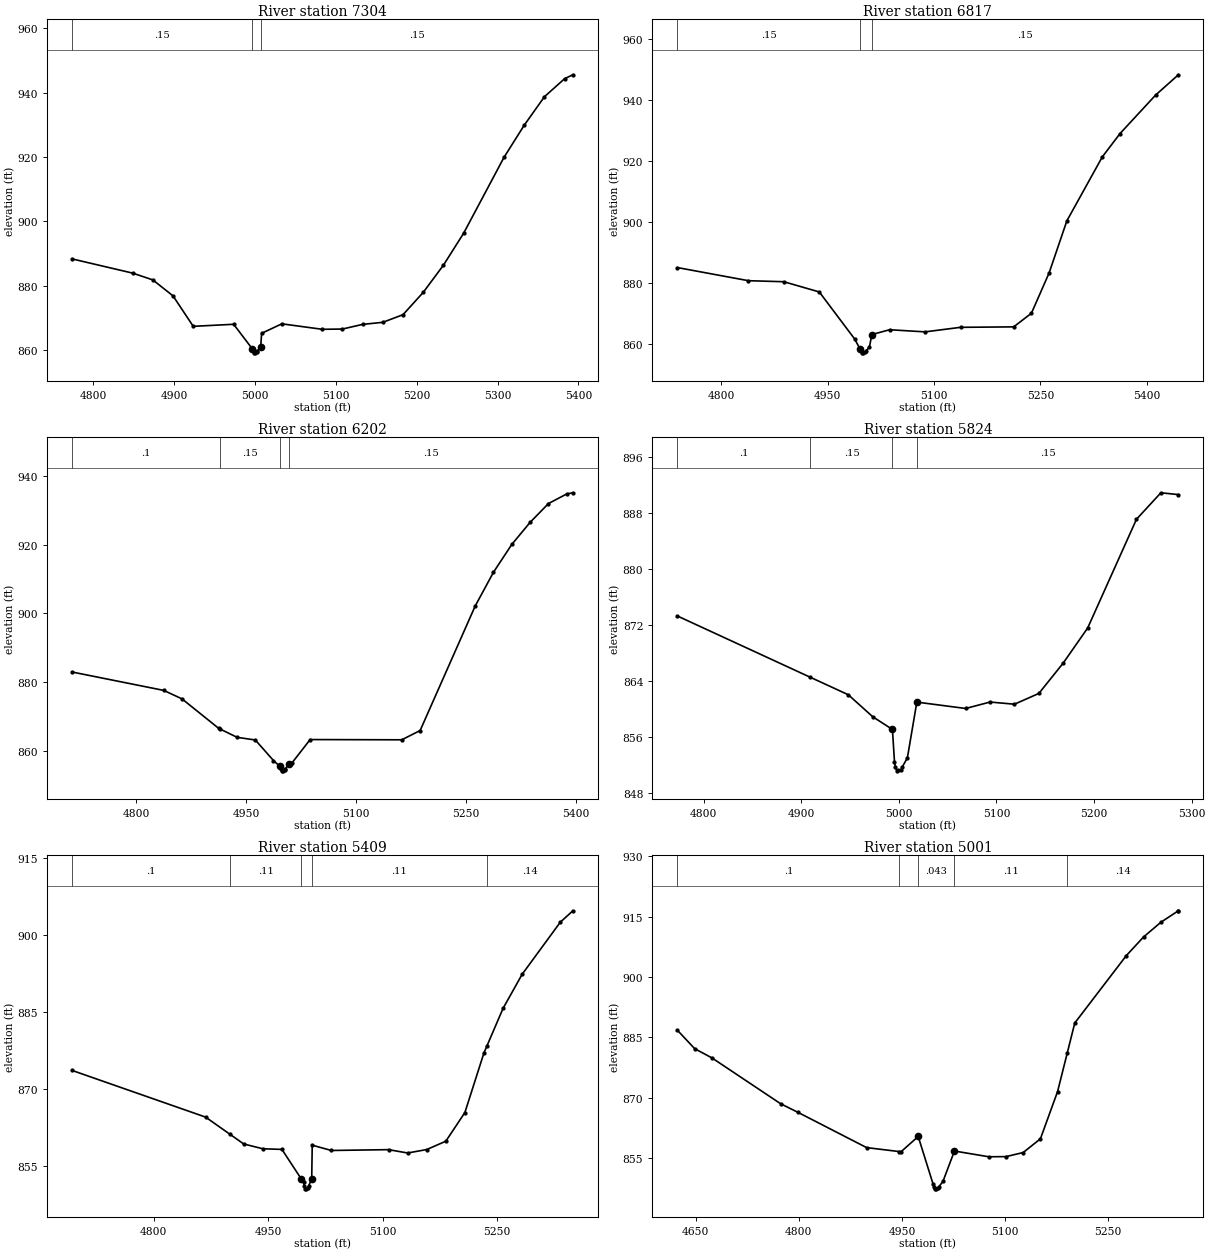
Type RM Length L Ch R = 1,7304,487,487,487
BEGIN DESCRIPTION:
Elk Shoal Creek 15.0
END DESCRIPTION:
XS GIS Cut Line= 3
      1363325.00       753925.00      1363287.57       753693.43
      1363175.00       753325.00
#Sta/Elev= 28
  4773.5  888.28  4848.5  883.86  4873.5  881.75  4898.5  876.77  4923.5  867.31
  4973.5  867.95  4996.5  860.34  4997.2  859.64  4998.3  859.07  4999.6  859.13
  5002.1  859.25  5002.9  859.63  5007.0  860.92  5008.1  865.14  5033.1  868.09
  5083.1  866.39  5108.1  866.47  5133.1  867.92  5158.1  868.56  5183.1  870.94
  5208.1  877.87  5233.1  886.33  5258.1  896.26  5308.1  919.88  5333.1  929.86
  5358.1  938.71  5383.1  944.33  5393.3  945.53
#Mann=3,-1,0
  4773.5    0.15       0  4996.5   0.046       0  5007.0    0.15       0
Bank Sta=4996.5,5007
XS Rating Curve= 0
Exp/Cntr=0.3,0.1

Type RM Length L Ch R = 1,6817,615,615,615
BEGIN DESCRIPTION:
Elk Shoal Creek 14.0
END DESCRIPTION:
XS GIS Cut Line= 3
      1363925.00       753775.00      1363716.18       753597.47
      1363625.00       753175.00
#Sta/Elev= 24
  4738.2  885.09  4838.2  880.79  4888.2  880.45  4938.2  877.09  4988.2  861.61
  4995.6  858.39  4996.5  857.69  4997.9  857.12  4999.5  857.18  5002.6  857.30
  5003.6  857.68  5008.8  858.97  5012.3  863.12  5037.3  864.70  5087.3  864.00
  5137.3  865.49  5212.3  865.64  5237.3  870.11  5262.3  883.37  5287.3  900.44
  5337.3  921.43  5362.3  929.08  5412.3  941.66  5444.5  948.35
#Mann=3,-1,0
  4738.2    0.15       0  4995.6   0.046       0  5012.3    0.15       0
Bank Sta=4995.6,5012.3
XS Rating Curve= 0
Exp/Cntr=0.3,0.1

Type RM Length L Ch R = 1,6202,378,378,378
BEGIN DESCRIPTION:
Elk Shoal Creek 13.0
END DESCRIPTION:
XS GIS Cut Line= 3
      1364355.89       753392.76      1364112.80       753264.82
      1363780.15       753028.12
#Sta/Elev= 26
  4712.4  882.94  4837.4  877.58  4862.4  875.10  4912.4  866.51  4914.5  866.29
  4937.4  863.90  4962.4  863.11  4987.1  857.12  4996.0  855.39  4996.9  854.69
  4998.1  854.12  4999.6  854.18  5002.3  854.30  5003.2  854.68  5007.9  855.97
  5012.1  856.37  5037.1  863.24  5162.1  863.17  5187.1  865.88  5262.1  902.15
  5287.1  912.03  5312.1  920.14  5337.1  926.59  5362.1  932.06  5387.1  934.87
  5395.4  935.20
#Mann=4,-1,0
  4712.4     0.1       0  4914.5    0.15       0  4996.0   0.046       0
  5007.9    0.15       0
Bank Sta=4996,5007.9
XS Rating Curve= 0
Exp/Cntr=0.3,0.1

Type RM Length L Ch R = 1,5824,415,415,415
BEGIN DESCRIPTION:
Elk Shoal Creek 12.0
END DESCRIPTION:
XS GIS Cut Line= 3
      1364525.00       753025.00      1364317.51       752951.36
      1364068.02       752797.83
#Sta/Elev= 22
  4773.3  873.29  4909.5  864.53  4948.3  862.04  4973.3  858.90  4993.5  857.08
  4995.6  852.44  4996.5  851.74  4997.9  851.17  4999.5  851.23  5002.6  851.35
  5003.6  851.73  5008.8  853.02  5018.5  860.99  5068.5  860.08  5093.5  861.00
  5118.5  860.69  5143.5  862.23  5168.5  866.58  5193.5  871.58  5243.5  887.12
  5268.5  890.90  5286.4  890.64
#Mann=4,-1,0
  4773.3     0.1       0  4909.5    0.15       0  4993.5   0.043       0
  5018.5    0.15       0
Bank Sta=4993.5,5018.5
XS Rating Curve= 0
Exp/Cntr=0.3,0.1

Type RM Length L Ch R = 1,5409,408,408,408
BEGIN DESCRIPTION:
Elk Shoal Creek 11.0
END DESCRIPTION:
XS GIS Cut Line= 3
      1364803.69       752733.86      1364522.22       752593.12
      1364225.00       752425.00
#Sta/Elev= 27
  4693.0  873.64  4868.0  864.56  4900.2  861.19  4918.0  859.33  4943.0  858.40
  4968.0  858.28  4993.0  852.61  4996.5  851.88  4997.2  851.18  4998.3  850.61
  4999.6  850.67  5002.1  850.79  5002.9  851.17  5007.0  852.46  5007.7  859.10
  5032.7  858.07  5107.7  858.23  5132.7  857.58  5157.7  858.25  5182.7  859.87
  5207.7  865.45  5232.7  877.06  5236.3  878.30  5257.7  885.70  5282.7  892.33
  5332.7  902.46  5349.2  904.68
#Mann=5,-1,0
  4693.0     0.1       0  4900.2    0.11       0  4993.0   0.043       0
  5007.0    0.11       0  5236.3    0.14       0
Bank Sta=4993,5007
XS Rating Curve= 0
Exp/Cntr=0.3,0.1

Type RM Length L Ch R = 1,5001,603,603,603
BEGIN DESCRIPTION:
Elk Shoal Creek 10.0
END DESCRIPTION:
XS GIS Cut Line= 3
      1365078.77       752414.00      1364739.72       752247.67
      1364464.64       752030.17
#Sta/Elev= 29
  4623.7  886.71  4648.7  882.15  4673.7  879.87  4773.7  868.46  4798.7  866.34
  4898.7  857.56  4946.4  856.57  4948.7  856.52  4973.7  860.33  4995.2  848.58
  4996.2  847.88  4997.7  847.31  4999.5  847.37  5002.9  847.49  5004.0  847.87
  5009.7  849.16  5026.4  856.71  5076.4  855.28  5101.4  855.32  5126.4  856.34
  5151.4  859.74  5176.4  871.50  5190.6  881.18  5201.4  888.54  5276.4  905.30
  5301.4  909.92  5326.4  913.55  5351.4  916.37  5352.0  916.43
#Mann=5,-1,0
  4623.7     0.1       0  4946.4    0.11       0  4973.7   0.043       0
  5026.4    0.11       0  5190.6    0.14       0
Bank Sta=4973.7,5026.4
XS Rating Curve= 0
Exp/Cntr=0.3,0.1

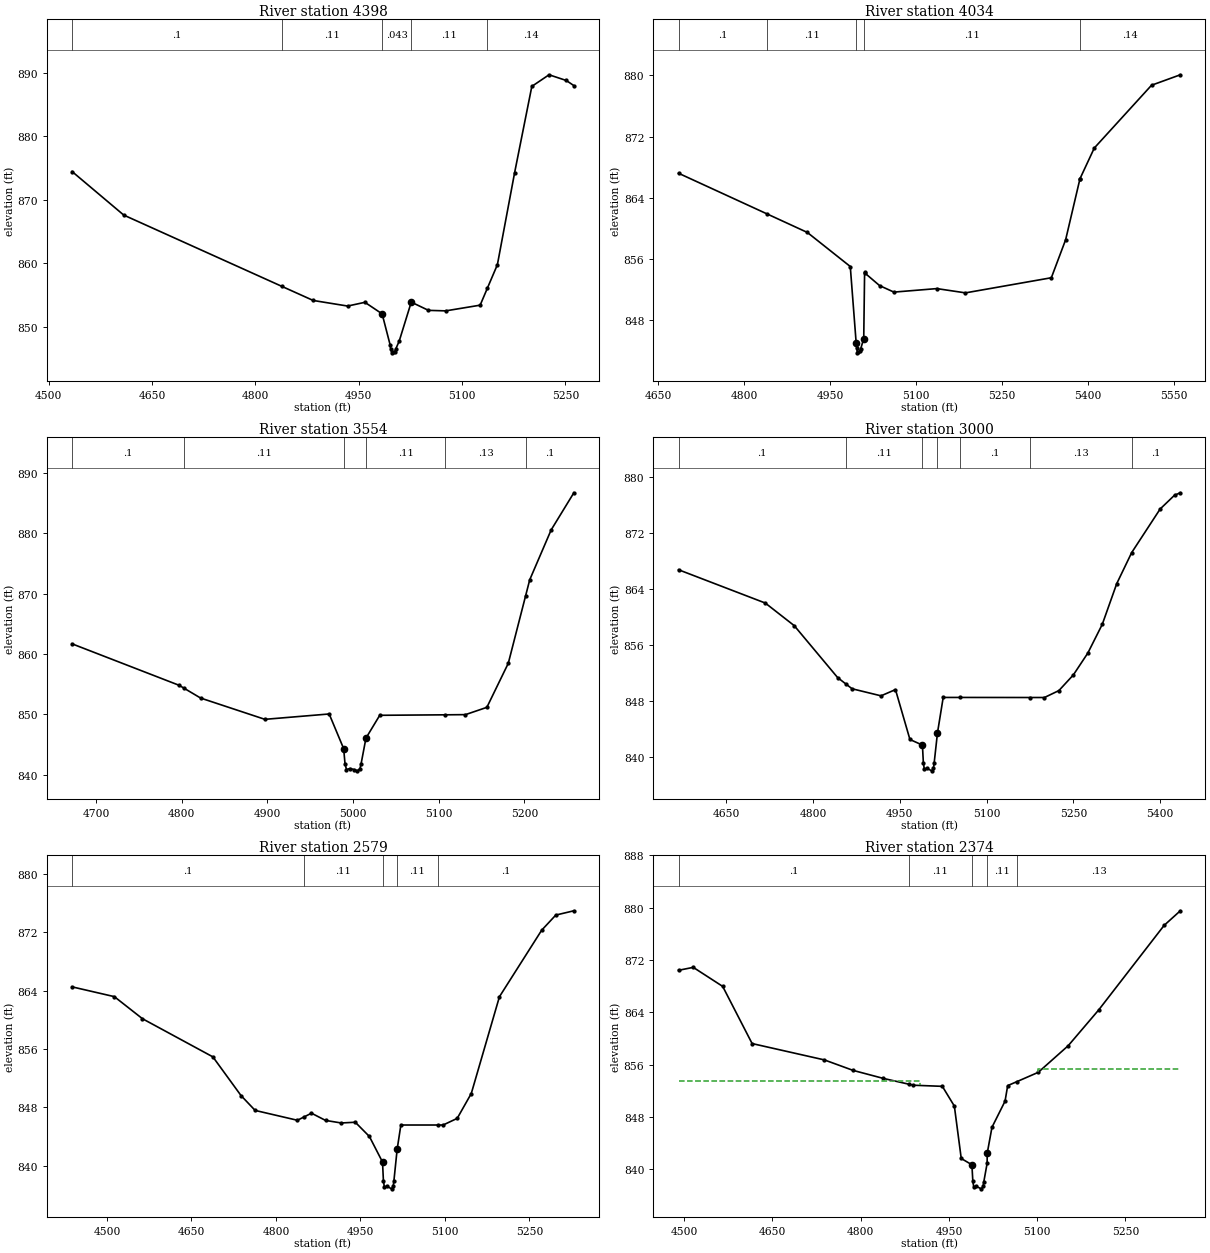
Type RM Length L Ch R = 1,4398,364,364,364
BEGIN DESCRIPTION:
Elk Shoal Creek 9.0
END DESCRIPTION:
XS GIS Cut Line= 3
      1365277.08       751838.26      1364835.68       751684.72
      1364586.19       751607.96
#Sta/Elev= 25
  4534.0  874.47  4609.0  867.60  4838.8  856.34  4884.0  854.13  4934.0  853.25
  4959.0  853.84  4984.0  852.02  4995.6  847.14  4996.5  846.44  4997.9  845.87
  4999.5  845.93  5002.6  846.05  5003.6  846.43  5008.8  847.72  5026.3  853.87
  5051.3  852.57  5076.3  852.49  5126.3  853.39  5136.9  856.10  5151.3  859.77
  5176.3  874.28  5201.3  887.90  5226.3  889.73  5251.3  888.83  5262.3  888.02
#Mann=5,-1,0
  4534.0     0.1       0  4838.8    0.11       0  4984.0   0.043       0
  5026.3    0.11       0  5136.9    0.14       0
Bank Sta=4984,5026.3
XS Rating Curve= 0
Exp/Cntr=0.3,0.1

Type RM Length L Ch R = 1,4034,480,480,480
BEGIN DESCRIPTION:
Elk Shoal Creek 8.0
END DESCRIPTION:
XS GIS Cut Line= 3
      1365283.48       751646.34      1365065.98       751403.25
      1364541.41       751236.92
#Sta/Elev= 24
  4685.3  867.20  4839.8  861.88  4910.3  859.45  4985.3  854.99  4995.6  844.96
  4996.5  844.26  4997.9  843.69  4999.5  843.75  5002.6  843.87  5003.6  844.25
  5008.8  845.54  5010.3  854.21  5011.5  854.09  5036.5  852.49  5061.5  851.64
  5136.5  852.10  5186.5  851.54  5336.5  853.52  5361.5  858.50  5386.4  866.45
  5386.5  866.48  5411.5  870.50  5511.5  878.72  5561.8  880.09
#Mann=5,-1,0
  4685.3     0.1       0  4839.8    0.11       0  4995.6   0.043       0
  5008.8    0.11       0  5386.4    0.14       0
Bank Sta=4995.6,5008.8
XS Rating Curve= 0
Exp/Cntr=0.3,0.1

Type RM Length L Ch R = 1,3554,554,554,554
BEGIN DESCRIPTION:
Elk Shoal Creek 7.0
END DESCRIPTION:
XS GIS Cut Line= 3
      1365545.76       751486.41      1365449.80       751166.56
      1365417.82       750917.07
#Sta/Elev= 24
  4672.2  861.70  4797.2  854.82  4803.1  854.32  4822.2  852.71  4897.2  849.18
  4972.2  850.07  4989.1  844.32  4990.7  841.78  4992.4  840.86  4996.3  841.02
  5001.3  840.86  5005.2  840.64  5008.1  841.01  5009.3  841.70  5015.1  846.06
  5031.2  849.85  5107.8  849.93  5131.2  849.96  5156.2  851.17  5181.2  858.48
  5201.4  869.66  5206.2  872.32  5231.2  880.59  5257.7  886.75
#Mann=6,-1,0
  4672.2     0.1       0  4803.1    0.11       0  4989.1   0.043       0
  5015.1    0.11       0  5107.8    0.13       0  5201.4     0.1       0
Bank Sta=4989.1,5015.1
XS Rating Curve= 0
Exp/Cntr=0.3,0.1

Type RM Length L Ch R = 1,3000,421,421,421
BEGIN DESCRIPTION:
Elk Shoal Creek 6.0
END DESCRIPTION:
XS GIS Cut Line= 3
      1365750.47       751582.37      1365966.83       751207.87
      1365925.00       750775.00
#Sta/Elev= 30
  4567.5  866.77  4717.5  862.01  4767.5  858.78  4842.5  851.36  4856.2  850.48
  4867.5  849.76  4917.5  848.75  4942.5  849.64  4967.5  842.51  4989.1  841.71
  4990.7  839.17  4992.4  838.25  4996.3  838.41  5005.2  838.03  5008.1  838.40
  5009.3  839.09  5015.1  843.45  5025.0  848.52  5054.3  848.52  5175.7  848.51
  5200.0  848.51  5225.0  849.50  5250.0  851.74  5275.0  854.86  5300.0  858.97
  5325.0  864.79  5350.8  869.22  5400.0  875.45  5425.0  877.43  5434.9  877.77
#Mann=7,-1,0
  4567.5     0.1       0  4856.2    0.11       0  4989.1   0.041       0
  5015.1    0.11       0  5054.3     0.1       0  5175.7    0.13       0
  5350.8     0.1       0
Bank Sta=4989.1,5015.1
XS Rating Curve= 0
Exp/Cntr=0.3,0.1

Type RM Length L Ch R = 1,2579,205,205,205
BEGIN DESCRIPTION:
Elk Shoal Creek 5.0
END DESCRIPTION:
XS GIS Cut Line= 4
      1365878.41       751633.55      1366307.02       751422.44
      1366332.61       751345.68      1366525.00       751075.00
#Sta/Elev= 30
  4438.0  864.53  4513.0  863.19  4563.0  860.16  4688.0  854.93  4738.0  849.62
  4763.0  847.59  4838.0  846.24  4848.9  846.66  4863.0  847.21  4888.0  846.22
  4915.8  845.87  4940.8  845.97  4965.8  844.02  4989.1  840.52  4990.7  837.98
  4992.4  837.06  4996.3  837.22  5005.2  836.84  5008.1  837.21  5009.3  837.90
  5015.1  842.26  5021.7  845.59  5087.3  845.59  5096.7  845.59  5121.7  846.50
  5146.7  849.91  5196.7  863.18  5271.7  872.30  5296.7  874.37  5328.8  874.96
#Mann=5,-1,0
  4438.0     0.1       0  4848.9    0.11       0  4989.1   0.041       0
  5015.1    0.11       0  5087.3     0.1       0
Bank Sta=4989.1,5015.1
XS Rating Curve= 0
Exp/Cntr=0.5,0.3

Type RM Length L Ch R = 1,2374,168,168,168
BEGIN DESCRIPTION:
Elk Shoak 4.2
END DESCRIPTION:
XS GIS Cut Line= 4
      1366413.83       751870.75      1366519.94       751454.09
      1366525.12       751384.22      1366571.70       751034.85
#Sta/Elev= 30
  4490.7  870.43  4515.7  870.88  4565.7  867.97  4615.7  859.23  4738.5  856.73
  4787.2  855.13  4838.3  853.91  4881.9  853.02  4889.8  852.86  4938.9  852.69
  4959.3  849.67  4971.0  841.66  4989.1  840.70  4990.7  838.16  4992.4  837.24
  4996.3  837.40  5005.2  837.02  5008.1  837.39  5009.3  838.08  5015.0  840.94
  5015.1  842.44  5023.2  846.43  5045.4  850.42  5049.9  852.80  5066.1  853.43
  5101.8  854.83  5152.7  858.90  5204.6  864.38  5315.7  877.30  5343.2  879.53
#Mann=5,-1,0
  4490.7     0.1       0  4881.9    0.11       0  4989.1   0.041       0
  5015.1    0.11       0  5066.1    0.13       0
#XS Ineff=2,0
    0.00 4900.60  853.52 5101.40    0.00  855.40
Bank Sta=4989.1,5015.1
XS Rating Curve= 0
Exp/Cntr=0.5,0.3

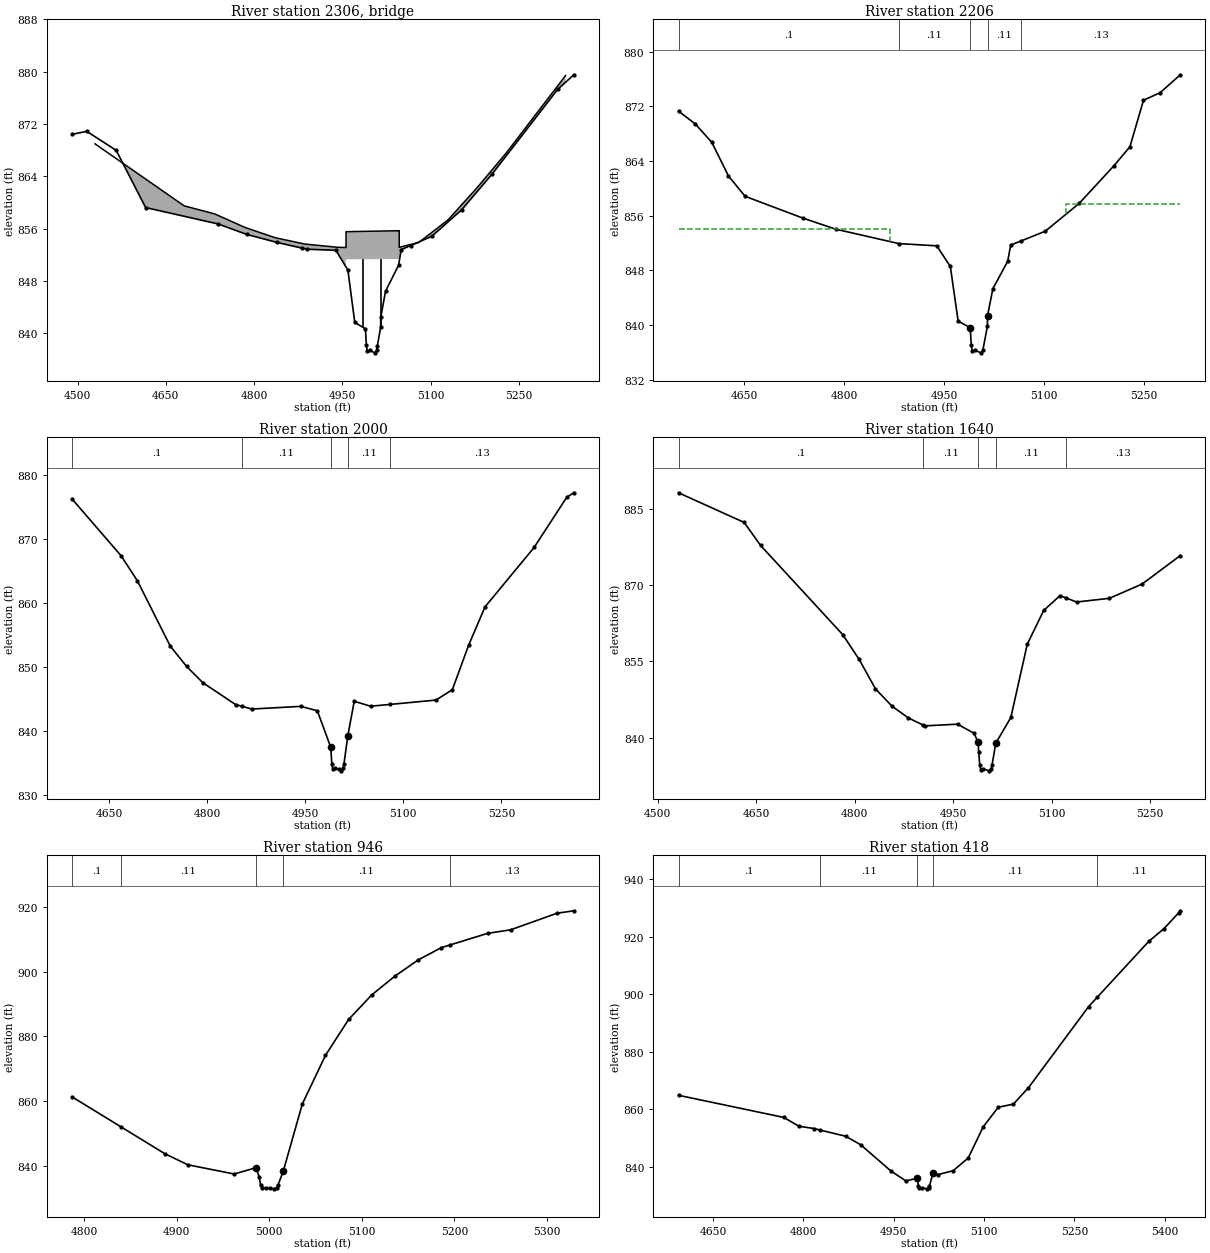
Type RM Length L Ch R =3,2306,,,
BEGIN DESCRIPTION:
ESC-1
Structure ID: UC_ESC_01
Detailed Survey Structure
END DESCRIPTION:
Bridge Culvert--1,0,-1,-1,0
Deck Dist Width WeirC Skew NumUp NumDn MinLoCord MaxHiCord MaxSubmerge Is_Ogee
55,26,3,,20,20,,,,0,1,1,,,
  4529.7  4681.2  4733.3  4785.4  4835.8  4886.3  4941.4  4955.6  4955.6  4956.1
  4956.1  5046.4  5046.4  5046.5  5046.5  5079.5  5129.5  5179.1  5228.3  5329.1
  868.97  859.49  858.25  856.16  854.62  853.65  853.16  853.12  853.12  853.12
  855.54  855.69  855.69  855.69  853.16  853.88  857.35  862.30  867.57  879.41
  817.02  817.02  817.02  817.02  817.02  817.02  817.02  817.02  851.32  851.32
  851.32  851.36  817.02  817.02  817.02  817.02  817.02  817.02  817.02  817.02
  4529.7  4681.2  4733.3  4785.4  4835.8  4886.3  4941.4  4955.6  4955.6  4956.1
  4956.1  5046.4  5046.4  5046.5  5046.5  5079.5  5129.5  5179.1  5228.3  5329.1
  868.97  859.49  858.25  856.16  854.62  853.65  853.16  853.12  853.12  853.12
  855.54  855.69  855.69  855.69  853.16  853.88  857.35  862.30  867.57  879.41
  817.02  817.02  817.02  817.02  817.02  817.02  817.02  817.02  851.32  851.32
  851.32  851.36  817.02  817.02  817.02  817.02  817.02  817.02  817.02  817.02
Pier Skew, UpSta & Num, DnSta & Num=,4984.8,2,4984.8,2,0,0,0,0,0
       2       2
  839.00  851.33
       2       2
  839.05  851.33
Pier Skew, UpSta & Num, DnSta & Num=,5015,2,5015,2,0,0,0,0,0
       2       2
  840.94  851.34
       2       2
  840.99  851.34
Abutment Skew #Up #Dn=,2,2
  4955.6  4955.8
  851.32  848.30
  4955.6  4955.8
  851.32  848.35
Abutment Skew #Up #Dn=,2,2
  5045.3  5046.4
  850.40  851.36
  5045.3  5046.4
  850.45  851.36
BR Coef=1,1,0,1.25,0,,,0.8,0,2,0,
WSPro=,,,, 1 ,,,, 0 ,,,, 0 ,,,,-1 ,-1 ,-1 , 0 , 0 , 0 , 0 , 0
BC Design=,,0,,0,,,,,,

Type RM Length L Ch R = 1,2206,206,206,206
BEGIN DESCRIPTION:
Elk Shoak 4.1
END DESCRIPTION:
XS GIS Cut Line= 4
      1366607.93       751826.75      1366693.33       751386.80
      1366711.45       751340.22      1366664.86       751089.19
#Sta/Elev= 30
  4551.2  871.31  4576.2  869.45  4601.2  866.74  4626.2  861.81  4651.2  858.84
  4738.5  855.63  4787.2  854.03  4881.9  851.92  4938.9  851.59  4959.3  848.57
  4971.0  840.56  4989.1  839.60  4990.7  837.06  4992.4  836.14  4996.3  836.30
  5005.2  835.92  5008.1  836.29  5015.0  839.84  5015.1  841.34  5023.2  845.33
  5045.4  849.32  5049.9  851.70  5066.1  852.33  5101.8  853.73  5152.7  857.80
  5204.6  863.28  5228.9  866.10  5249.3  872.91  5274.3  874.02  5304.6  876.64
#Mann=5,-1,0
  4551.2     0.1       0  4881.9    0.11       0  4989.1   0.041       0
  5015.1    0.11       0  5066.1    0.13       0
#XS Ineff=2,0
    0.00 4868.60  853.99 5133.40    0.00  857.74
Bank Sta=4989.1,5015.1
XS Rating Curve= 0
Exp/Cntr=0.5,0.3

Type RM Length L Ch R = 1,2000,360,360,360
BEGIN DESCRIPTION:
Elk Shoal Creek 4.0
END DESCRIPTION:
XS GIS Cut Line= 3
      1366975.00       751825.00      1366894.58       751426.68
      1366975.00       751075.00
#Sta/Elev= 30
  4593.6  876.25  4668.6  867.38  4693.6  863.45  4743.6  853.30  4768.6  850.11
  4793.6  847.56  4843.6  844.15  4853.7  843.87  4868.6  843.45  4943.6  843.87
  4968.6  843.17  4989.1  837.48  4990.7  834.94  4992.4  834.02  4996.3  834.18
  5001.3  834.02  5005.2  833.80  5008.1  834.17  5009.3  834.86  5015.1  839.22
  5025.0  844.66  5050.0  843.89  5079.5  844.17  5150.0  844.85  5175.0  846.47
  5200.0  853.44  5225.0  859.41  5300.0  868.68  5350.0  876.53  5360.8  877.22
#Mann=5,-1,0
  4593.6     0.1       0  4853.7    0.11       0  4989.1   0.041       0
  5015.1    0.11       0  5079.5    0.13       0
Bank Sta=4989.1,5015.1
XS Rating Curve= 0
Exp/Cntr=0.3,0.1

Type RM Length L Ch R = 1,1640,694,694,694
BEGIN DESCRIPTION:
Elk Shoal Creek 3.0
END DESCRIPTION:
XS GIS Cut Line= 3
      1367068.28       751953.40      1367241.00       751531.19
      1367275.00       751225.00
#Sta/Elev= 30
  4531.9  888.09  4631.9  882.26  4656.9  877.74  4781.9  860.24  4806.9  855.38
  4831.9  849.57  4856.9  846.19  4881.9  843.87  4904.9  842.43  4906.9  842.30
  4956.9  842.64  4981.9  840.85  4988.1  839.14  4989.1  837.15  4990.7  834.61
  4992.4  833.69  4996.3  833.85  5005.2  833.47  5008.1  833.84  5009.3  834.53
  5015.1  838.89  5038.1  843.97  5063.1  858.36  5088.1  864.98  5113.1  867.90
  5121.9  867.45  5138.1  866.63  5188.1  867.36  5238.1  870.17  5296.2  875.76
#Mann=5,-1,0
  4531.9     0.1       0  4904.9    0.11       0  4988.1   0.041       0
  5015.1    0.11       0  5121.9    0.13       0
Bank Sta=4988.1,5015.1
XS Rating Curve= 0
Exp/Cntr=0.3,0.1

Type RM Length L Ch R = 1,946,528,528,528
BEGIN DESCRIPTION:
Elk Shoal Creek 2.0
END DESCRIPTION:
XS GIS Cut Line= 3
      1367875.00       751225.00      1367701.60       751128.17
      1367425.00       750925.00
#Sta/Elev= 27
  4787.1  861.30  4839.9  852.02  4887.1  843.72  4912.1  840.27  4962.1  837.41
  4985.7  839.36  4989.1  836.50  4990.7  833.96  4992.4  833.04  4996.3  833.20
  5001.3  833.04  5005.2  832.82  5008.1  833.19  5009.3  833.88  5015.1  838.24
  5035.7  859.09  5060.7  874.15  5085.7  885.27  5110.7  892.88  5135.7  898.69
  5160.7  903.69  5185.7  907.50  5194.8  908.31  5235.7  911.93  5260.7  913.04
  5310.7  918.17  5328.9  918.93
#Mann=5,-1,0
  4787.1     0.1       0  4839.9    0.11       0  4985.7   0.041       0
  5015.1    0.11       0  5194.8    0.13       0
Bank Sta=4985.7,5015.1
XS Rating Curve= 0
Exp/Cntr=0.3,0.1

Type RM Length L Ch R = 1,418,0,0,0
BEGIN DESCRIPTION:
Elk Shoal Creek 1.0
END DESCRIPTION:
XS GIS Cut Line= 4
      1368002.26       751185.75      1368123.81       750936.26
      1368111.02       750808.32      1367725.00       750625.00
#Sta/Elev= 30
  4592.5  864.88  4767.5  857.17  4792.5  854.11  4817.5  853.32  4827.0  852.82
  4870.0  850.64  4895.0  847.68  4945.0  838.57  4970.0  835.10  4989.1  836.01
  4990.7  833.47  4992.4  832.55  4996.3  832.71  5005.2  832.33  5008.1  832.70
  5009.3  833.39  5015.1  837.75  5023.6  837.29  5048.6  838.64  5073.6  843.06
  5098.6  853.94  5123.6  860.74  5148.6  861.81  5173.6  867.50  5273.6  895.75
  5287.6  898.93  5373.6  918.47  5398.6  922.84  5423.6  928.48  5425.9  929.09
#Mann=5,-1,0
  4592.5     0.1       0  4827.0    0.11       0  4989.1   0.041       0
  5015.1    0.11       0  5287.6    0.11       0
Bank Sta=4989.1,5015.1
XS Rating Curve= 0
Exp/Cntr=0.3,0.1

Chan Stop Cuts=-1