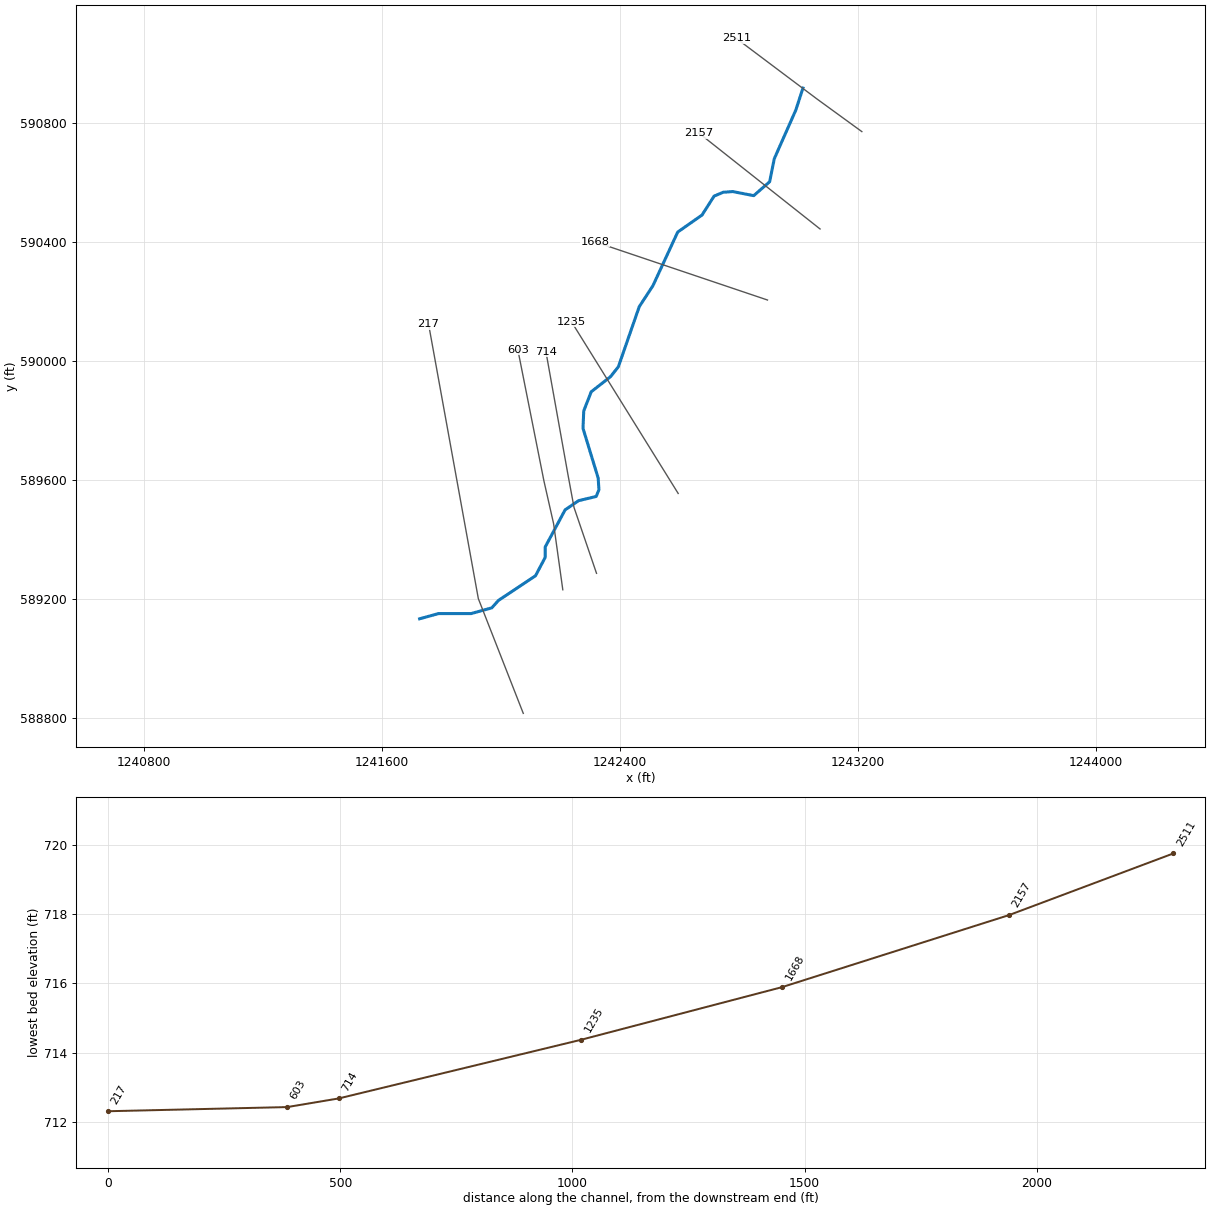
--- lds_first_broad_rvr_trib30.prj (project) ---

Proj Title=First Broad River Trib 30 Limited Detail Study
Current Plan=p03
Default Exp/Contr=0.3,0.1
English Units
Geom File=g01
Geom File=g02
Flow File=f02
Plan File=p01
Plan File=p03
Y Axis Title=Elevation
X Axis Title(PF)=Main Channel Distance
X Axis Title(XS)=Station
BEGIN DESCRIPTION:
First Broad River Trib 30
END DESCRIPTION:
DSS Export Rating Curves= 0
DSS Export Rating Curve Sorted= 0
DSS Export Volume Flow Curves= 0
DXF OffsetX= 0
DXF OffsetY= 0
DXF ScaleX= 1
DXF ScaleY= 10

--- lds_first_broad_rvr_trib30.p03 (plan) ---

Plan Title=Floodway Run_12-28-06
Program Version=3.13
Short Identifier=FWAY
Geom File=g02
Flow File=f02
Subcritical Flow
K Sum by GR= 0
Std Step Tol= 0.01
Critical Tol= 0.01
Num of Std Step Trials= 20
Max Error Tol= 0.3
Flow Tol Ratio= 0.001
Split Flow NTrial= 30
Split Flow Tol= 0.02
Split Flow Ratio= 0.02
Log Output Level= 0
Friction Slope Method= 1
Unsteady Friction Slope Method= 2
Unsteady Bridges Friction Slope Method= 1
Parabolic Critical Depth
Global Vel Dist= 0 , 0 , 0
Global Log Level= 0
CheckData=True
Encroach Param=-1 ,5,5, 2
Encroach River=First Broad Rive
Encroach Reach=Reach-1
Encroach Node=2511
       4      .7
Encroach Node=2157
       4      .7
Encroach Node=1668
       4      .7
Encroach Node=1235
       4      .7
Encroach Node=714
       1 4935.05 5064.95
Encroach Node=603
       1  4921.5  5078.5
Encroach Node=217
       4      .7
BEGIN DESCRIPTION:
Floodway Run
END DESCRIPTION:
Computation Interval=1HOUR
Output Interval=1HOUR
Run HTab= 0
Run UNet= 0
Run PostProcess= 0
UNET Theta= 1
UNET Theta Warmup= 1
UNET ZTol= 0.02
UNET ZSATol= 0.05
UNET MxIter= 20
UNET MaxInSteps= 0
UNET DtIC= 0
UNET DtMin= 0
UNET MaxCRTS= 20
UNET WFStab= 2
UNET SFStab= 1
UNET WFX= 1
UNET SFX= 1
UNET DSS MLevel= 4
UNET DZMax Abort= 100
UNET Convert EG Bridges=-1
UNET Use Existing IB Tables=-1
UNET Froude Reduction=False
UNET Froude Limit= 1
UNET Froude Power= 10
Instantaneous Interval=1HOUR
Write IC File= 0
Echo Input=False
Echo Output=False
Write Detailed= 0
Detailed Automatic Start=False, 10

--- lds_first_broad_rvr_trib30.p01 (plan) ---

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Plan Title=Floodway Run_06-24-06
Short Identifier=Floodway
Geom File=g01
Flow File=f02

--- lds_first_broad_rvr_trib30.p02 (plan) ---

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Plan Title=Floodway Run
Short Identifier=Floodway
Geom File= g01
Flow File= f02
Encroach Param= -1, 0, 0, 0

--- lds_first_broad_rvr_trib30.f02 (steady flow) ---

Flow Title=Floodway_06-24-06
Program Version=3.13
Number of Profiles= 2
Profile Names=100-year,100-FW
River Rch & RM=First Broad Rive,Reach-1         ,2511
    1910    1910
Boundary for River Rch & Prof#=First Broad Rive,Reach-1         , 1
Up Type= 0
Dn Type= 3
Dn Slope=0.003
Boundary for River Rch & Prof#=First Broad Rive,Reach-1         , 2
Up Type= 0
Dn Type= 3
Dn Slope=0.003
DSS Import GetInterval= 0
DSS Import GetPeak= 0
DSS Import FillOption= 0

--- lds_first_broad_rvr_trib30.g02 (geometry) ---

Geom Title=Existing Conditions_12-28-06
Program Version=3.13

River Reach=First Broad Rive,Reach-1
Reach XY= 30
      1243015.93       590916.61      1242991.84       590842.61
      1242919.56       590679.12      1242903.88       590601.69
      1242850.38       590555.06        1242780.       590568.81
      1242747.88        590566.5      1242717.25        590553.5
      1242676.75         590490.      1242594.88       590432.63
       1242511.5       590252.13      1242465.63       590181.75
       1242395.5         589980.      1242369.38       589946.88
      1242304.25       589895.88      1242279.13       589831.56
      1242276.63       589773.06      1242327.63       589605.88
      1242330.13       589566.63        1242321.       589544.06
      1242261.63       589529.88       1242216.5       589498.94
      1242149.63       589374.38      1242149.63       589339.31
        1242117.       589277.44       1241992.5       589194.69
        1241970.       589169.63      1241900.63       589150.44
      1241791.13       589150.44       1241727.5       589132.88

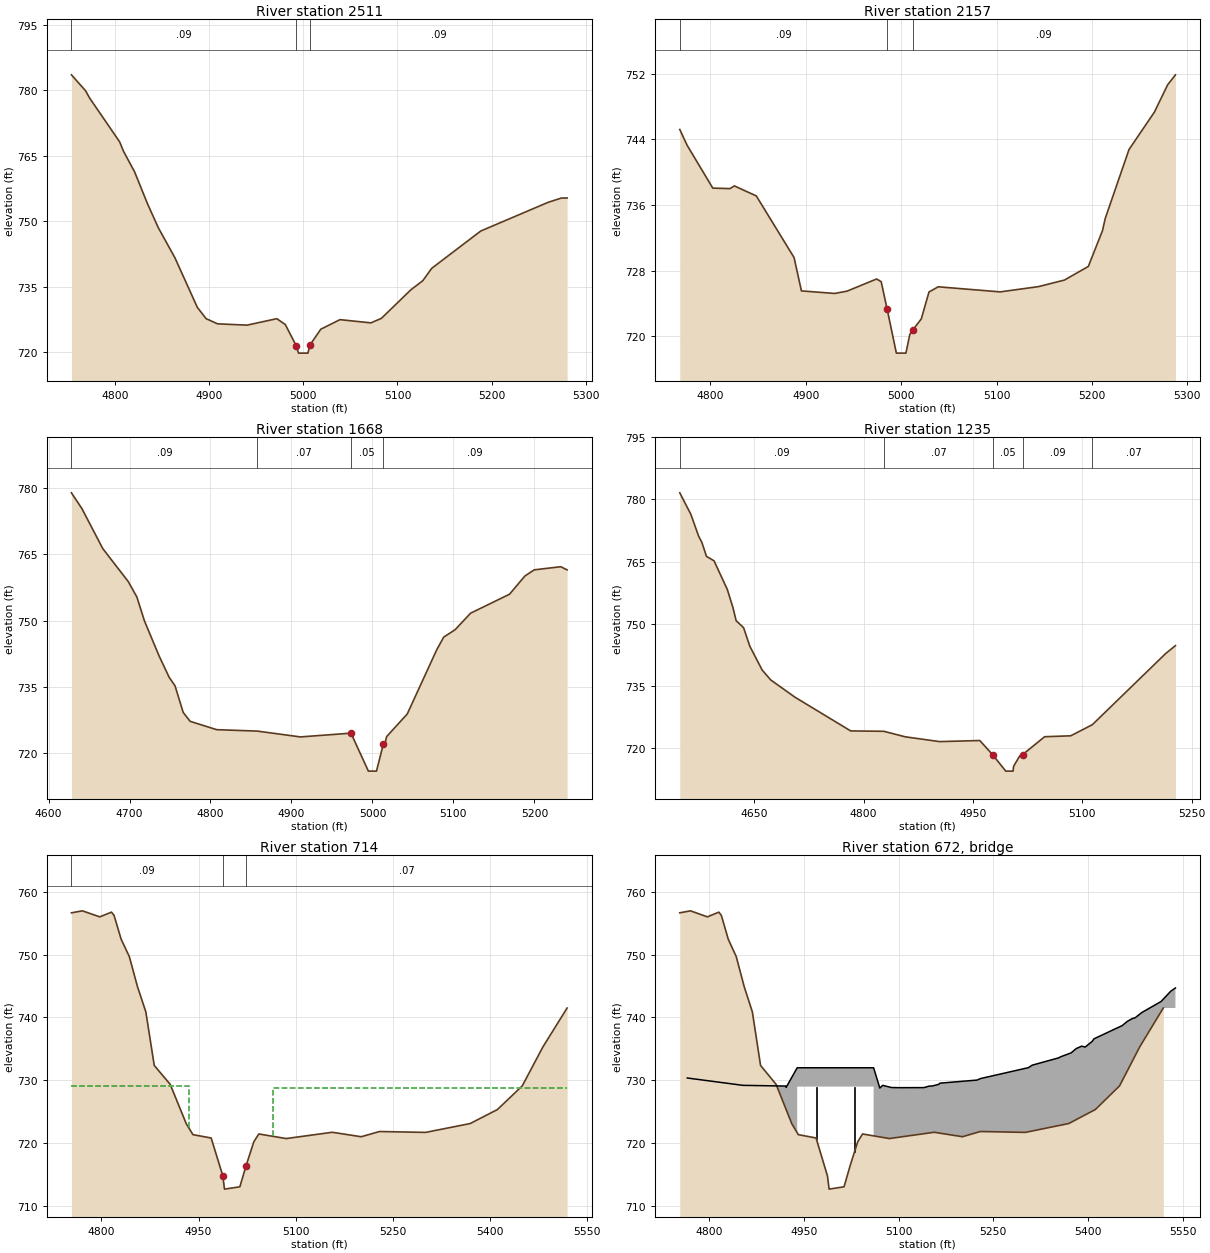
Type RM Length L Ch R = 1 ,2511    ,354,354,354
BEGIN DESCRIPTION:
first_broad_rvr_trib30_0
END DESCRIPTION:
XS GIS Cut Line= 3
      1243213.83       590770.33      1243062.39       590880.47
      1242791.64       591083.82
#Sta/Elev= 30
  4754.1  783.49  4769.1  779.84  4773.4  778.17  4805.3  768.12  4809.4  765.96
  4821.1  761.27  4834.6  754.06  4846.2   748.5  4863.9  741.58  4887.7  730.22
    4897  727.64  4909.1  726.46  4940.4  726.16    4972  727.64    4981   726.3
  4992.5  721.49    4995  719.75    5005  719.75    5007  721.54  5018.6  725.22
    5039  727.42  5071.8  726.68    5083  727.72  5114.1  734.23  5126.9  736.34
  5136.3  739.16  5188.4  747.72    5260   754.3    5274  755.27    5280  755.28
#Mann= 3 , 0 , 0
  4754.1     .09       0  4992.5     .05       0    5007     .09       0
Bank Sta=4992.5,5007
Exp/Cntr=0.3,0.1

Type RM Length L Ch R = 1 ,2157    ,489,489,489
BEGIN DESCRIPTION:
first_broad_rvr_trib30_1
END DESCRIPTION:
XS GIS Cut Line= 2
      1243073.37       590443.08      1242666.02       590765.46
#Sta/Elev= 30
    4768  745.21  4775.7  743.29  4802.6  738.07  4820.6  738.01  4825.2  738.34
  4848.2  737.12  4887.8  729.61  4895.5  725.55  4930.4  725.24  4943.3  725.52
  4974.3     727  4979.1  726.67 4985.37  723.31    4995  717.97    5005  717.97
  5009.1  720.24  5012.5  720.84  5021.1  722.13  5029.2  725.42  5038.9  726.05
  5103.8  725.43  5143.9  726.07  5171.2  726.87  5196.2  728.53  5211.1  732.91
  5213.9  734.37  5238.8  742.76  5265.5  747.34  5279.3  750.65  5287.5  751.87
#Mann= 3 , 0 , 0
    4768     .09       0 4985.37     .05       0  5012.5     .09       0
Bank Sta=4985.37,5012.5
Exp/Cntr=0.3,0.1

Type RM Length L Ch R = 1 ,1668    ,433,433,433
BEGIN DESCRIPTION:
first_broad_rvr_trib30_2
END DESCRIPTION:
XS GIS Cut Line= 2
      1242896.67       590204.33      1242316.66       590399.92
#Sta/Elev= 30
  4628.3  778.94  4641.4  775.31    4667   766.3  4698.4  758.85  4709.1  755.34
  4718.5   749.9  4736.6  741.96    4749  737.14  4756.2  735.22  4766.3  729.19
  4774.9  727.17  4807.7  725.28  4857.8  724.96    4911  723.64  4973.5  724.49
    4995  715.89    5005  715.89  5013.4  721.97  5015.9  722.49  5017.6  723.73
    5043  728.84  5079.5  743.42    5088  746.25  5102.1  747.93  5121.2  751.67
  5169.3  755.97  5188.2  760.08  5199.8  761.49  5232.5   762.2  5240.4  761.49
#Mann= 4 ,-1 , 0
  4628.3     .09       0  4857.8     .07       0  4973.5     .05       0
  5013.4     .09       0
Bank Sta=4973.5,5013.4
Exp/Cntr=0.3,0.1

Type RM Length L Ch R = 1 ,1235    ,521,521,521
BEGIN DESCRIPTION:
first_broad_rvr_trib30_3
END DESCRIPTION:
XS GIS Cut Line= 2
      1242596.55       589554.18      1242237.75       590131.49
#Sta/Elev= 30
    4548  781.59  4563.2   776.4  4573.9   771.1  4578.3  769.62  4584.6  766.25
    4595  765.16  4613.2  758.25  4620.8  753.94  4625.3  750.71  4635.5  749.02
    4644  744.56    4661  738.78  4672.7   736.4    4706  732.22  4782.4  724.08
  4827.9  723.99  4857.1  722.66  4904.3   721.5  4959.4  721.76  4977.3  718.28
    4995  714.37    5005  714.37  5005.8  715.54  5014.2  718.06  5018.1  718.35
  5048.3  722.68  5084.1   722.9  5113.7  725.58  5214.4  742.79  5227.7  744.68
#Mann= 5 ,-1 , 0
    4548     .09       0  4827.9     .07       0  4977.3     .05       0
  5018.1     .09       0  5113.7     .07       0
Bank Sta=4977.3,5018.1
Exp/Cntr=0.5,0.3

Type RM Length L Ch R = 1 ,714     ,111,111,111
BEGIN DESCRIPTION:
North_Lafayette_St_US
END DESCRIPTION:
XS GIS Cut Line= 4
      1242322.06       589285.76      1242246.52       589506.97
      1242226.29       589616.23       1242152.1       590030.33
#Sta/Elev= 30
  4753.6  756.66  4770.5  756.98  4797.3  756.02  4815.4  756.77  4819.4  756.26
  4830.3  752.48    4843  749.69  4855.6  744.91  4868.5   740.9  4881.5  732.37
  4906.1  729.36  4930.9   723.1  4941.3  721.35  4969.4  720.82  4987.4  714.79
    4990  712.68  5013.7  713.05 5023.29   716.4  5035.3  720.21    5043  721.46
  5085.4  720.73  5156.4  721.73  5201.2  721.02  5229.4  721.85  5300.6  721.71
  5369.5  723.12  5411.6  725.35  5449.9  729.11  5481.9  735.33  5519.2  741.51
#Mann= 3 , 0 , 0
  4753.6     .09       0  4987.4    .045       0 5023.29     .07       0
#XS Ineff= 2 , 0
       0 4935.05  729.11 5064.95       0  728.85
Permanent Ineff=
       F       F
Bank Sta=4987.4,5023.29
Exp/Cntr=0.5,0.3

Type RM Length L Ch R = 3 ,672     ,,,
BEGIN DESCRIPTION:
North_Lafayette_St_TOR
Structure ID: layfayette st SR1005
Approximate Survey Structure
END DESCRIPTION:
Bridge Culvert--1,0,-1,-1, 0
Deck Dist Width WeirC Skew NumUp NumDn MinLoCord MaxHiCord MaxSubmerge Is_Ogee
29,26,3,0, 38, 38, , , , 0, 1,1,,
  4765.4  4853.6  4921.3  4921.6    4922  4939.5  4939.5  5060.5  5060.5  5070.3
  5074.8    5089  5102.6  5140.3  5148.5    5153  5163.6  5165.6  5224.3  5229.8
  5305.7  5311.5  5353.6  5356.5  5373.2  5381.4    5390  5395.4  5406.8  5409.3
  5454.2  5461.9  5469.7  5474.9  5485.1  5515.7    5531  5538.4
  730.37   729.2  729.09  729.03  728.87     732     732     732     732  728.77
   729.2  728.85  728.83  728.84  729.08  729.09  729.36  729.55  730.04  730.28
  732.02  732.41  733.58  733.74  734.37  735.06  735.44  735.29  736.22   736.6
  738.72  739.36  739.81  739.98  740.79  742.55  744.19   744.7
  692.68  692.68  692.68  692.68  692.68  692.68     729     729  692.68  692.68
  692.68  692.68  692.68  692.68  692.68  692.68  692.68  692.68  692.68  692.68
  692.68  692.68  692.68  692.68  692.68  692.68  692.68  692.68  692.68  692.68
  692.68  692.68  692.68  692.68  692.68  692.68  692.68  692.68
  4765.4  4853.6  4921.3  4921.6    4922  4939.5  4939.5  5060.5  5060.5  5070.3
  5074.8    5089  5102.6  5140.3  5148.5    5153  5163.6  5165.6  5224.3  5229.8
  5305.7  5311.5  5353.6  5356.5  5373.2  5381.4    5390  5395.4  5406.8  5409.3
  5454.2  5461.9  5469.7  5474.9  5485.1  5515.7    5531  5538.4
  730.37   729.2  729.09  729.03  728.87     732     732     732     732  728.77
   729.2  728.85  728.83  728.84  729.08  729.09  729.36  729.55  730.04  730.28
  732.02  732.41  733.58  733.74  734.37  735.06  735.44  735.29  736.22   736.6
  738.72  739.36  739.81  739.98  740.79  742.55  744.19   744.7
  692.68  692.68  692.68  692.68  692.68  692.68     729     729  692.68  692.68
  692.68  692.68  692.68  692.68  692.68  692.68  692.68  692.68  692.68  692.68
  692.68  692.68  692.68  692.68  692.68  692.68  692.68  692.68  692.68  692.68
  692.68  692.68  692.68  692.68  692.68  692.68  692.68  692.68
Pier Skew, UpSta & Num, DnSta & Num=  ,4969.8, 2 ,4969.8, 2 , 0 , 0 , 0 ,0,0
       2       2
  720.69     729
       2       2
  718.99     729
Pier Skew, UpSta & Num, DnSta & Num=  ,5030.3, 2 ,5030.3, 2 , 0 , 0 , 0 ,0,0
       2       2
  718.55     729
       2       2
  715.92     729
Abutment Skew #Up #Dn= , 2 , 2
  4939.5  4962.5
     729  721.03
  4939.5  4962.5
     729  718.79
Abutment Skew #Up #Dn= , 2 , 2
  5037.5  5060.5
  720.57     729
  5037.5  5060.5
  717.75     729
BR Coef= 1 , 1 , 0 ,1.25, 0 ,,,0.8,0,2,0,
WSPro=,,,, 1 ,,,, 0 ,,,, 0 ,,,,-1 ,-1 ,-1 , 0 , 0 , 0 , 0 , 0
BC Design=,, 0 ,, 0 ,,,,,,
BC HTab HWMax=756.98

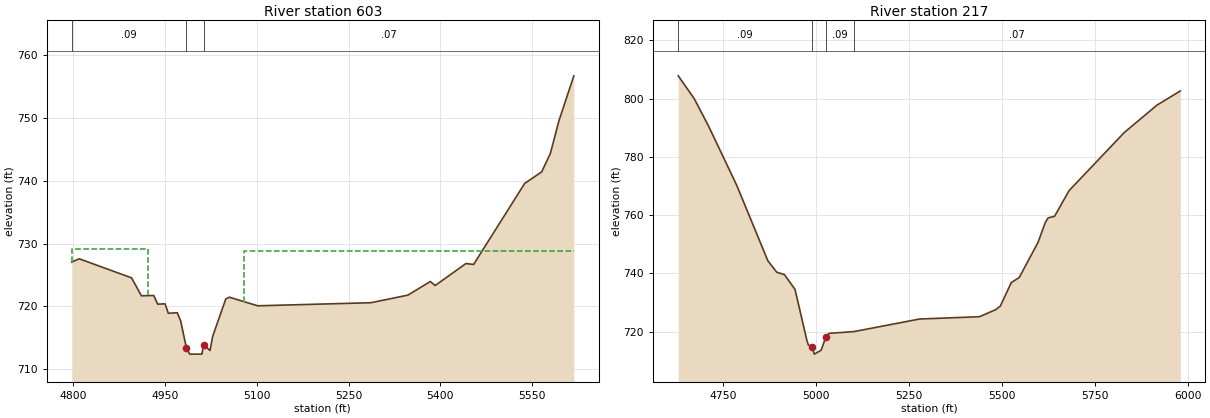
Type RM Length L Ch R = 1 ,603     ,386,386,386
BEGIN DESCRIPTION:
North_Lafayette_St_DS
END DESCRIPTION:
XS GIS Cut Line= 4
      1242208.75       589230.46      1242177.73       589453.02
      1242145.36         589596.      1242057.68       590037.07
#Sta/Elev= 30
  4797.2  727.06  4809.5  727.58    4895  724.55  4911.1   721.7  4931.2  721.75
  4937.7  720.37  4949.7  720.43  4955.1  718.92  4969.7  719.01  4975.3  717.71
  4984.6  713.44    4990  712.43    5010  712.43  5012.8   713.9  5023.3  713.01
  5027.6  715.25    5049  721.19  5054.8  721.48  5101.2  720.11  5286.4   720.6
  5346.9  721.81  5383.5  723.97  5391.4  723.33  5441.8  726.83  5454.3  726.68
  5537.8  739.56  5565.6  741.39  5579.8  744.32  5593.8  749.51  5618.2  756.66
#Mann= 3 , 0 , 0
  4797.2     .09       0  4984.6    .045       0  5012.8     .07       0
#XS Ineff= 2 , 0
       0  4921.5  729.15  5078.5       0  728.83
Permanent Ineff=
       F       F
Bank Sta=4984.6,5012.8
Exp/Cntr=0.5,0.3

Type RM Length L Ch R = 1 ,217     ,0,0,0
BEGIN DESCRIPTION:
first_broad_rvr_trib30_4
END DESCRIPTION:
XS GIS Cut Line= 3
      1242075.89       588815.01      1241924.82       589200.78
      1241757.56        590123.4
#Sta/Elev= 30
  4628.3  807.83  4671.3  800.01  4710.2  790.52  4786.2  770.14  4869.5  744.39
  4893.6  740.42  4914.2   739.6  4942.8  734.53  4974.7  717.04  4978.7  715.45
  4987.8   714.9    4995  712.31  5013.1  713.67    5026  718.24  5034.2  719.43
  5101.6  720.05  5278.2  724.36  5439.4  725.15  5482.8  727.55  5495.6  728.79
    5525  736.84  5546.7  738.63  5597.3  750.71  5616.7  757.51  5624.4  759.08
  5641.7  759.61  5680.7  768.42  5829.5  788.38  5917.3  797.76  5980.3  802.64
#Mann= 4 ,-1 , 0
  4628.3     .09       0  4987.8     .05       0    5026     .09       0
  5101.6     .07       0
Bank Sta=4987.8,5026
Exp/Cntr=0.3,0.1

Chan Stop Cuts=-1
Use User Specified Reach Order=0
User Specified Reach Order=First Broad Rive,Reach-1

--- lds_first_broad_rvr_trib30.g01 (geometry) ---

Geom Title=Existing Conditions_06-24-06
Program Version=3.13

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
River Reach=First Broad Rive,Reach-1