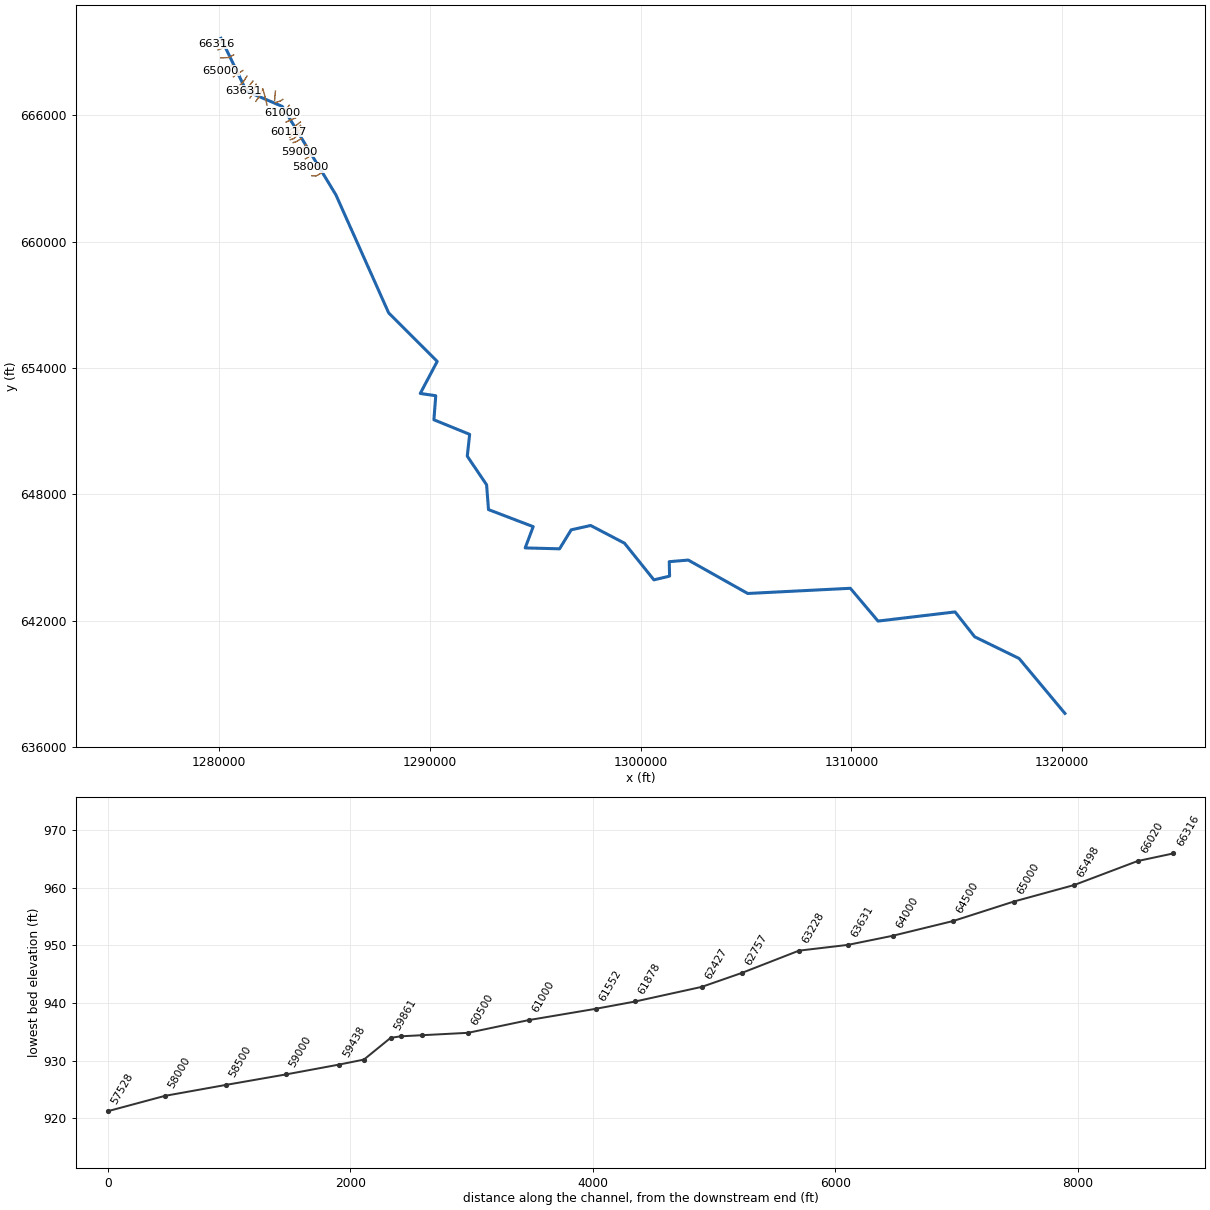
--- Howards Creek.prj (project) ---

Proj Title=Howards Creek Limited Detail Study
Current Plan=p01
Default Exp/Contr=0.3,0.1
English Units
Geom File=g01
Flow File=f01
Plan File=p01
Y Axis Title=Elevation
X Axis Title(PF)=Main Channel Distance
X Axis Title(XS)=Station
BEGIN DESCRIPTION:
& RHowards Creek
END DESCRIPTION:
DSS Export Rating Curves= 0
DSS Export Rating Curve Sorted= 0
DSS Export Volume Flow Curves= 0
DXF OffsetX= 0
DXF OffsetY= 0
DXF ScaleX= 1
DXF ScaleY= 10

--- Howards Creek.p01 (plan) ---

Plan Title=Floodway Run
Program Version=3.12
Short Identifier=Floodway
Geom File=g01
Flow File=f01
Subcritical Flow
K Sum by GR= 0
Std Step Tol= 0.01
Critical Tol= 0.01
Num of Std Step Trials= 20
Max Error Tol= 0.3
Flow Tol Ratio= 0.001
Split Flow NTrial= 30
Split Flow Tol= 0.02
Split Flow Ratio= 0.02
Log Output Level= 0
Friction Slope Method= 1
Unsteady Friction Slope Method= 2
Unsteady Bridges Friction Slope Method= 1
Parabolic Critical Depth
Global Vel Dist= 0 , 0 , 0
Global Log Level= 0
CheckData=True
Encroach Param=-1 ,5,5, 2
Encroach River=Howards Creek
Encroach Reach=Reach-1
Encroach Node=66316
       1 4980.15 5097.53
Encroach Node=66020
       1  4992.8 5095.27
Encroach Node=65498
       1 4991.26 5126.74
Encroach Node=65000
       1 4982.62 5109.82
Encroach Node=64500
       1 4855.53    5012
Encroach Node=64000
       1 4890.06  5007.2
Encroach Node=63631
       1 4889.17  5007.2
Encroach Node=63228
       1 4770.05 5014.01
Encroach Node=62757
       1  4991.8 5043.88
Encroach Node=62427
       1  4974.8 5154.71
Encroach Node=61878
       1 4985.48 5040.65
Encroach Node=61552
       1 4978.09 5019.83
Encroach Node=61000
       1 4926.83 5036.38
Encroach Node=60500
       1 4851.87  5065.3
Encroach Node=60117
       1 4856.27 5129.39
Encroach Node=59943
       1 4971.44    5025
Encroach Node=59861
       1 4971.44    5025
Encroach Node=59641
       1 4967.39 5082.67
Encroach Node=59438
       1 4990.57 5085.11
Encroach Node=59000
       1 4946.57 5101.98
Encroach Node=58500
       1 4934.89  5035.1
Encroach Node=58000
       1 4916.66    5009
Encroach Node=57528
       1 4946.23 5011.83
Encroach Node=57019
       1    4991 5175.69
Encroach Node=56666
       1 4937.76 5131.29
Encroach Node=56000
       1 4832.81  5013.4
Encroach Node=55500
       1 4851.85 5213.38
Encroach Node=55000
       1 4843.56 5315.69
Encroach Node=54340
       1 4817.49 5214.69
Encroach Node=54126
       1    4947    5053
Encroach Node=54041
       1    4972    5034
Encroach Node=53513
       1 4848.11  5013.4
Encroach Node=53049
       1 4815.14 5024.56
Encroach Node=52468
       1 4899.18 5178.93
Encroach Node=51845
       1  4871.2 5033.59
Encroach Node=51500
       1 4875.37 5031.39
Encroach Node=50940
       1 4815.26 5106.82
Encroach Node=50425
       1 4797.34 5241.15
Encroach Node=49980
       1 4921.86  5014.2
Encroach Node=49316
       1 4984.17 5188.92
Encroach Node=49111
       1 4980.23 5231.25
Encroach Node=48326
       1  4984.6 5198.56
Encroach Node=47930
       1  4984.6 5320.84
Encroach Node=47512
       1 4970.82 5196.46
Encroach Node=47000
       1 4923.48 5024.59
Encroach Node=46323
       1 4853.86  5015.4
Encroach Node=46021
       1 4885.33 5062.99
Encroach Node=45742
       1 4894.67  5015.4
Encroach Node=45409
       1 4923.27 5017.08
Encroach Node=45000
       1 4971.09 5043.45
Encroach Node=44756
       1 4983.04    5026
Encroach Node=44475
       1 4973.45 5027.45
Encroach Node=44358
       1  4973.2  5027.2
Encroach Node=43943
       1  4984.6 5018.51
Encroach Node=43663
       1 4977.65 5033.02
Encroach Node=43132
       1 4975.97  5015.8
Encroach Node=42592
       1 4927.33 5029.52
Encroach Node=42306
       1 4976.62  5015.8
Encroach Node=41656
       1 4833.15  5028.6
Encroach Node=41365
       1 4973.53  5015.8
Encroach Node=40649
       1 4980.79  5407.2
Encroach Node=39895
       1 4816.43 5295.52
Encroach Node=39266
       1 4966.78 5237.11
Encroach Node=39044
       1  4978.1 5090.42
Encroach Node=38764
       1    4969  5031.5
Encroach Node=38659
       1  4968.3  5030.8
Encroach Node=38438
       1 4851.45  5016.2
Encroach Node=38169
       1 4882.63    5017
Encroach Node=37758
       1 4736.23 5017.25
Encroach Node=37295
       1  4983.8  5193.8
Encroach Node=36999
       1 4982.67 5123.56
Encroach Node=36196
       1 4914.21 5209.21
Encroach Node=35795
       1 4844.74 5141.63
Encroach Node=35415
       1  4983.1 5227.12
Encroach Node=34750
       1 4829.83 5150.38
Encroach Node=34412
       1  4983.1 5060.05
Encroach Node=34039
       1    4975    5041
Encroach Node=33500
       1    4955    5030
Encroach Node=32995
       1    4972  5045.5
Encroach Node=32748
       1  4969.5  5030.4
Encroach Node=32562
       1    4989  5033.5
Encroach Node=32424
       1    4950    5061
Encroach Node=32350
       1  4968.4  5031.7
Encroach Node=32025
       1 4941.31  5018.9
Encroach Node=31535
       1    4984    5019
Encroach Node=30842
       1 4972.46 5081.33
Encroach Node=30404
       1 4960.71 5033.27
Encroach Node=29907
       1 4977.22 5019.87
Encroach Node=29534
       1    4985 5027.63
Encroach Node=29320
       1 4972.55  5025.6
Encroach Node=29000
       1 4964.73  5022.8
Encroach Node=28699
       1 4954.43  5013.4
Encroach Node=28572
       1    4976    5024
Encroach Node=28518
       1    4976    5024
Encroach Node=28394
       1    4960    5018
Encroach Node=28000
       1 4955.58 5020.87
Encroach Node=27475
       1    4965 5040.44
Encroach Node=27000
       1 4980.15  5030.1
Encroach Node=26456
       1    4970    5060
Encroach Node=25879
       1    4963    5220
Encroach Node=25500
       1 4900.19 5117.58
Encroach Node=24784
       1 4560.42  5160.9
Encroach Node=24350
       1 4545.53    5108
Encroach Node=23855
       1 4874.94 5334.33
Encroach Node=23681
       1 4897.54  5026.4
Encroach Node=23468
       1 4848.63 5090.89
Encroach Node=23009
       1  4916.4 5053.54
Encroach Node=22515
       1 4961.33 5094.75
Encroach Node=22000
       1 4955.24  5019.5
Encroach Node=21772
       1 4975.76 5037.22
Encroach Node=21621
       1 4843.07 5031.82
Encroach Node=21500
       1 4830.42 5042.29
Encroach Node=21137
       1 4376.59 5157.74
Encroach Node=20374
       1 4830.33 5439.32
Encroach Node=20167
       1    4920    5080
Encroach Node=20097
       1    4940    5060
Encroach Node=19924
       1 4910.66 5139.43
Encroach Node=19633
       1 4916.78 5034.48
Encroach Node=19030
       1 4707.38 5046.91
Encroach Node=18691
       1 4948.71 5150.12
Encroach Node=18291
       1 4814.05 5423.34
Encroach Node=17430
       1 4804.74 5085.58
Encroach Node=17000
       1 4421.18  5748.1
Encroach Node=16500
       1 4125.21 5604.01
Encroach Node=16000
       1 4049.39  5531.1
Encroach Node=15500
       1 4548.45  5488.2
Encroach Node=15000
       1 4777.56 5167.38
Encroach Node=14335
       1 4711.74 5662.32
Encroach Node=14049
       1 4736.05 5266.15
Encroach Node=13757
       1    4925    5065
Encroach Node=13679
       1    4925    5065
Encroach Node=13418
       1 4849.78 5091.66
Encroach Node=12963
       1 4892.92 5144.19
Encroach Node=12500
       1 4589.81 5180.93
Encroach Node=12000
       1 4236.18 5529.48
Encroach Node=11500
       1 4292.99 5452.43
Encroach Node=11000
       1 4580.64 5405.74
Encroach Node=10500
       1 4701.34 5327.38
Encroach Node=10042
       1 4579.88 5277.98
Encroach Node=9624
       1 4610.48 5252.33
Encroach Node=9140
       1 4789.18 5074.73
Encroach Node=8965
       1    4910    5075
Encroach Node=8883
       1    4910    5075
Encroach Node=8500
       1 4944.19 5034.49
Encroach Node=7721
       1 4917.07 5138.25
Encroach Node=7318
       1 4931.03 5276.35
Encroach Node=6964
       1 4811.27 5258.57
Encroach Node=6506
       1  4893.7 5225.19
Encroach Node=5798
       1 4891.65 5343.21
Encroach Node=5482
       1  4665.7  5459.7
Encroach Node=4921
       1  4422.5  5047.1
Encroach Node=4442
       1 4943.43 5047.74
Encroach Node=4314
       1 4950.77 5091.66
Encroach Node=4240
       1 4950.77 5091.66
Encroach Node=4000
       1  4973.7 5225.15
Encroach Node=3633
       1    4965  5444.8
Encroach Node=3198
       1 4935.43 5504.04
Encroach Node=2500
       1 4669.41  5028.2
Encroach Node=2000
       1 4685.33 5024.81
Encroach Node=1500
       1 4745.78  5028.2
Encroach Node=1000
       1 4662.05    5040
Encroach Node=522
       1 4413.01 5115.62
BEGIN DESCRIPTION:
Floodway Run
END DESCRIPTION:
Computation Interval=1HOUR
Output Interval=1HOUR
Run HTab= 0
Run UNet= 0
Run PostProcess= 0
UNET Theta= 1
UNET Theta Warmup= 1
UNET ZTol= 0.02
UNET ZSATol= 0.05
UNET MxIter= 20
UNET MaxInSteps= 0
UNET DtIC= 0
UNET DtMin= 0
UNET MaxCRTS= 20
UNET WFStab= 2
UNET SFStab= 1
UNET WFX= 1
UNET SFX= 1
UNET DSS MLevel= 4
UNET DZMax Abort= 100
UNET Convert EG Bridges=-1
UNET Use Existing IB Tables=-1
UNET Froude Reduction=False
UNET Froude Limit= 1
UNET Froude Power= 10
Instantaneous Interval=1HOUR
Write IC File= 0
Echo Input=False
Echo Output=False
Write Detailed= 0
Detailed Automatic Start=False, 10

--- Howards Creek.f01 (steady flow) ---

Flow Title=Floodway
Number of Profiles=2
Profile Names=100-year,100-FW
River Rch & RM= Howards Creek,Reach-1,66316
    1246    1246
River Rch & RM= Howards Creek,Reach-1,62757
    1576    1576
River Rch & RM= Howards Creek,Reach-1,59438
    1810    1810
River Rch & RM= Howards Creek,Reach-1,56000
    3232    3232
River Rch & RM= Howards Creek,Reach-1,53049
    3459    3459
River Rch & RM= Howards Creek,Reach-1,50940
    3590    3590
River Rch & RM= Howards Creek,Reach-1,48326
    4079    4079
River Rch & RM= Howards Creek,Reach-1,43663
    4218    4218
River Rch & RM= Howards Creek,Reach-1,39044
    4374    4374
River Rch & RM= Howards Creek,Reach-1,36196
    4660    4660
River Rch & RM= Howards Creek,Reach-1,32025
    4934    4934
River Rch & RM= Howards Creek,Reach-1,31535
    5161    5161
River Rch & RM= Howards Creek,Reach-1,27475
    5496    5496
River Rch & RM= Howards Creek,Reach-1,17430
    5789    5789
River Rch & RM= Howards Creek,Reach-1,15500
    7308    7308
River Rch & RM= Howards Creek,Reach-1,12963
    7468    7468
River Rch & RM= Howards Creek,Reach-1,7721
    7793    7793
River Rch & RM= Howards Creek,Reach-1,2500
    8479    8479
Boundary for River Rch & Prof#=Howards Creek,Reach-1,1
Up Type=0
Dn Type=3
Dn Slope=0.001
Boundary for River Rch & Prof#=Howards Creek,Reach-1,2
Up Type=0
Dn Type=3
Dn Slope=0.001

--- Howards Creek.g01 (geometry) ---

Geom Title=Existing Conditions

River Reach=Howards Creek,Reach-1
Reach XY= 30
      1280085.38       669652.44      1281296.63       667141.56
      1282995.50       666419.75      1285537.63       662222.63
      1288043.50       656612.63      1290346.25       654311.81
      1289541.38       652789.94      1290276.38       652682.13
      1290188.50       651539.69      1291884.13       650848.69
      1291772.25       649810.13      1292689.00       648452.00
      1292779.05       647275.52      1294900.05       646464.64
      1294519.72       645455.15      1296150.58       645412.83
      1296702.88       646314.52      1297625.19       646520.69
      1299231.88       645679.88      1300627.45       643938.34
      1301372.13       644116.39      1301355.00       644801.69
      1302256.88       644878.06      1305080.25       643291.63
      1309948.38       643538.44      1311261.63       641981.31
      1314919.31       642416.13      1315847.75       641235.06
      1317953.14       640207.92      1320130.00       637598.63

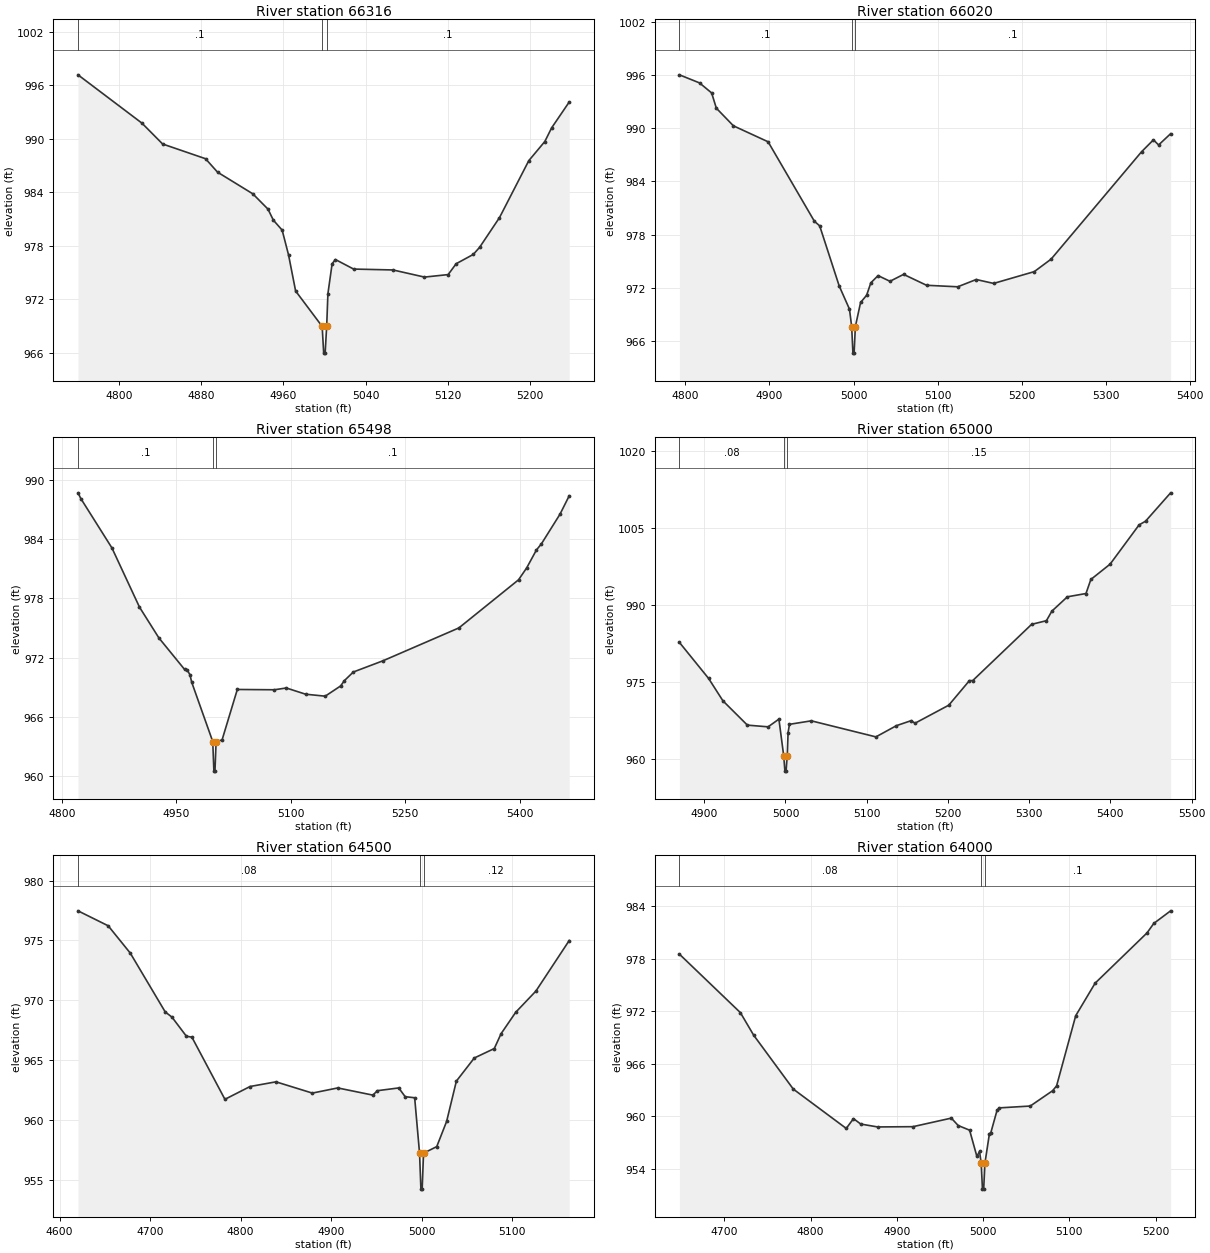
Type RM Length L Ch R = 1,66316,296,296,296
BEGIN DESCRIPTION:
Howards Creek 133.0
END DESCRIPTION:
XS GIS Cut Line= 3
      1280304.84       669552.23      1280050.50       669430.84
      1279856.85       669401.93
#Sta/Elev= 30
  4760.4  997.19  4822.6  991.77  4842.7  989.43  4884.4  987.78  4896.1  986.27
  4930.4  983.84  4945.1  982.13  4950.4  980.88  4958.9  979.77  4965.1  977.00
  4972.0  972.94  4997.8  968.97  4999.3  965.97  5000.7  965.97  5002.2  968.97
  5003.4  972.64  5007.5  976.00  5010.7  976.47  5028.4  975.40  5066.7  975.30
  5097.3  974.50  5120.3  974.78  5128.1  976.00  5144.7  977.04  5150.9  977.84
  5170.2  981.17  5198.7  987.56  5214.3  989.71  5220.9  991.24  5238.0  994.14
#Mann=3,-1,0
  4760.4     0.1       0  4997.8    0.05       0  5002.2     0.1       0
Bank Sta=4997.8,5002.2
XS Rating Curve= 0
Exp/Cntr=0.3,0.1

Type RM Length L Ch R = 1,66020,522,522,522
BEGIN DESCRIPTION:
Howards Creek 132.0
END DESCRIPTION:
XS GIS Cut Line= 3
      1280478.25       669335.46      1280362.64       669268.98
      1279943.56       669104.24
#Sta/Elev= 30
  4793.1  996.02  4817.0  995.11  4831.4  993.98  4837.0  992.26  4857.3  990.27
  4898.5  988.47  4953.5  979.51  4959.8  978.99  4983.0  972.21  4995.2  969.60
  4997.8  967.64  4999.3  964.64  5000.7  964.64  5002.2  967.64  5008.4  970.35
  5015.6  971.17  5020.6  972.57  5029.2  973.38  5043.3  972.74  5059.5  973.52
  5086.8  972.29  5123.8  972.12  5145.8  972.94  5166.5  972.50  5214.8  973.83
  5234.8  975.24  5342.3  987.35  5356.4  988.69  5362.5  988.11  5376.8  989.38
#Mann=3,-1,0
  4793.1     0.1       0  4997.8    0.05       0  5002.2     0.1       0
Bank Sta=4997.8,5002.2
XS Rating Curve= 0
Exp/Cntr=0.3,0.1

Type RM Length L Ch R = 1,65498,498,498,498
BEGIN DESCRIPTION:
Howards Creek 131.0
END DESCRIPTION:
XS GIS Cut Line= 3
      1280686.35       668865.80      1280460.91       668741.52
      1280075.00       668725.00
#Sta/Elev= 30
  4821.2  988.70  4825.0  988.11  4865.7  983.11  4901.8  977.11  4927.2  973.99
  4960.9  970.79  4963.9  970.78  4967.9  970.26  4970.2  969.50  4997.8  963.48
  4999.3  960.48  5000.7  960.48  5002.2  963.48  5010.0  963.64  5030.0  968.76
  5078.6  968.73  5094.2  968.91  5119.5  968.28  5145.2  968.08  5165.4  969.12
  5170.2  969.65  5182.0  970.53  5220.9  971.67  5320.3  975.00  5398.5  979.88
  5409.2  981.09  5421.9  982.90  5428.5  983.53  5452.8  986.53  5464.9  988.40
#Mann=3,-1,0
  4821.2     0.1       0  4997.8    0.05       0  5002.2     0.1       0
Bank Sta=4997.8,5002.2
XS Rating Curve= 0
Exp/Cntr=0.3,0.1

Type RM Length L Ch R = 1,65000,500,500,500
BEGIN DESCRIPTION:
Howards Creek 130.0
END DESCRIPTION:
XS GIS Cut Line= 3
      1280625.00       668375.00      1280510.62       668312.00
      1280075.00       668125.00
#Sta/Elev= 30
  4869.4  982.72  4905.4  975.68  4923.0  971.32  4953.1  966.58  4978.6  966.25
  4991.9  967.75  4997.8  960.61  4999.3  957.61  5000.7  957.61  5002.2  960.61
  5003.2  965.13  5004.9  966.74  5031.8  967.42  5111.3  964.29  5136.6  966.48
  5154.8  967.46  5159.4  966.95  5201.0  970.47  5226.4  975.26  5230.5  975.27
  5303.0  986.24  5321.2  986.95  5327.9  988.81  5347.0  991.61  5369.9  992.25
  5375.9  994.99  5399.6  997.98  5435.3 1005.64  5443.2 1006.35  5474.1 1011.89
#Mann=3,-1,0
  4869.4    0.08       0  4997.8    0.05       0  5002.2    0.15       0
Bank Sta=4997.8,5002.2
XS Rating Curve= 0
Exp/Cntr=0.3,0.1

Type RM Length L Ch R = 1,64500,500,500,500
BEGIN DESCRIPTION:
Howards Creek 129.0
END DESCRIPTION:
XS GIS Cut Line= 3
      1281125.00       668125.00      1280797.76       667932.51
      1280675.00       667825.00
#Sta/Elev= 30
  4620.3  977.47  4653.7  976.22  4678.1  973.94  4716.7  969.03  4724.2  968.59
  4740.1  967.00  4746.2  966.92  4782.7  961.73  4810.5  962.80  4839.1  963.19
  4879.3  962.25  4907.4  962.68  4946.2  962.08  4951.2  962.45  4974.8  962.68
  4981.9  961.95  4992.4  961.86  4997.8  957.23  4999.3  954.23  5000.7  954.23
  5002.2  957.23  5016.8  957.78  5027.7  959.88  5038.5  963.25  5058.3  965.18
  5080.4  965.97  5087.9  967.21  5104.1  969.00  5126.4  970.77  5163.2  974.99
#Mann=3,-1,0
  4620.3    0.08       0  4997.8    0.05       0  5002.2    0.12       0
Bank Sta=4997.8,5002.2
XS Rating Curve= 0
Exp/Cntr=0.3,0.1

Type RM Length L Ch R = 1,64000,369,369,369
BEGIN DESCRIPTION:
Howards Creek 128.0
END DESCRIPTION:
XS GIS Cut Line= 3
      1281322.20       667857.10      1281128.67       667563.09
      1280969.59       667414.90
#Sta/Elev= 30
  4648.0  978.53  4718.7  971.84  4734.1  969.26  4780.0  963.10  4841.4  958.60
  4849.8  959.72  4858.2  959.10  4877.8  958.77  4918.7  958.80  4963.2  959.78
  4971.2  958.93  4984.4  958.40  4992.8  955.41  4995.9  955.97  4997.8  954.66
  4999.3  951.66  5000.7  951.66  5002.2  954.66  5007.4  958.02  5008.8  958.04
  5016.2  960.67  5018.8  960.95  5054.7  961.16  5080.6  962.91  5085.2  963.46
  5107.4  971.49  5129.9  975.21  5190.0  980.95  5197.9  982.04  5217.4  983.48
#Mann=3,-1,0
  4648.0    0.08       0  4997.8    0.05       0  5002.2     0.1       0
Bank Sta=4997.8,5002.2
XS Rating Curve= 0
Exp/Cntr=0.3,0.1

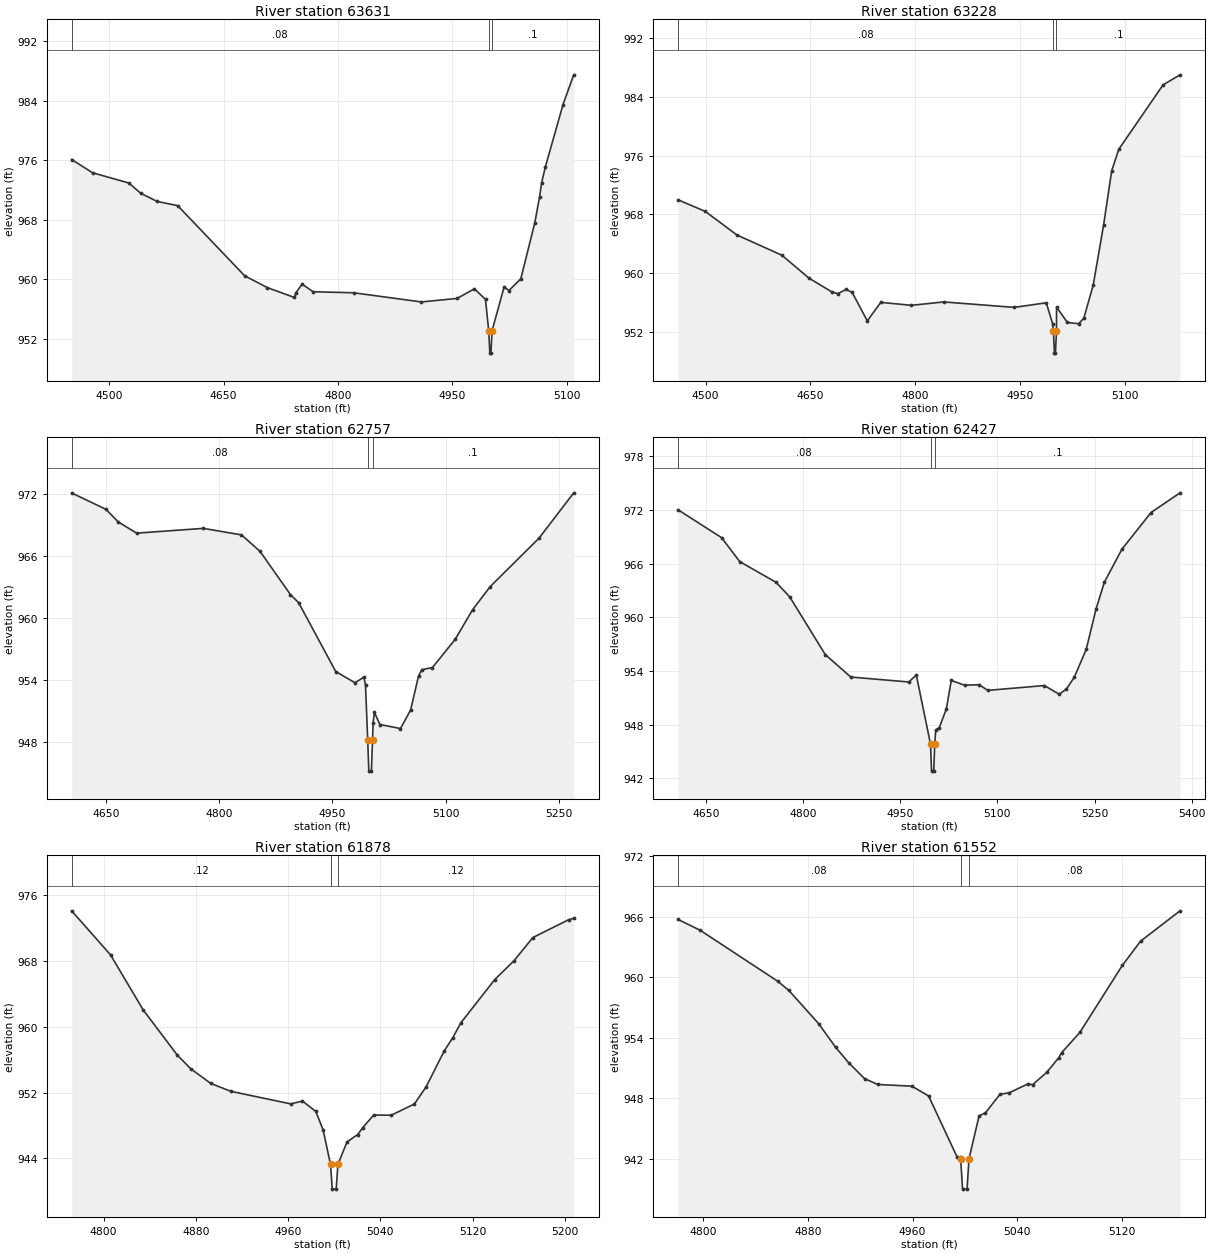
Type RM Length L Ch R = 1,63631,403,403,403
BEGIN DESCRIPTION:
Howards Creek 127.5
END DESCRIPTION:
XS GIS Cut Line= 3
      1281602.55       667623.00      1281313.53       667255.94
      1281145.90       667163.45
#Sta/Elev= 30
  4450.7  976.10  4478.1  974.32  4525.8  972.94  4541.2  971.57  4562.7  970.47
  4589.8  969.90  4677.6  960.48  4707.5  958.88  4742.9  957.56  4744.7  958.16
  4753.0  959.35  4767.5  958.33  4820.6  958.19  4909.5  956.96  4956.3  957.43
  4979.1  958.73  4993.6  957.29  4997.8  953.08  4999.3  950.08  5000.7  950.08
  5002.2  953.08  5018.0  958.98  5024.3  958.49  5039.9  960.07  5058.1  967.52
  5064.5  971.05  5067.2  972.98  5072.1  975.10  5095.3  983.49  5109.3  987.48
#Mann=3,-1,0
  4450.7    0.08       0  4997.8    0.05       0  5002.2     0.1       0
Bank Sta=4997.8,5002.2
XS Rating Curve= 0
Exp/Cntr=0.3,0.1

Type RM Length L Ch R = 1,63228,471,471,471
BEGIN DESCRIPTION:
Howards Creek 127.0
END DESCRIPTION:
XS GIS Cut Line= 3
      1281752.85       667475.59      1281530.30       666935.12
      1281458.04       666822.40
#Sta/Elev= 30
  4460.6  969.99  4499.6  968.41  4545.1  965.18  4609.3  962.43  4648.0  959.31
  4680.7  957.43  4689.4  957.19  4701.2  957.77  4709.9  957.35  4731.5  953.48
  4750.8  956.00  4794.7  955.60  4840.7  956.06  4941.7  955.32  4987.6  955.94
  4996.6  953.12  4997.8  952.08  4999.3  949.08  5000.7  949.08  5002.2  952.08
  5002.3  955.36  5017.8  953.26  5033.8  953.09  5041.3  953.83  5054.8  958.37
  5069.6  966.54  5081.2  973.94  5091.3  976.87  5154.7  985.66  5179.0  987.03
#Mann=3,-1,0
  4460.6    0.08       0  4997.8    0.05       0  5002.2     0.1       0
Bank Sta=4997.8,5002.2
XS Rating Curve= 0
Exp/Cntr=0.3,0.1

Type RM Length L Ch R = 1,62757,330,330,330
BEGIN DESCRIPTION:
Howards Creek 126.0
END DESCRIPTION:
XS GIS Cut Line= 3
      1282047.65       667253.05      1281917.59       666912.00
      1281744.17       666666.33
#Sta/Elev= 30
  4604.2  972.13  4649.8  970.54  4666.0  969.32  4690.4  968.24  4778.9  968.70
  4829.4  968.07  4854.0  966.48  4894.4  962.29  4905.2  961.51  4954.4  954.85
  4980.0  953.76  4991.7  954.30  4993.9  953.56  4996.8  948.21  4998.3  945.21
  5001.7  945.21  5003.2  948.21  5004.0  949.89  5005.7  950.90  5013.0  949.72
  5040.3  949.33  5053.8  951.14  5064.2  954.41  5068.7  955.03  5082.6  955.23
  5112.8  957.96  5135.9  960.83  5159.3  963.07  5224.0  967.75  5270.0  972.14
#Mann=3,-1,0
  4604.2    0.08       0  4996.8    0.05       0  5003.2     0.1       0
Bank Sta=4996.8,5003.2
XS Rating Curve= 0
Exp/Cntr=0.3,0.1

Type RM Length L Ch R = 1,62427,549,549,549
BEGIN DESCRIPTION:
Howards Creek 125.0
END DESCRIPTION:
XS GIS Cut Line= 3
      1282079.44       667232.81      1282157.48       666946.68
      1282270.20       666481.35
#Sta/Elev= 30
  4606.7  972.02  4674.0  968.90  4702.1  966.22  4758.2  963.90  4779.2  962.29
  4834.1  955.83  4873.6  953.31  4963.2  952.76  4974.8  953.54  4996.8  945.79
  4998.3  942.79  5001.7  942.79  5003.2  945.79  5004.8  947.41  5010.3  947.66
  5021.2  949.75  5028.8  952.93  5049.3  952.40  5071.7  952.45  5085.2  951.82
  5172.7  952.36  5195.3  951.39  5206.6  951.97  5218.8  953.29  5237.2  956.40
  5252.3  960.89  5265.2  963.91  5292.3  967.60  5337.2  971.70  5382.1  973.91
#Mann=3,-1,0
  4606.7    0.08       0  4996.8    0.05       0  5003.2     0.1       0
Bank Sta=4996.8,5003.2
XS Rating Curve= 0
Exp/Cntr=0.3,0.1

Type RM Length L Ch R = 1,61878,326,326,326
BEGIN DESCRIPTION:
Howards Creek 124.0
END DESCRIPTION:
XS GIS Cut Line= 2
      1282669.05       667149.00      1282628.59       666715.46
#Sta/Elev= 30
  4772.3  974.13  4806.0  968.77  4834.3  962.08  4864.0  956.55  4875.7  954.89
  4893.0  953.11  4910.6  952.15  4962.2  950.63  4972.5  950.97  4984.0  949.71
  4990.4  947.46  4996.8  943.25  4998.3  940.25  5001.7  940.25  5003.2  943.25
  5011.1  945.99  5020.4  946.90  5024.8  947.75  5034.3  949.27  5049.5  949.25
  5069.5  950.61  5079.7  952.70  5095.4  957.07  5102.9  958.70  5109.8  960.49
  5139.2  965.76  5155.9  968.05  5172.3  970.88  5203.2  973.04  5207.7  973.22
#Mann=3,-1,0
  4772.3    0.12       0  4996.8    0.05       0  5003.2    0.12       0
Bank Sta=4996.8,5003.2
XS Rating Curve= 0
Exp/Cntr=0.3,0.1

Type RM Length L Ch R = 1,61552,552,552,552
BEGIN DESCRIPTION:
Howards Creek 123.0
END DESCRIPTION:
XS GIS Cut Line= 3
      1283018.77       666753.04      1282900.27       666675.00
      1282669.05       666602.74
#Sta/Elev= 30
  4780.5  965.73  4797.5  964.65  4856.8  959.60  4865.4  958.68  4888.2  955.38
  4901.2  953.04  4911.1  951.52  4923.3  949.94  4933.3  949.36  4959.5  949.19
  4972.3  948.22  4994.0  942.19  4996.4  942.12  4996.8  941.98  4998.3  938.98
  5001.7  938.98  5003.2  941.98  5010.9  946.24  5015.8  946.55  5026.9  948.38
  5034.1  948.54  5048.2  949.41  5051.9  949.34  5062.7  950.56  5071.9  952.02
  5074.1  952.51  5088.1  954.53  5120.6  961.18  5134.5  963.57  5164.7  966.58
#Mann=3,-1,0
  4780.5    0.08       0  4996.8    0.05       0  5003.2    0.08       0
Bank Sta=4996.8,5003.2
XS Rating Curve= 0
Exp/Cntr=0.3,0.1

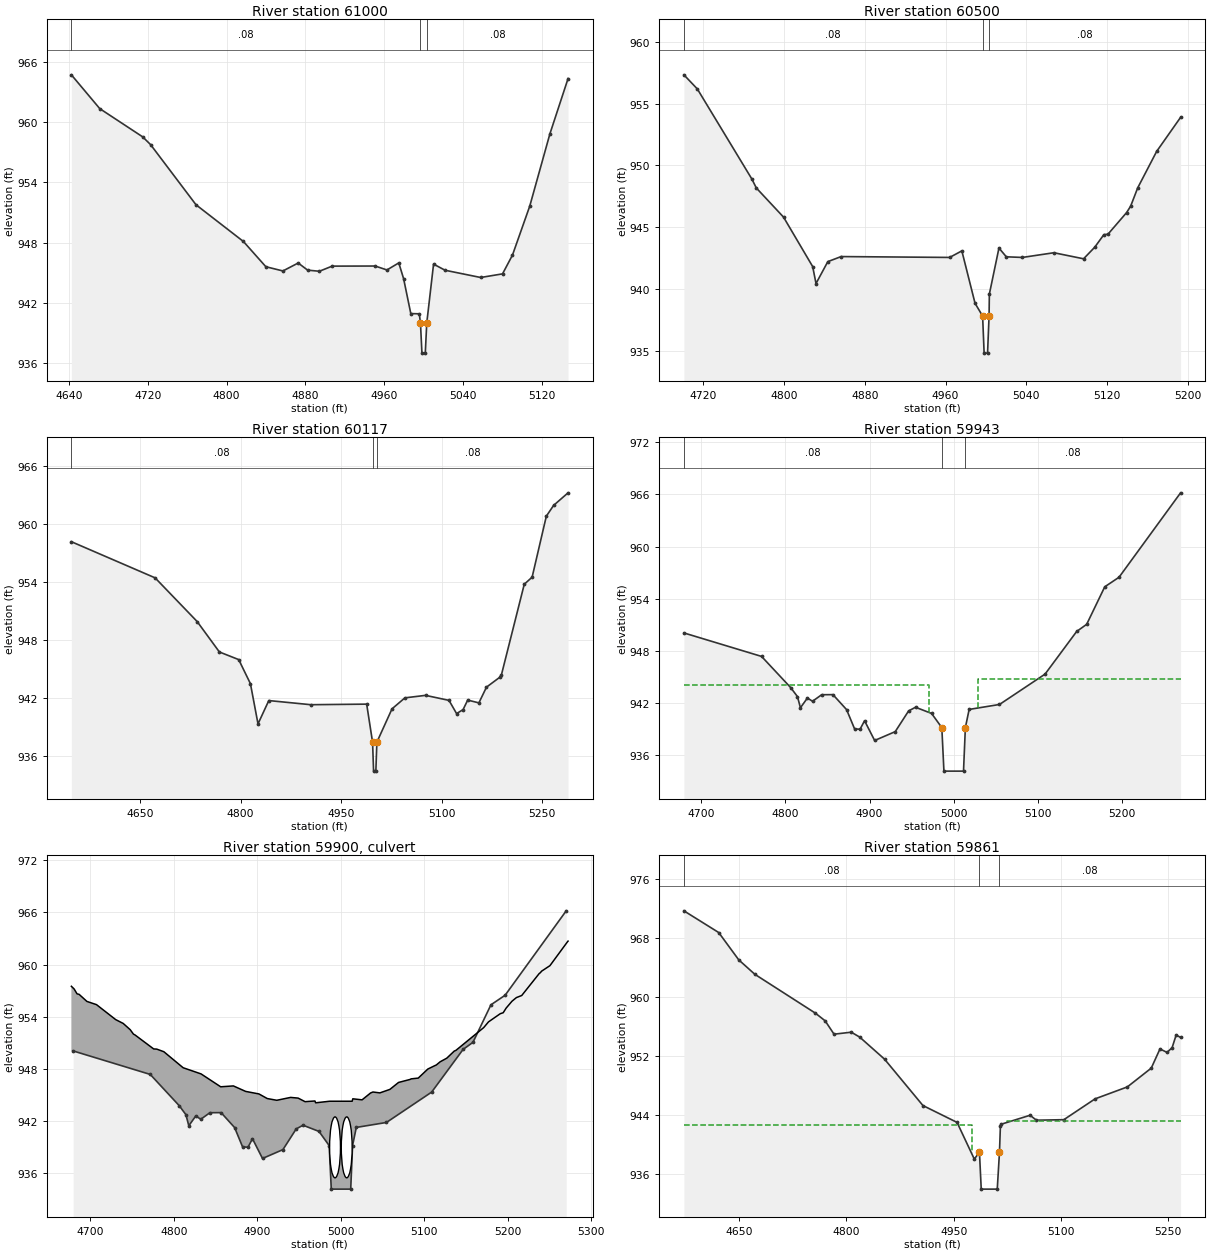
Type RM Length L Ch R = 1,61000,500,500,500
BEGIN DESCRIPTION:
Howards Creek 122.0
END DESCRIPTION:
XS GIS Cut Line= 3
      1283325.00       666475.00      1283104.58       666193.58
      1282975.00       666125.00
#Sta/Elev= 30
  4642.5  964.69  4671.3  961.33  4714.9  958.52  4722.9  957.75  4769.0  951.77
  4817.1  948.12  4839.9  945.61  4857.2  945.19  4872.7  945.98  4882.3  945.27
  4894.2  945.16  4907.2  945.67  4950.8  945.68  4962.8  945.29  4974.8  945.99
  4979.7  944.42  4987.0  940.95  4995.6  940.93  4996.8  940.02  4998.3  937.02
  5001.7  937.02  5003.2  940.02  5010.1  945.87  5021.8  945.26  5057.9  944.54
  5080.1  944.90  5090.2  946.77  5107.7  951.63  5128.2  958.83  5146.6  964.32
#Mann=3,-1,0
  4642.5    0.08       0  4996.8    0.05       0  5003.2    0.08       0
Bank Sta=4996.8,5003.2
XS Rating Curve= 0
Exp/Cntr=0.3,0.1

Type RM Length L Ch R = 1,60500,383,383,383
BEGIN DESCRIPTION:
Howards Creek 121.0
END DESCRIPTION:
XS GIS Cut Line= 3
      1283625.00       665875.00      1283349.43       665757.86
      1283175.00       665675.00
#Sta/Elev= 30
  4700.6  957.32  4713.9  956.18  4768.0  948.89  4772.4  948.17  4799.4  945.81
  4828.3  941.81  4831.6  940.44  4843.3  942.21  4856.5  942.62  4964.1  942.55
  4976.2  943.08  4989.3  938.84  4996.8  937.81  4998.3  934.81  5001.7  934.81
  5003.2  937.81  5003.5  939.59  5013.0  943.31  5020.3  942.60  5036.2  942.55
  5067.5  942.93  5096.9  942.44  5107.9  943.37  5117.0  944.39  5121.1  944.43
  5139.6  946.18  5143.6  946.70  5150.6  948.18  5169.4  951.13  5193.1  953.88
#Mann=3,-1,0
  4700.6    0.08       0  4996.8    0.05       0  5003.2    0.08       0
Bank Sta=4996.8,5003.2
XS Rating Curve= 0
Exp/Cntr=0.3,0.1

Type RM Length L Ch R = 1,60117,174,174,174
BEGIN DESCRIPTION:
Howards Creek 120.0
END DESCRIPTION:
XS GIS Cut Line= 3
      1283855.78       665677.87      1283422.24       665348.38
      1283277.73       665215.43
#Sta/Elev= 30
  4547.5  958.19  4672.4  954.44  4735.1  949.91  4768.3  946.75  4797.1  945.96
  4814.6  943.46  4825.9  939.29  4842.0  941.71  4904.7  941.28  4988.0  941.34
  4996.8  937.39  4998.3  934.39  5001.7  934.39  5003.2  937.39  5025.8  940.85
  5045.0  941.99  5075.8  942.25  5110.8  941.73  5122.1  940.36  5131.8  940.77
  5138.7  941.76  5155.4  941.47  5166.7  943.10  5186.8  944.14  5188.9  944.35
  5223.1  953.78  5234.8  954.51  5256.0  960.84  5266.9  961.96  5288.4  963.26
#Mann=3,-1,0
  4547.5    0.08       0  4996.8    0.05       0  5003.2    0.08       0
Bank Sta=4996.8,5003.2
XS Rating Curve= 0
Exp/Cntr=0.5,0.3

Type RM Length L Ch R = 1,59943,82,82,82
BEGIN DESCRIPTION:
Zur Leonard Road u/s HC
END DESCRIPTION:
XS GIS Cut Line= 5
      1283861.56       665518.91      1283659.24       665331.04
      1283563.86       665247.22      1283506.06       665209.65
      1283318.19       665105.60
#Sta/Elev= 30
  4679.2  950.08  4771.6  947.38  4806.2  943.80  4814.3  942.76  4817.8  941.48
  4826.1  942.60  4832.2  942.23  4843.1  942.98  4856.5  942.99  4872.7  941.27
  4882.2  939.06  4888.7  939.01  4894.1  939.99  4906.1  937.72  4930.6  938.74
  4946.5  941.12  4954.7  941.54  4973.8  940.83  4986.0  939.20  4988.5  934.20
  5011.8  934.20  5014.0  939.20  5018.5  941.29  5054.6  941.86  5108.8  945.35
  5146.4  950.25  5158.3  951.07  5179.8  955.38  5196.8  956.48  5270.0  966.18
#Mann=3,-1,0
  4679.2    0.08       0  4986.0    0.05       0  5014.0    0.08       0
#XS Ineff=2,0
    0.00 4971.00  944.13 5029.00    0.00  944.74
Bank Sta=4986,5014
XS Rating Curve= 0
Exp/Cntr=0.5,0.3

Type RM Length L Ch R =2,59900,,,
BEGIN DESCRIPTION:
Zur Leonard Road TOR HC
Structure ID: LDS_HC_10
Approximate Survey Structure
END DESCRIPTION:
Bridge Culvert--1,0,-1,-1,0
Deck Dist Width WeirC Skew NumUp NumDn MinLoCord MaxHiCord MaxSubmerge Is_Ogee
15.5,55,3,,60,60,,,,0,1,1,,,
  4677.1  4680.4  4683.9  4686.4  4695.7  4707.2  4730.2  4739.2  4747.6  4751.5
  4753.3  4775.7  4779.4  4787.9  4811.0  4832.5  4856.0  4871.2  4885.9  4901.8
  4911.8  4923.2  4939.8  4948.8  4957.1  4968.9  4969.8  4986.5  5013.5  5014.3
  5025.4  5035.6  5038.4  5046.7  5058.7  5069.1  5083.1  5084.1  5092.7  5104.2
  5111.9  5114.4  5118.9  5126.9  5135.8  5137.9  5171.1  5176.9  5191.0  5194.5
  5198.0  5205.0  5210.3  5216.7  5237.6  5239.1  5240.4  5250.5  5271.8  5272.2
  957.51  957.20  956.64  956.58  955.77  955.40  953.68  953.24  952.52  952.01
  951.92  950.31  950.29  949.99  948.15  947.44  945.96  946.06  945.43  945.14
  944.61  944.41  944.74  944.66  944.25  944.33  944.12  944.30  944.30  944.58
  944.46  945.25  945.36  945.26  945.66  946.46  946.81  946.87  946.96  948.00
  948.36  948.47  948.83  949.25  950.06  950.15  952.76  953.42  954.36  954.47
  955.00  955.79  956.21  956.45  958.97  959.08  959.24  959.88  962.66  962.70
  914.20  914.20  914.20  914.20  914.20  914.20  914.20  914.20  914.20  914.20
  914.20  914.20  914.20  914.20  914.20  914.20  914.20  914.20  914.20  914.20
  914.20  914.20  914.20  914.20  914.20  914.20  914.20  914.20  914.20  914.20
  914.20  914.20  914.20  914.20  914.20  914.20  914.20  914.20  914.20  914.20
  914.20  914.20  914.20  914.20  914.20  914.20  914.20  914.20  914.20  914.20
  914.20  914.20  914.20  914.20  914.20  914.20  914.20  914.20  914.20  914.20
  4677.1  4680.4  4683.9  4686.4  4695.7  4707.2  4730.2  4739.2  4747.6  4751.5
  4753.3  4775.7  4779.4  4787.9  4811.0  4832.5  4856.0  4871.2  4885.9  4901.8
  4911.8  4923.2  4939.8  4948.8  4957.1  4968.9  4969.8  4986.5  5013.5  5014.3
  5025.4  5035.6  5038.4  5046.7  5058.7  5069.1  5083.1  5084.1  5092.7  5104.2
  5111.9  5114.4  5118.9  5126.9  5135.8  5137.9  5171.1  5176.9  5191.0  5194.5
  5198.0  5205.0  5210.3  5216.7  5237.6  5239.1  5240.4  5250.5  5271.8  5272.2
  957.51  957.20  956.64  956.58  955.77  955.40  953.68  953.24  952.52  952.01
  951.92  950.31  950.29  949.99  948.15  947.44  945.96  946.06  945.43  945.14
  944.61  944.41  944.74  944.66  944.25  944.33  944.12  944.30  944.30  944.58
  944.46  945.25  945.36  945.26  945.66  946.46  946.81  946.87  946.96  948.00
  948.36  948.47  948.83  949.25  950.06  950.15  952.76  953.42  954.36  954.47
  955.00  955.79  956.21  956.45  958.97  959.08  959.24  959.88  962.66  962.70
  913.93  913.93  913.93  913.93  913.93  913.93  913.93  913.93  913.93  913.93
  913.93  913.93  913.93  913.93  913.93  913.93  913.93  913.93  913.93  913.93
  913.93  913.93  913.93  913.93  913.93  913.93  913.93  913.93  913.93  913.93
  913.93  913.93  913.93  913.93  913.93  913.93  913.93  913.93  913.93  913.93
  913.93  913.93  913.93  913.93  913.93  913.93  913.93  913.93  913.93  913.93
  913.93  913.93  913.93  913.93  913.93  913.93  913.93  913.93  913.93  913.93
Culvert=3,7,13,55,0.024,0.7,1,34,2,935.5,4993,935.23,4993,Culvert #1,0,15.5
Culvert Bottom n=0.024
Culvert Bottom Depth=0
Culvert Depth Blocked=0
Culvert=3,7,13,55,0.024,0.7,1,34,2,935.5,5007,935.23,5007,Culvert #2,0,15.5
Culvert Bottom n=0.024
Culvert Bottom Depth=0
Culvert Depth Blocked=0
BC Design=,,0,,0,,,,,,

Type RM Length L Ch R = 1,59861,220,220,220
BEGIN DESCRIPTION:
Zur Leonard Road d/s HC
END DESCRIPTION:
XS GIS Cut Line= 5
      1283948.27       665359.94      1283650.57       665215.43
      1283549.41       665146.07      1283442.47       665047.80
      1283355.77       664955.31
#Sta/Elev= 30
  4572.8  971.72  4621.5  968.77  4649.5  965.06  4672.0  963.10  4756.7  957.82
  4770.3  956.78  4782.7  954.97  4806.8  955.24  4818.5  954.58  4853.3  951.58
  4907.0  945.28  4954.7  942.99  4978.8  938.01  4986.0  938.93  4988.5  933.93
  5010.9  933.93  5014.0  938.93  5015.3  942.49  5016.0  942.73  5056.8  943.96
  5065.6  943.29  5104.0  943.36  5147.7  946.19  5192.8  947.81  5226.2  950.36
  5238.4  952.97  5248.3  952.49  5255.4  953.15  5261.0  954.85  5267.2  954.53
#Mann=3,-1,0
  4572.8    0.08       0  4986.0    0.05       0  5014.0    0.08       0
#XS Ineff=2,0
    0.00 4975.00  942.64 5025.00    0.00  943.20
Bank Sta=4986,5014
XS Rating Curve= 0
Exp/Cntr=0.5,0.3

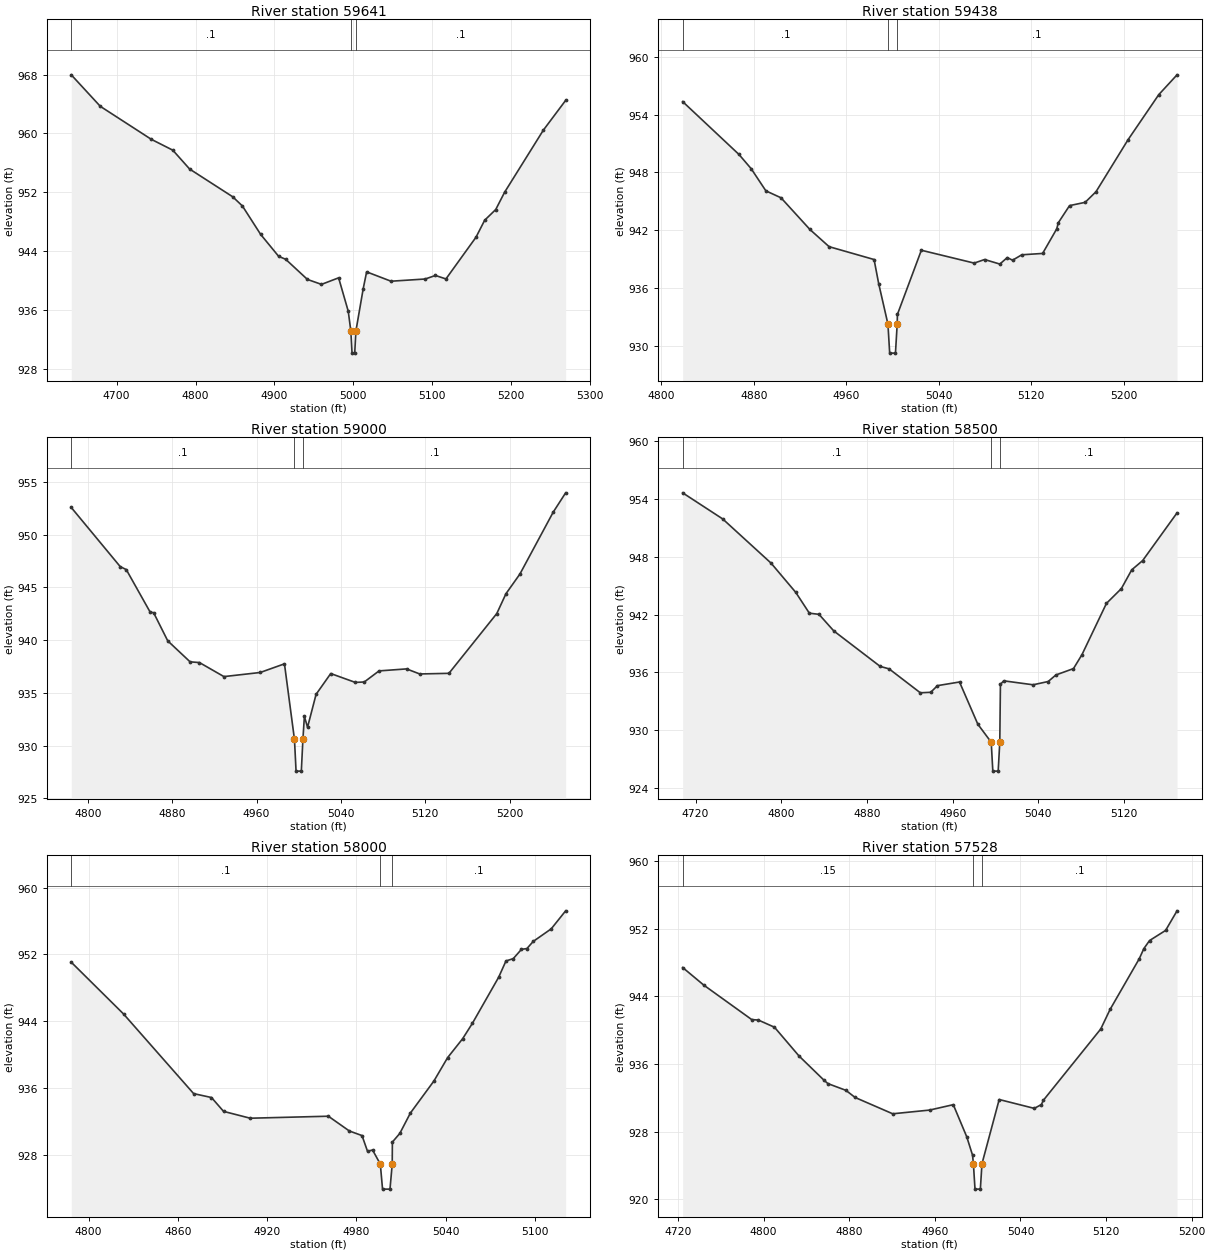
Type RM Length L Ch R = 1,59641,203,203,203
BEGIN DESCRIPTION:
Howards Creek 119.5
END DESCRIPTION:
XS GIS Cut Line= 3
      1283884.68       665183.64      1283540.74       664894.62
      1283373.11       664836.81
#Sta/Elev= 30
  4642.5  967.97  4679.3  963.69  4743.9  959.21  4771.2  957.73  4792.5  955.17
  4847.1  951.40  4859.4  950.15  4882.5  946.29  4905.3  943.31  4914.2  942.91
  4941.8  940.17  4959.6  939.50  4981.3  940.39  4993.5  935.85  4996.8  933.16
  4998.3  930.16  5001.7  930.16  5003.2  933.16  5012.5  938.94  5016.8  941.20
  5047.7  939.93  5091.0  940.23  5104.0  940.71  5117.3  940.24  5155.4  945.91
  5166.4  948.22  5180.4  949.67  5191.7  952.03  5240.7  960.45  5269.0  964.50
#Mann=3,-1,0
  4642.5     0.1       0  4996.8    0.05       0  5003.2     0.1       0
Bank Sta=4996.8,5003.2
XS Rating Curve= 0
Exp/Cntr=0.3,0.1

Type RM Length L Ch R = 1,59438,438,438,438
BEGIN DESCRIPTION:
Howards Creek 119.0
END DESCRIPTION:
XS GIS Cut Line= 3
      1283893.35       664887.39      1283636.12       664734.21
      1283511.84       664702.42
#Sta/Elev= 30
  4818.4  955.34  4867.1  949.87  4877.7  948.39  4890.4  946.10  4903.5  945.38
  4928.5  942.10  4945.1  940.32  4984.0  938.99  4988.0  936.49  4996.0  932.30
  4997.5  929.30  5002.5  929.30  5004.0  932.30  5004.2  933.31  5024.9  939.95
  5070.6  938.62  5079.6  938.99  5092.8  938.52  5099.2  939.19  5103.8  938.92
  5111.8  939.48  5129.8  939.62  5142.0  942.16  5143.4  942.80  5153.1  944.57
  5166.6  944.91  5176.0  946.01  5203.7  951.39  5230.3  956.06  5246.1  958.11
#Mann=3,-1,0
  4818.4     0.1       0  4996.0    0.05       0  5004.0     0.1       0
Bank Sta=4996,5004
XS Rating Curve= 0
Exp/Cntr=0.3,0.1

Type RM Length L Ch R = 1,59000,500,500,500
BEGIN DESCRIPTION:
Howards Creek 118.0
END DESCRIPTION:
XS GIS Cut Line= 3
      1284121.68       664598.37      1283982.52       664433.52
      1283797.97       664260.21
#Sta/Elev= 30
  4784.3  952.58  4830.7  946.98  4836.5  946.69  4859.2  942.65  4862.4  942.61
  4875.8  939.94  4897.0  937.95  4905.9  937.88  4929.1  936.55  4963.5  936.94
  4986.5  937.76  4996.0  930.59  4997.5  927.59  5002.5  927.59  5004.0  930.59
  5005.4  932.78  5008.4  931.75  5016.5  934.87  5030.4  936.84  5053.7  936.00
  5062.2  936.04  5076.2  937.09  5102.3  937.28  5114.8  936.80  5142.5  936.86
  5187.9  942.53  5196.6  944.41  5209.8  946.27  5241.4  952.14  5253.2  953.97
#Mann=3,-1,0
  4784.3     0.1       0  4996.0    0.05       0  5004.0     0.1       0
Bank Sta=4996,5004
XS Rating Curve= 0
Exp/Cntr=0.3,0.1

Type RM Length L Ch R = 1,58500,500,500,500
BEGIN DESCRIPTION:
Howards Creek 117.0
END DESCRIPTION:
XS GIS Cut Line= 3
      1284459.84       664200.96      1284234.07       664015.56
      1284089.89       663926.39
#Sta/Elev= 30
  4707.9  954.63  4745.3  951.92  4790.4  947.34  4813.5  944.30  4826.2  942.14
  4835.2  942.02  4849.0  940.30  4892.3  936.62  4900.7  936.36  4929.8  933.88
  4939.5  933.93  4945.8  934.62  4966.4  935.00  4983.5  930.62  4996.0  928.75
  4997.5  925.75  5002.5  925.75  5004.0  928.75  5004.6  934.76  5007.7  935.12
  5035.1  934.71  5049.2  935.05  5056.4  935.73  5072.8  936.39  5080.7  937.83
  5103.6  943.16  5117.5  944.69  5127.2  946.64  5137.4  947.60  5169.5  952.55
#Mann=3,-1,0
  4707.9     0.1       0  4996.0    0.05       0  5004.0     0.1       0
Bank Sta=4996,5004
XS Rating Curve= 0
Exp/Cntr=0.3,0.1

Type RM Length L Ch R = 1,58000,472,472,472
BEGIN DESCRIPTION:
Howards Creek 116.0
END DESCRIPTION:
XS GIS Cut Line= 3
      1284644.81       663614.24      1284439.89       663561.47
      1284325.00       663525.00
#Sta/Elev= 30
  4788.4  951.06  4823.5  944.86  4870.6  935.31  4882.6  934.84  4890.7  933.18
  4908.6  932.36  4961.1  932.60  4975.2  930.83  4983.7  930.28  4987.4  928.40
  4990.8  928.55  4996.0  926.86  4997.5  923.86  5002.5  923.86  5004.0  926.86
  5004.1  929.50  5009.1  930.54  5016.2  932.98  5032.0  936.82  5041.2  939.62
  5051.3  941.89  5057.8  943.72  5075.5  949.26  5080.4  951.21  5085.3  951.49
  5090.8  952.60  5094.5  952.70  5098.7  953.55  5110.8  955.06  5120.5  957.22
#Mann=3,-1,0
  4788.4     0.1       0  4996.0    0.05       0  5004.0     0.1       0
Bank Sta=4996,5004
XS Rating Curve= 0
Exp/Cntr=0.3,0.1

Type RM Length L Ch R = 1,57528,509,509,509
BEGIN DESCRIPTION:
Howards Creek 115.0
END DESCRIPTION:
XS GIS Cut Line= 3
      1284829.79       663245.74      1284598.57       663115.68
      1284402.03       663124.35
#Sta/Elev= 30
  4724.3  947.43  4744.1  945.34  4788.9  941.26  4795.0  941.21  4810.1  940.36
  4833.0  936.96  4856.5  934.07  4860.1  933.68  4876.8  932.89  4885.5  932.04
  4920.6  930.11  4955.1  930.55  4977.2  931.19  4989.8  927.38  4995.2  925.21
  4996.0  924.19  4997.5  921.19  5002.5  921.19  5004.0  924.19  5020.1  931.80
  5052.9  930.75  5059.5  931.20  5061.4  931.71  5115.0  940.15  5123.7  942.46
  5151.0  948.47  5155.3  949.67  5160.6  950.62  5175.6  951.82  5186.3  954.14
#Mann=3,-1,0
  4724.3    0.15       0  4996.0    0.05       0  5004.0     0.1       0
Bank Sta=4996,5004
XS Rating Curve= 0
Exp/Cntr=0.3,0.1