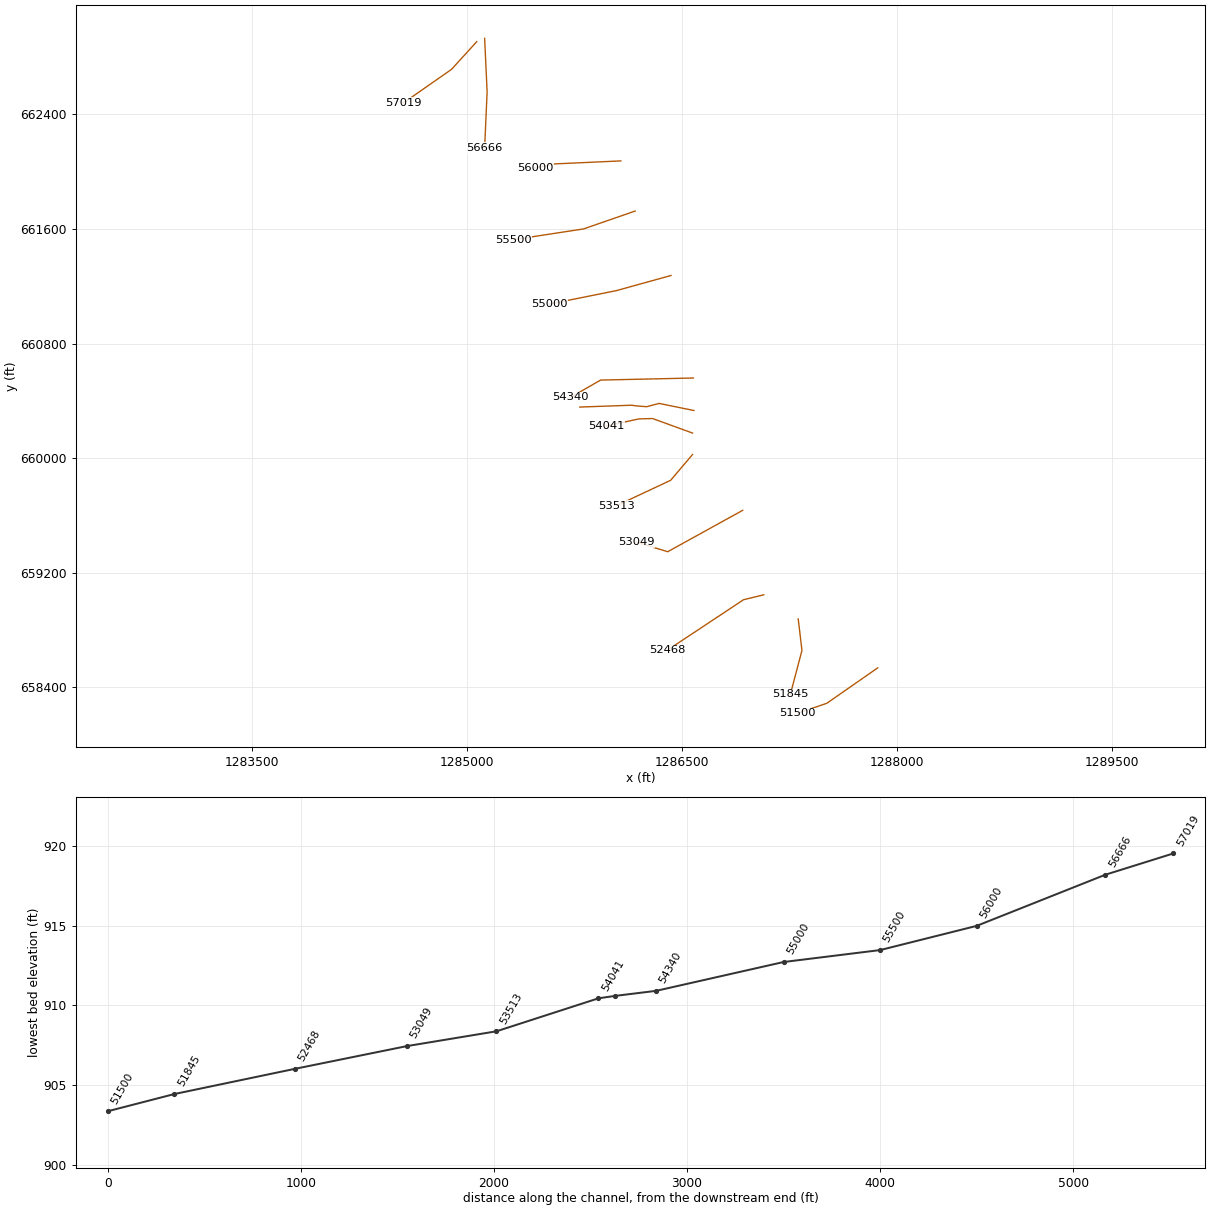
HEC-RAS study Howards Creek.prj: Howards Creek Limited Detail Study

--- Howards Creek.g01 (geometry) --- (continued)

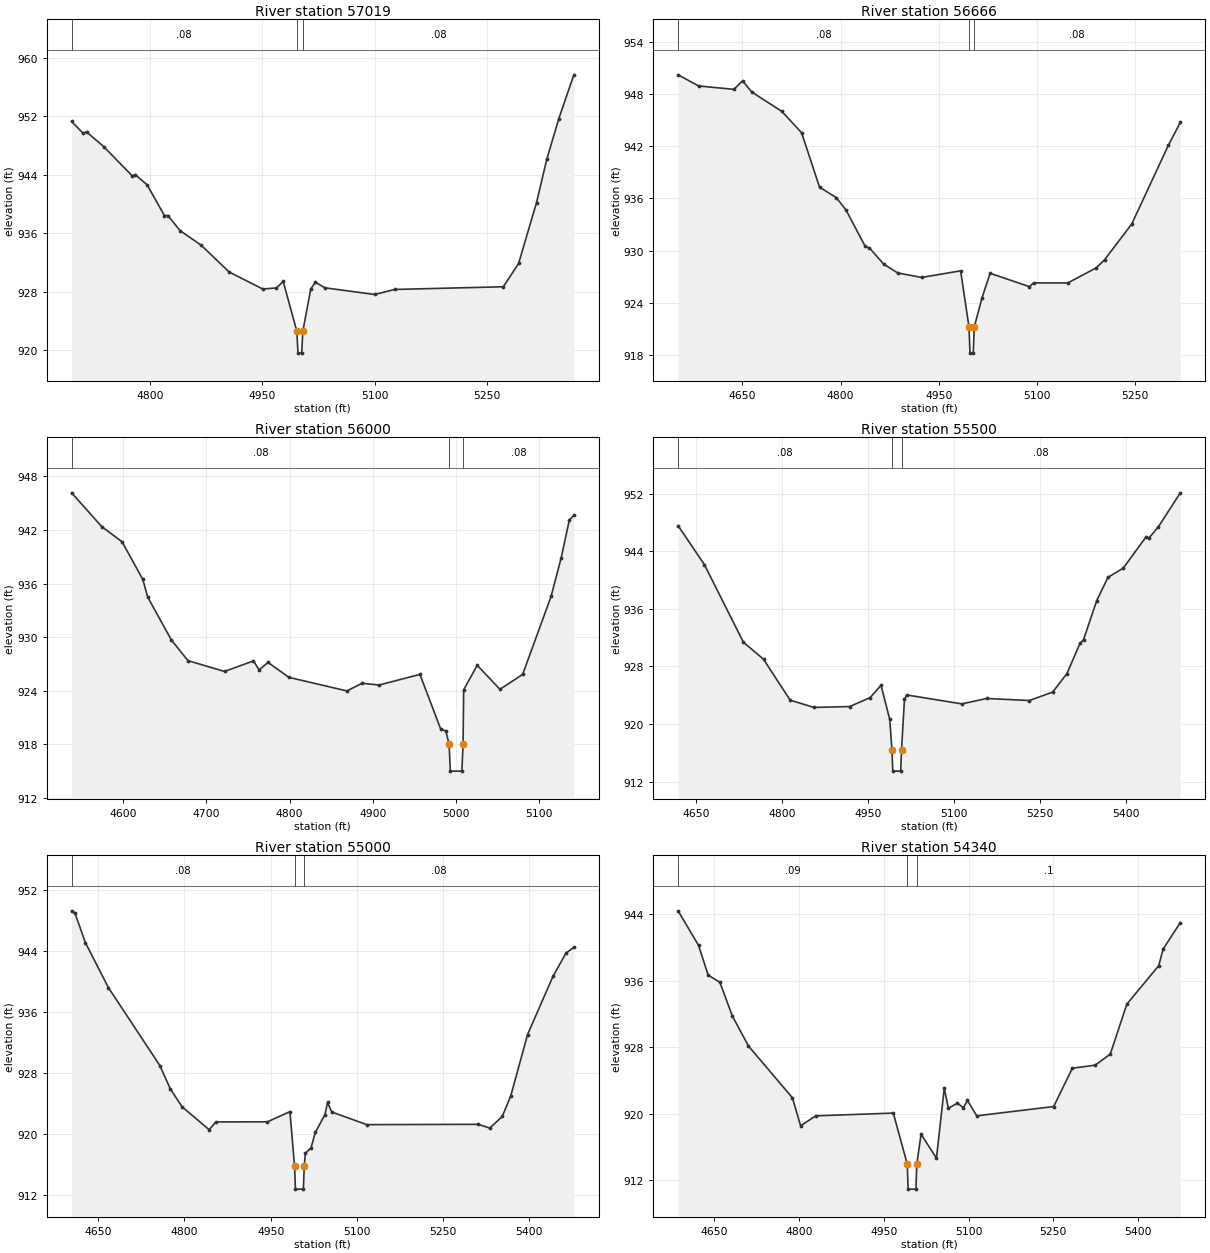
Type RM Length L Ch R = 1,57019,353,353,353
BEGIN DESCRIPTION:
Howards Creek 114.0
END DESCRIPTION:
XS GIS Cut Line= 3
      1285069.68       662907.58      1284893.37       662713.94
      1284558.10       662479.83
#Sta/Elev= 30
  4695.2  951.32  4710.3  949.71  4715.1  949.88  4737.9  947.88  4776.1  943.86
  4780.3  944.01  4796.0  942.63  4819.1  938.42  4823.8  938.42  4840.1  936.34
  4868.2  934.35  4905.5  930.68  4950.5  928.34  4968.8  928.49  4977.8  929.38
  4996.0  922.55  4997.5  919.55  5002.5  919.55  5004.0  922.55  5014.6  928.34
  5020.8  929.28  5033.3  928.51  5100.0  927.59  5126.5  928.28  5271.8  928.65
  5292.2  931.84  5316.2  940.20  5329.8  946.11  5346.0  951.72  5366.0  957.71
#Mann=3,-1,0
  4695.2    0.08       0  4996.0    0.05       0  5004.0    0.08       0
Bank Sta=4996,5004
XS Rating Curve= 0
Exp/Cntr=0.3,0.1

Type RM Length L Ch R = 1,56666,666,666,666
BEGIN DESCRIPTION:
Howards Creek 113.0
END DESCRIPTION:
XS GIS Cut Line= 3
      1285124.59       662930.70      1285141.93       662557.86
      1285124.59       662164.79
#Sta/Elev= 30
  4551.9  950.20  4583.2  948.92  4637.1  948.53  4650.2  949.51  4664.4  948.22
  4710.4  945.99  4740.4  943.54  4767.8  937.29  4793.5  936.08  4808.4  934.64
  4837.6  930.47  4844.0  930.30  4865.9  928.43  4887.1  927.43  4923.5  926.91
  4983.2  927.67  4996.0  921.21  4997.5  918.21  5002.5  918.21  5004.0  921.21
  5015.9  924.57  5028.2  927.39  5088.3  925.85  5094.5  926.28  5146.9  926.28
  5190.2  928.01  5203.0  928.94  5244.5  933.06  5300.3  942.09  5318.6  944.73
#Mann=3,-1,0
  4551.9    0.08       0  4996.0    0.05       0  5004.0    0.08       0
Bank Sta=4996,5004
XS Rating Curve= 0
Exp/Cntr=0.3,0.1

Type RM Length L Ch R = 1,56000,500,500,500
BEGIN DESCRIPTION:
Howards Creek 112.0
END DESCRIPTION:
XS GIS Cut Line= 3
      1286075.00       662075.00      1285613.45       662053.97
      1285475.00       662025.00
#Sta/Elev= 30
  4538.0  946.16  4574.1  942.38  4598.6  940.68  4623.4  936.48  4629.5  934.47
  4657.8  929.69  4677.8  927.37  4721.7  926.16  4756.5  927.34  4763.3  926.33
  4774.0  927.17  4799.1  925.50  4868.8  923.98  4887.1  924.84  4907.5  924.64
  4956.5  925.83  4981.3  919.76  4987.8  919.47  4991.6  918.00  4993.1  915.00
  5006.9  915.00  5008.4  918.00  5009.1  924.11  5025.4  926.85  5052.7  924.16
  5080.0  925.83  5114.2  934.58  5126.3  938.88  5136.0  943.09  5141.5  943.65
#Mann=3,-1,0
  4538.0    0.08       0  4991.6    0.05       0  5008.4    0.08       0
Bank Sta=4991.6,5008.4
XS Rating Curve= 0
Exp/Cntr=0.3,0.1

Type RM Length L Ch R = 1,55500,500,500,500
BEGIN DESCRIPTION:
Howards Creek 111.0
END DESCRIPTION:
XS GIS Cut Line= 3
      1286175.00       661725.00      1285814.35       661599.98
      1285325.00       661525.00
#Sta/Elev= 30
  4618.3  947.53  4664.1  942.15  4732.2  931.38  4767.5  929.00  4813.9  923.33
  4855.3  922.32  4917.8  922.44  4953.6  923.69  4972.6  925.39  4987.8  920.65
  4991.6  916.48  4993.1  913.48  5006.9  913.48  5008.4  916.48  5013.5  923.44
  5017.5  924.05  5113.7  922.81  5156.9  923.56  5231.6  923.28  5272.3  924.45
  5297.2  927.02  5319.9  931.21  5326.1  931.72  5349.1  937.12  5368.7  940.36
  5395.6  941.66  5435.5  946.01  5440.2  945.82  5456.7  947.36  5495.1  952.10
#Mann=3,-1,0
  4618.3    0.08       0  4991.6    0.05       0  5008.4    0.08       0
Bank Sta=4991.6,5008.4
XS Rating Curve= 0
Exp/Cntr=0.3,0.1

Type RM Length L Ch R = 1,55000,660,660,660
BEGIN DESCRIPTION:
Howards Creek 110.0
END DESCRIPTION:
XS GIS Cut Line= 3
      1286425.00       661275.00      1286043.10       661169.21
      1285575.00       661075.00
#Sta/Elev= 30
  4603.7  949.24  4609.7  948.89  4627.5  945.08  4667.8  939.15  4757.2  928.94
  4775.4  925.88  4796.0  923.52  4842.9  920.53  4854.7  921.55  4944.4  921.56
  4983.5  922.90  4991.6  915.73  4993.1  912.73  5006.9  912.73  5008.4  915.73
  5010.3  917.41  5020.3  918.16  5027.7  920.18  5044.4  922.50  5048.9  924.10
  5056.3  922.85  5117.2  921.19  5311.3  921.23  5331.3  920.74  5353.0  922.26
  5367.9  925.01  5397.0  933.01  5441.2  940.64  5463.8  943.69  5477.5  944.45
#Mann=3,-1,0
  4603.7    0.08       0  4991.6    0.05       0  5008.4    0.08       0
Bank Sta=4991.6,5008.4
XS Rating Curve= 0
Exp/Cntr=0.3,0.1

Type RM Length L Ch R = 1,54340,214,214,214
BEGIN DESCRIPTION:
Howards Creek 109.0
END DESCRIPTION:
XS GIS Cut Line= 3
      1286581.27       660559.27      1285933.86       660544.82
      1285725.00       660425.00
#Sta/Elev= 30
  4586.2  944.41  4622.3  940.25  4639.4  936.67  4660.1  935.81  4682.0  931.77
  4710.7  928.14  4788.5  921.90  4802.9  918.54  4829.7  919.74  4966.9  920.07
  4991.6  913.92  4993.1  910.92  5006.9  910.92  5008.4  913.92  5016.0  917.53
  5043.2  914.64  5057.0  923.05  5064.3  920.65  5080.4  921.27  5090.8  920.71
  5098.1  921.59  5114.5  919.74  5250.6  920.86  5283.6  925.47  5324.0  925.84
  5350.7  927.16  5380.0  933.18  5436.3  937.80  5444.3  939.82  5474.6  942.99
#Mann=3,-1,0
  4586.2    0.09       0  4991.6    0.05       0  5008.4     0.1       0
Bank Sta=4991.6,5008.4
XS Rating Curve= 0
Exp/Cntr=0.5,0.3

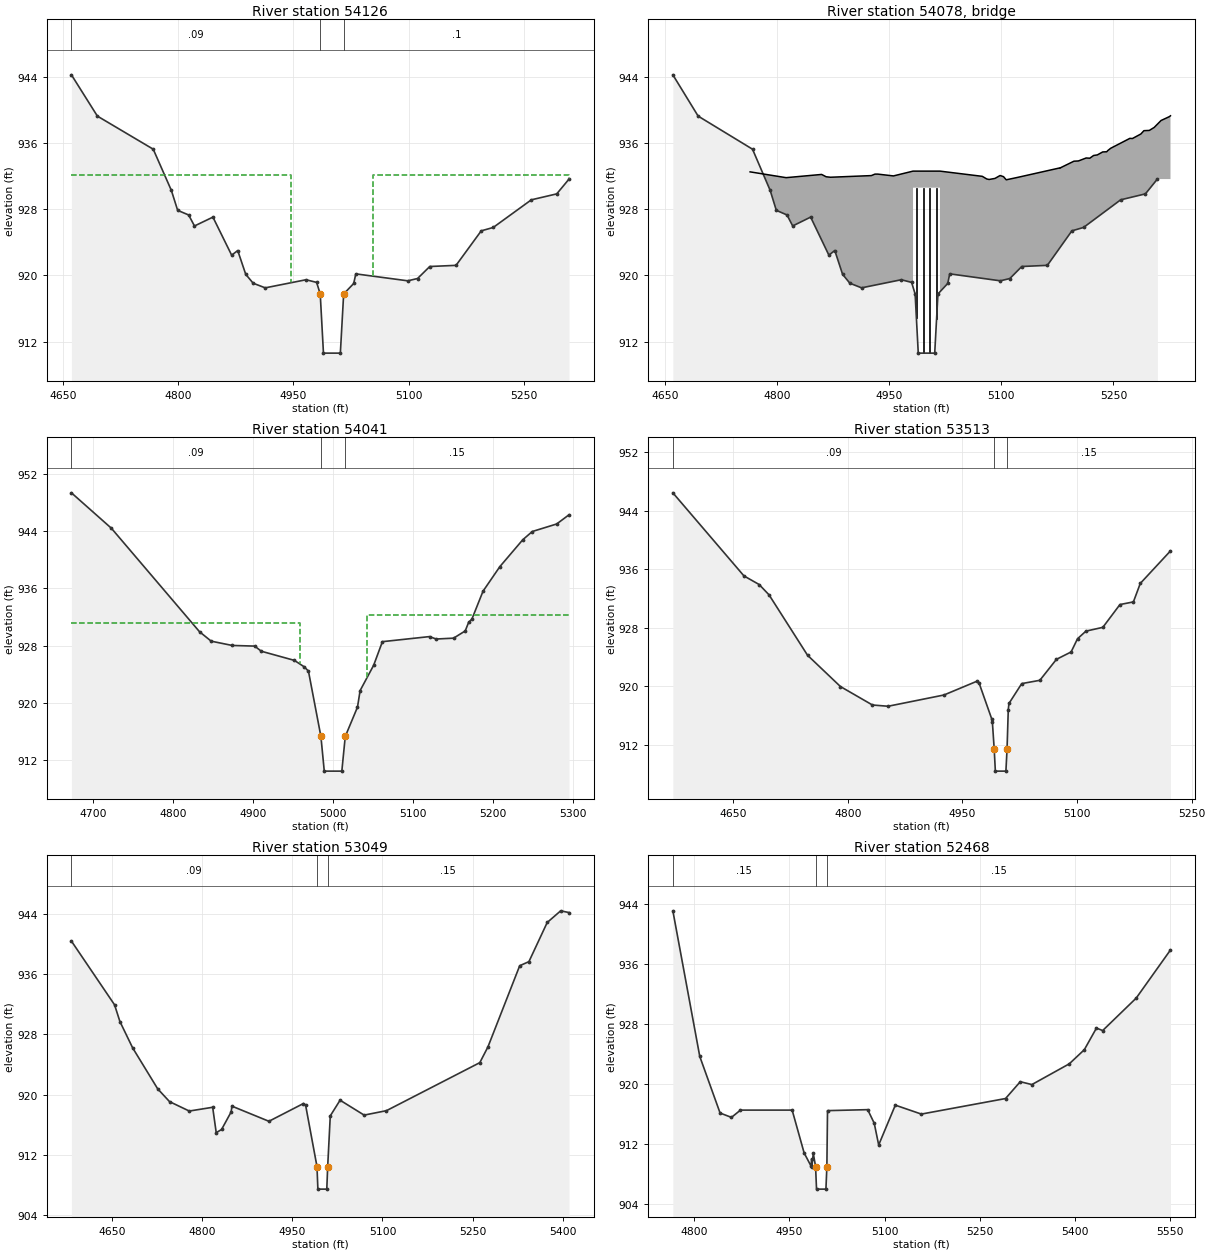
Type RM Length L Ch R = 1,54126,85,85,85
BEGIN DESCRIPTION:
Reepsville Road u/s HC
END DESCRIPTION:
XS GIS Cut Line= 6
      1286584.68       660332.32      1286341.87       660381.90
      1286255.42       660359.02      1286202.03       660362.83
      1286147.36       660369.19      1285788.87       660356.48
#Sta/Elev= 30
  4660.9  944.24  4694.7  939.25  4767.4  935.25  4791.0  930.27  4799.2  927.86
  4813.5  927.30  4821.1  925.97  4845.1  927.04  4869.5  922.44  4877.4  923.00
  4887.8  920.13  4897.5  919.05  4913.2  918.49  4966.3  919.47  4980.1  919.15
  4984.8  917.75  4989.0  910.60  5011.0  910.60  5015.3  917.75  5028.4  919.02
  5031.1  920.18  5098.8  919.34  5111.5  919.62  5127.4  921.07  5161.6  921.21
  5194.4  925.38  5210.0  925.79  5259.6  929.13  5292.7  929.85  5308.7  931.64
#Mann=3,-1,0
  4660.9    0.09       0  4984.8    0.05       0  5015.3     0.1       0
#XS Ineff=2,0
    0.00 4947.00  932.11 5053.00    0.00  932.12
Bank Sta=4984.8,5015.3
XS Rating Curve= 0
Exp/Cntr=0.5,0.3

Type RM Length L Ch R =3,54078,,,
BEGIN DESCRIPTION:
Reepsville Road TOR HC
Structure ID: LDS_HC_09
Approximate Survey Structure
END DESCRIPTION:
Bridge Culvert--1,0,-1,-1,0
Deck Dist Width WeirC Skew NumUp NumDn MinLoCord MaxHiCord MaxSubmerge Is_Ogee
35,26,3,,43,43,,,,0,1,1,,,
  4764.2  4812.3  4859.8  4865.8  4871.6  4926.3  4931.1  4934.8  4955.8  4982.0
  4982.0  5018.0  5018.0  5074.6  5080.6  5083.7  5091.6  5098.4  5103.0  5106.6
  5122.2  5178.3  5178.6  5179.9  5197.1  5203.1  5213.5  5218.3  5223.4  5228.4
  5235.6  5241.0  5242.2  5246.2  5271.9  5275.3  5286.6  5290.7  5297.9  5304.4
  5313.6  5324.8  5326.2
  932.51  931.81  932.20  931.92  931.86  932.06  932.24  932.24  932.02  932.60
  932.60  932.60  932.60  931.97  931.65  931.59  931.72  932.07  931.93  931.55
  931.85  932.99  932.95  933.04  933.80  933.83  934.19  934.16  934.49  934.56
  934.92  934.94  935.07  935.36  936.56  936.54  937.09  937.49  937.52  937.88
  938.72  939.19  939.29
  890.54  890.54  890.54  890.54  890.54  890.54  890.54  890.54  890.54  890.54
  930.60  930.60  890.54  890.54  890.54  890.54  890.54  890.54  890.54  890.54
  890.54  890.54  890.54  890.54  890.54  890.54  890.54  890.54  890.54  890.54
  890.54  890.54  890.54  890.54  890.54  890.54  890.54  890.54  890.54  890.54
  890.54  890.54  890.54
  4764.2  4812.3  4859.8  4865.8  4871.6  4926.3  4931.1  4934.8  4955.8  4982.0
  4982.0  5018.0  5018.0  5074.6  5080.6  5083.7  5091.6  5098.4  5103.0  5106.6
  5122.2  5178.3  5178.6  5179.9  5197.1  5203.1  5213.5  5218.3  5223.4  5228.4
  5235.6  5241.0  5242.2  5246.2  5271.9  5275.3  5286.6  5290.7  5297.9  5304.4
  5313.6  5324.8  5326.2
  932.51  931.81  932.20  931.92  931.86  932.06  932.24  932.24  932.02  932.60
  932.60  932.60  932.60  931.97  931.65  931.59  931.72  932.07  931.93  931.55
  931.85  932.99  932.95  933.04  933.80  933.83  934.19  934.16  934.49  934.56
  934.92  934.94  935.07  935.36  936.56  936.54  937.09  937.49  937.52  937.88
  938.72  939.19  939.29
  890.54  890.54  890.54  890.54  890.54  890.54  890.54  890.54  890.54  890.54
  930.60  930.60  890.54  890.54  890.54  890.54  890.54  890.54  890.54  890.54
  890.54  890.54  890.54  890.54  890.54  890.54  890.54  890.54  890.54  890.54
  890.54  890.54  890.54  890.54  890.54  890.54  890.54  890.54  890.54  890.54
  890.54  890.54  890.54
Pier Skew, UpSta & Num, DnSta & Num=,4986.5,2,4986.5,2,0,0,0,0,0
       1       1
  915.79  930.60
       1       1
  915.54  930.60
Pier Skew, UpSta & Num, DnSta & Num=,4995.5,2,4995.5,2,0,0,0,0,0
       1       1
  912.90  930.60
       1       1
  912.65  930.60
Pier Skew, UpSta & Num, DnSta & Num=,5004.5,2,5004.5,2,0,0,0,0,0
       1       1
  912.90  930.60
       1       1
  912.65  930.60
Pier Skew, UpSta & Num, DnSta & Num=,5013.5,2,5013.5,2,0,0,0,0,0
       1       1
  915.72  930.60
       1       1
  915.47  930.60
Abutment Skew #Up #Dn=,2,2
  4982.0  4986.0
  930.60  916.36
  4982.0  4986.0
  930.60  916.11
Abutment Skew #Up #Dn=,2,2
  5014.0  5018.0
  916.28  930.60
  5014.0  5018.0
  916.03  930.60
BR Coef=1,1,0,1.25,0,,,0.8,0,2,0,
WSPro=,,,, 1 ,,,, 0 ,,,, 0 ,,,,-1 ,-1 ,-1 , 0 , 0 , 0 , 0 , 0
BC Design=,,0,,0,,,,,,

Type RM Length L Ch R = 1,54041,528,528,528
BEGIN DESCRIPTION:
Reepsville Road d/s HC
END DESCRIPTION:
XS GIS Cut Line= 4
      1286575.00       660175.00      1286296.10       660276.39
      1286202.03       660273.85      1285975.00       660225.00
#Sta/Elev= 30
  4672.4  949.38  4722.4  944.43  4832.8  929.95  4847.4  928.63  4873.7  928.03
  4901.9  927.94  4910.2  927.22  4951.6  925.94  4963.9  925.04  4969.2  924.44
  4984.8  915.30  4989.0  910.45  5011.0  910.45  5015.3  915.30  5030.6  919.40
  5033.9  921.72  5050.9  925.27  5061.8  928.56  5120.8  929.27  5129.1  928.93
  5150.9  929.05  5165.5  930.06  5169.8  931.27  5173.8  931.70  5187.8  935.62
  5208.9  939.06  5237.6  942.82  5249.5  943.97  5280.0  945.02  5295.5  946.31
#Mann=3,-1,0
  4672.4    0.09       0  4984.8    0.05       0  5015.3    0.15       0
#XS Ineff=2,0
    0.00 4958.00  931.21 5042.00    0.00  932.26
Bank Sta=4984.8,5015.3
XS Rating Curve= 0
Exp/Cntr=0.5,0.3

Type RM Length L Ch R = 1,53513,464,464,464
BEGIN DESCRIPTION:
Howards Creek 107.0
END DESCRIPTION:
XS GIS Cut Line= 3
      1286575.00       660025.00      1286422.30       659845.09
      1286046.57       659668.79
#Sta/Elev= 30
  4571.2  946.47  4664.2  935.10  4684.1  933.92  4697.0  932.51  4747.4  924.24
  4790.4  919.96  4832.3  917.43  4852.8  917.26  4925.9  918.80  4968.9  920.68
  4971.8  920.44  4988.4  915.51  4989.2  915.12  4991.6  911.38  4993.1  908.38
  5006.9  908.38  5008.4  911.38  5010.0  916.79  5010.9  917.64  5027.6  920.36
  5051.3  920.81  5073.0  923.68  5092.2  924.69  5100.6  926.50  5111.6  927.54
  5133.7  928.06  5156.1  931.18  5173.7  931.54  5182.7  934.07  5222.2  938.52
#Mann=3,-1,0
  4571.2    0.09       0  4991.6    0.05       0  5008.4    0.15       0
Bank Sta=4991.6,5008.4
XS Rating Curve= 0
Exp/Cntr=0.3,0.1

Type RM Length L Ch R = 1,53049,581,581,581
BEGIN DESCRIPTION:
Howards Creek 106.0
END DESCRIPTION:
XS GIS Cut Line= 3
      1286925.20       659635.55      1286402.07       659346.53
      1286182.42       659413.00
#Sta/Elev= 30
  4582.9  940.39  4654.6  931.93  4663.5  929.71  4684.6  926.22  4726.3  920.77
  4746.0  919.07  4778.8  917.82  4817.7  918.32  4823.6  914.95  4832.5  915.37
  4848.4  917.70  4849.7  918.47  4911.2  916.46  4968.6  918.82  4972.1  918.64
  4991.1  910.45  4992.6  907.45  5007.4  907.45  5008.9  910.45  5013.2  917.18
  5029.5  919.26  5069.5  917.28  5106.6  917.87  5261.8  924.25  5275.3  926.34
  5328.1  937.12  5343.4  937.66  5373.8  942.86  5396.2  944.41  5410.1  944.18
#Mann=3,-1,0
  4582.9    0.09       0  4991.1    0.05       0  5008.9    0.15       0
Bank Sta=4991.1,5008.9
XS Rating Curve= 0
Exp/Cntr=0.3,0.1

Type RM Length L Ch R = 1,52468,623,623,623
BEGIN DESCRIPTION:
Howards Creek 105.0
END DESCRIPTION:
XS GIS Cut Line= 3
      1287072.61       659045.94      1286930.99       659011.26
      1286399.18       658658.65
#Sta/Elev= 30
  4766.3  943.07  4808.7  923.68  4840.7  916.15  4858.6  915.57  4872.8  916.54
  4954.2  916.54  4973.1  910.83  4984.2  909.05  4985.0  910.07  4985.1  909.02
  4987.5  910.78  4991.1  909.02  4992.6  906.02  5007.4  906.02  5008.9  909.02
  5009.9  916.47  5073.2  916.60  5083.5  914.79  5090.5  911.90  5116.7  917.20
  5157.7  916.01  5290.3  918.08  5313.5  920.32  5331.8  919.94  5390.7  922.70
  5414.4  924.58  5433.5  927.46  5443.3  927.13  5496.1  931.45  5550.1  937.86
#Mann=3,-1,0
  4766.3    0.15       0  4991.1    0.05       0  5008.9    0.15       0
Bank Sta=4991.1,5008.9
XS Rating Curve= 0
Exp/Cntr=0.3,0.1

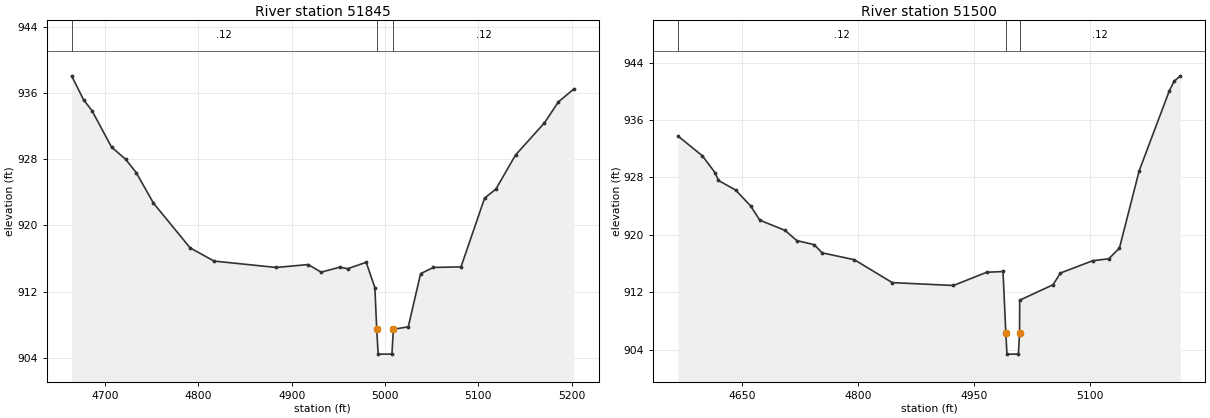
Type RM Length L Ch R = 1,51845,345,345,345
BEGIN DESCRIPTION:
Howards Creek 104.0
END DESCRIPTION:
XS GIS Cut Line= 3
      1287312.50       658876.86      1287338.51       658657.21
      1287257.58       658350.84
#Sta/Elev= 30
  4664.2  938.06  4677.0  935.16  4685.9  933.87  4706.9  929.46  4722.1  927.97
  4733.3  926.38  4751.9  922.68  4791.1  917.28  4816.8  915.68  4883.3  914.91
  4917.5  915.26  4931.6  914.34  4951.6  914.95  4959.9  914.76  4979.8  915.53
  4989.1  912.48  4991.1  907.44  4992.6  904.44  5007.4  904.44  5008.9  907.44
  5024.9  907.74  5038.1  914.16  5051.8  914.91  5081.4  914.98  5106.7  923.29
  5118.8  924.38  5139.8  928.49  5170.8  932.38  5185.8  934.92  5202.3  936.47
#Mann=3,-1,0
  4664.2    0.12       0  4991.1    0.05       0  5008.9    0.12       0
Bank Sta=4991.1,5008.9
XS Rating Curve= 0
Exp/Cntr=0.3,0.1

Type RM Length L Ch R = 1,51500,560,560,560
BEGIN DESCRIPTION:
Howards Creek 103.0
END DESCRIPTION:
XS GIS Cut Line= 3
      1287867.42       658535.82      1287511.98       658288.37
      1287306.72       658217.89
#Sta/Elev= 30
  4566.9  933.75  4598.3  931.01  4615.1  928.60  4619.0  927.58  4641.3  926.24
  4660.8  924.02  4672.6  922.04  4705.5  920.60  4720.5  919.19  4743.0  918.62
  4753.4  917.48  4795.1  916.52  4844.1  913.33  4923.3  912.93  4966.3  914.77
  4987.5  914.88  4991.1  906.36  4992.6  903.36  5007.4  903.36  5008.9  906.36
  5009.1  910.88  5052.2  913.03  5061.9  914.67  5103.8  916.39  5124.4  916.65
  5138.2  918.14  5163.8  928.93  5202.7  940.05  5208.9  941.38  5217.0  942.16
#Mann=3,-1,0
  4566.9    0.12       0  4991.1    0.05       0  5008.9    0.12       0
Bank Sta=4991.1,5008.9
XS Rating Curve= 0
Exp/Cntr=0.3,0.1