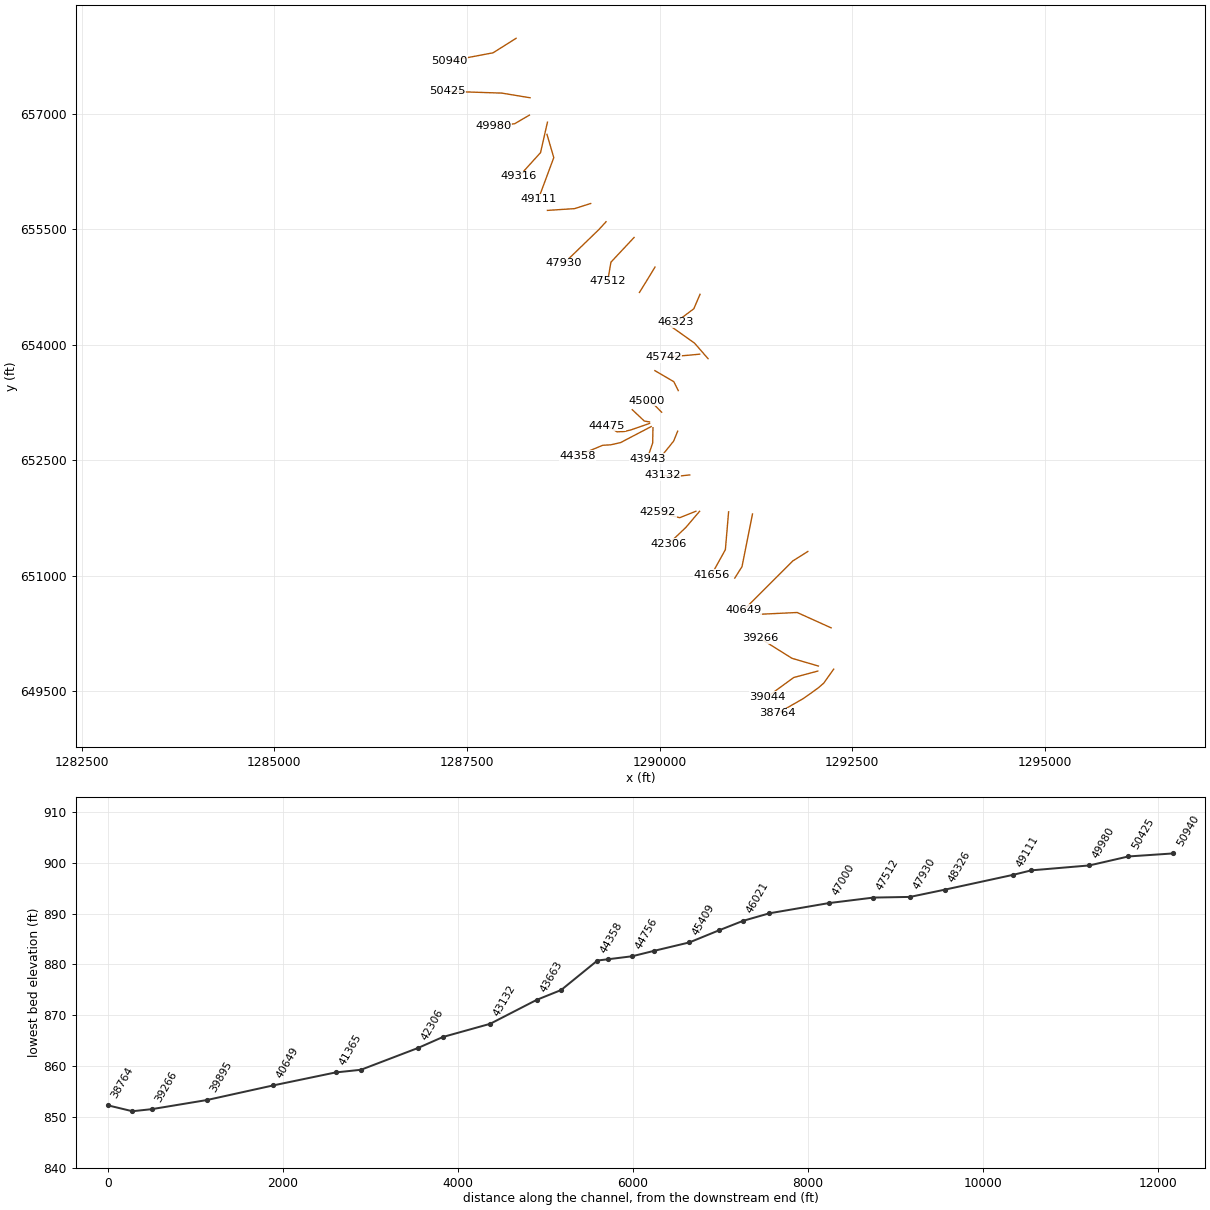
HEC-RAS study Howards Creek.prj: Howards Creek Limited Detail Study

--- Howards Creek.g01 (geometry) --- (continued)

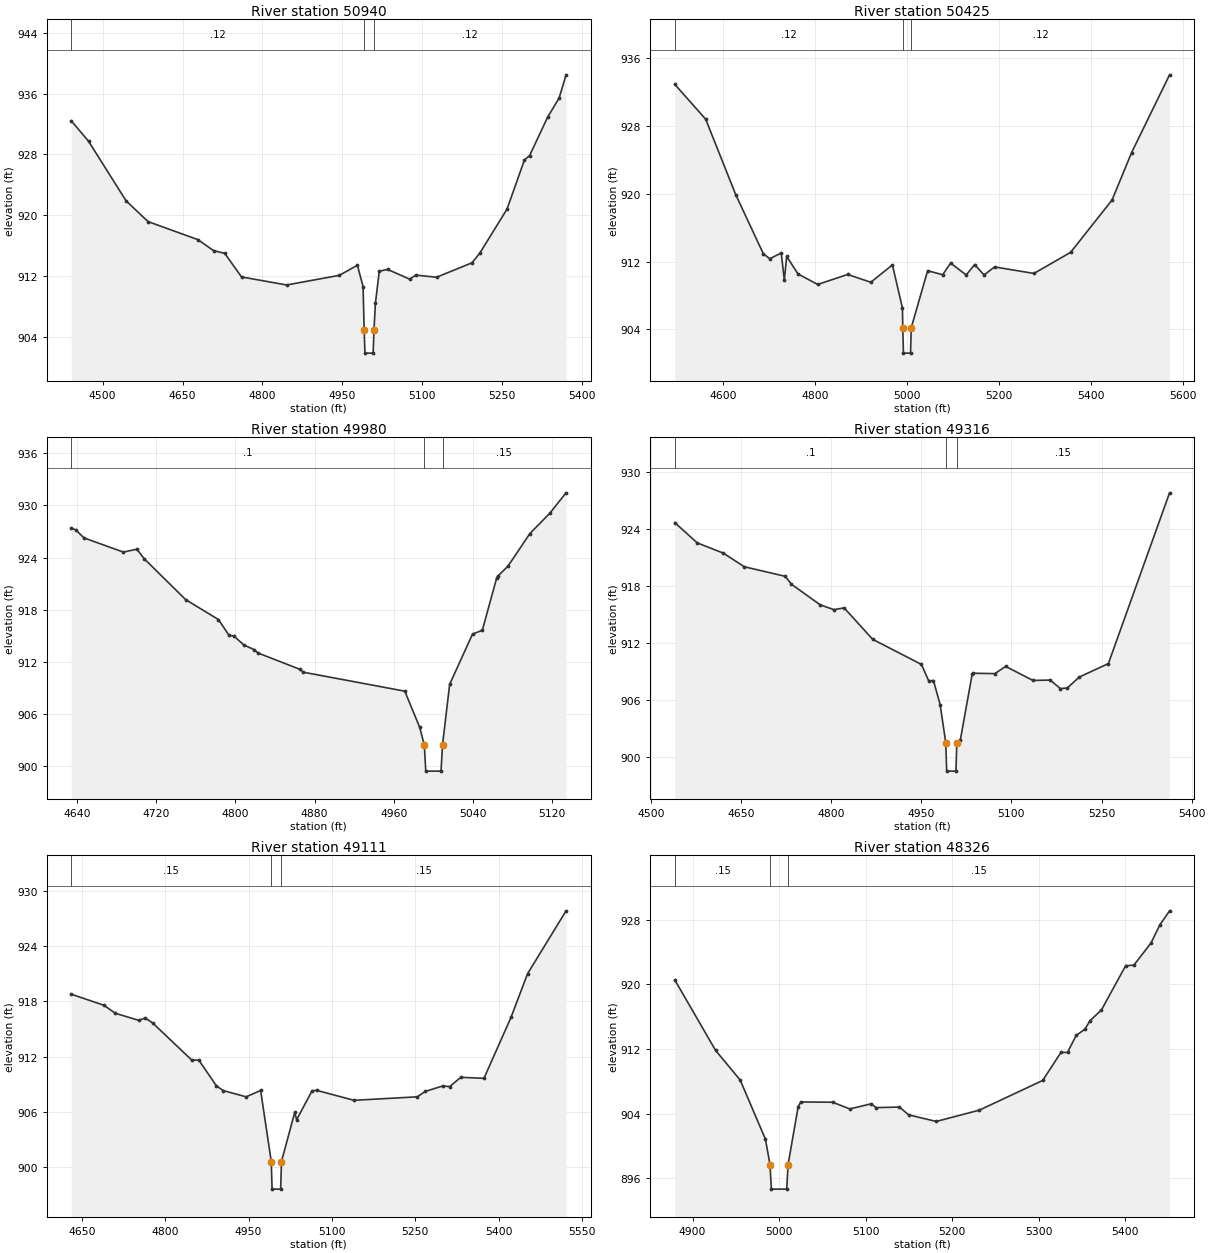
Type RM Length L Ch R = 1,50940,515,515,515
BEGIN DESCRIPTION:
Howards Creek 102.0
END DESCRIPTION:
XS GIS Cut Line= 3
      1288136.21       657979.45      1287838.52       657791.58
      1287272.03       657684.64
#Sta/Elev= 30
  4441.2  932.42  4473.6  929.73  4544.0  921.88  4585.3  919.14  4678.6  916.77
  4708.2  915.32  4729.3  914.95  4760.7  911.85  4845.3  910.79  4944.3  912.06
  4978.1  913.39  4988.8  910.57  4990.8  904.81  4992.3  901.81  5007.7  901.81
  5009.2  904.81  5011.9  908.37  5019.2  912.61  5034.9  912.84  5076.4  911.55
  5087.5  912.09  5126.6  911.81  5193.1  913.71  5207.8  914.98  5258.8  920.77
  5291.5  927.24  5301.4  927.85  5334.9  932.87  5356.8  935.44  5369.7  938.48
#Mann=3,-1,0
  4441.2    0.12       0  4990.8    0.05       0  5009.2    0.12       0
Bank Sta=4990.8,5009.2
XS Rating Curve= 0
Exp/Cntr=0.3,0.1

Type RM Length L Ch R = 1,50425,445,445,445
BEGIN DESCRIPTION:
Howards Creek 101.0
END DESCRIPTION:
XS GIS Cut Line= 3
      1288318.30       657207.75      1287951.24       657268.45
      1287248.91       657291.57
#Sta/Elev= 30
  4495.5  932.92  4562.7  928.80  4627.8  919.92  4687.8  912.94  4701.8  912.35
  4726.8  913.02  4733.5  909.81  4738.6  912.62  4763.2  910.55  4806.0  909.31
  4871.0  910.49  4921.4  909.57  4968.3  911.62  4990.1  906.52  4990.8  904.21
  4992.3  901.21  5007.7  901.21  5009.2  904.21  5044.8  910.93  5077.5  910.46
  5094.7  911.83  5128.6  910.43  5146.9  911.66  5167.4  910.43  5190.2  911.38
  5275.7  910.61  5355.4  913.10  5445.4  919.27  5487.9  924.87  5570.3  934.04
#Mann=3,-1,0
  4495.5    0.12       0  4990.8    0.05       0  5009.2    0.12       0
Bank Sta=4990.8,5009.2
XS Rating Curve= 0
Exp/Cntr=0.3,0.1

Type RM Length L Ch R = 1,49980,664,664,664
BEGIN DESCRIPTION:
Howards Creek 100.0
END DESCRIPTION:
XS GIS Cut Line= 3
      1288309.63       656982.32      1288115.98       656869.60
      1287841.41       656843.58
#Sta/Elev= 30
  4634.2  927.39  4638.7  927.18  4647.0  926.26  4686.8  924.63  4700.5  924.96
  4707.8  923.87  4749.8  919.16  4782.9  916.87  4793.6  915.05  4798.5  914.97
  4808.7  913.94  4819.2  913.40  4822.8  913.03  4865.2  911.15  4868.7  910.82
  4971.1  908.64  4986.2  904.47  4990.8  902.45  4992.3  899.45  5007.7  899.45
  5009.2  902.45  5016.4  909.42  5039.5  915.20  5049.4  915.64  5063.8  921.60
  5065.1  921.87  5075.4  923.02  5097.4  926.75  5117.4  929.07  5134.0  931.44
#Mann=3,-1,0
  4634.2     0.1       0  4990.8    0.05       0  5009.2    0.15       0
Bank Sta=4990.8,5009.2
XS Rating Curve= 0
Exp/Cntr=0.3,0.1

Type RM Length L Ch R = 1,49316,205,205,205
BEGIN DESCRIPTION:
Howards Creek 99.0
END DESCRIPTION:
XS GIS Cut Line= 3
      1288543.74       656891.27      1288454.14       656495.31
      1288173.79       656186.06
#Sta/Elev= 30
  4539.8  924.71  4577.1  922.57  4620.5  921.49  4655.4  920.05  4723.6  919.04
  4734.0  918.20  4782.0  916.02  4804.9  915.52  4821.6  915.71  4869.2  912.39
  4950.3  909.74  4962.4  908.01  4970.3  908.04  4981.4  905.51  4990.8  901.48
  4992.3  898.48  5007.7  898.48  5009.2  901.48  5015.0  901.76  5034.8  908.74
  5036.1  908.81  5072.5  908.77  5090.5  909.53  5135.9  908.05  5164.6  908.09
  5181.5  907.19  5193.0  907.25  5213.0  908.41  5261.4  909.83  5363.2  927.85
#Mann=3,-1,0
  4539.8     0.1       0  4990.8    0.05       0  5009.2    0.15       0
Bank Sta=4990.8,5009.2
XS Rating Curve= 0
Exp/Cntr=0.3,0.1

Type RM Length L Ch R = 1,49111,785,785,785
BEGIN DESCRIPTION:
Howards Creek 98.0
END DESCRIPTION:
XS GIS Cut Line= 3
      1288537.45       656732.56      1288626.03       656430.74
      1288425.24       655891.25
#Sta/Elev= 30
  4631.0  918.79  4690.1  917.58  4710.0  916.72  4752.4  915.95  4764.1  916.20
  4777.4  915.67  4847.4  911.65  4860.6  911.62  4892.1  908.83  4904.4  908.32
  4945.6  907.64  4971.7  908.33  4990.8  900.61  4992.3  897.61  5007.7  897.61
  5009.2  900.61  5033.0  905.94  5036.5  905.16  5064.2  908.29  5072.2  908.35
  5139.6  907.26  5253.5  907.64  5268.1  908.23  5299.3  908.82  5311.8  908.75
  5331.8  909.76  5373.5  909.65  5422.2  916.28  5451.9  921.01  5521.2  927.85
#Mann=3,-1,0
  4631.0    0.15       0  4990.8    0.05       0  5009.2    0.15       0
Bank Sta=4990.8,5009.2
XS Rating Curve= 0
Exp/Cntr=0.3,0.1

Type RM Length L Ch R = 1,48326,396,396,396
BEGIN DESCRIPTION:
Howards Creek 97.0
END DESCRIPTION:
XS GIS Cut Line= 3
      1289104.44       655834.89      1288896.34       655768.42
      1288543.74       655745.30
#Sta/Elev= 30
  4879.5  920.56  4926.6  911.85  4955.1  908.17  4984.3  900.85  4989.6  897.68
  4991.1  894.68  5008.9  894.68  5010.4  897.68  5022.1  904.88  5025.1  905.46
  5061.9  905.43  5081.8  904.60  5106.5  905.23  5112.1  904.76  5139.0  904.83
  5150.0  903.86  5181.7  903.05  5231.5  904.45  5304.7  908.12  5325.8  911.59
  5333.4  911.59  5343.4  913.69  5353.6  914.47  5359.3  915.50  5372.6  916.84
  5400.6  922.32  5410.0  922.37  5429.8  925.11  5440.1  927.36  5451.3  929.10
#Mann=3,-1,0
  4879.5    0.15       0  4989.6    0.05       0  5010.4    0.15       0
Bank Sta=4989.6,5010.4
XS Rating Curve= 0
Exp/Cntr=0.3,0.1

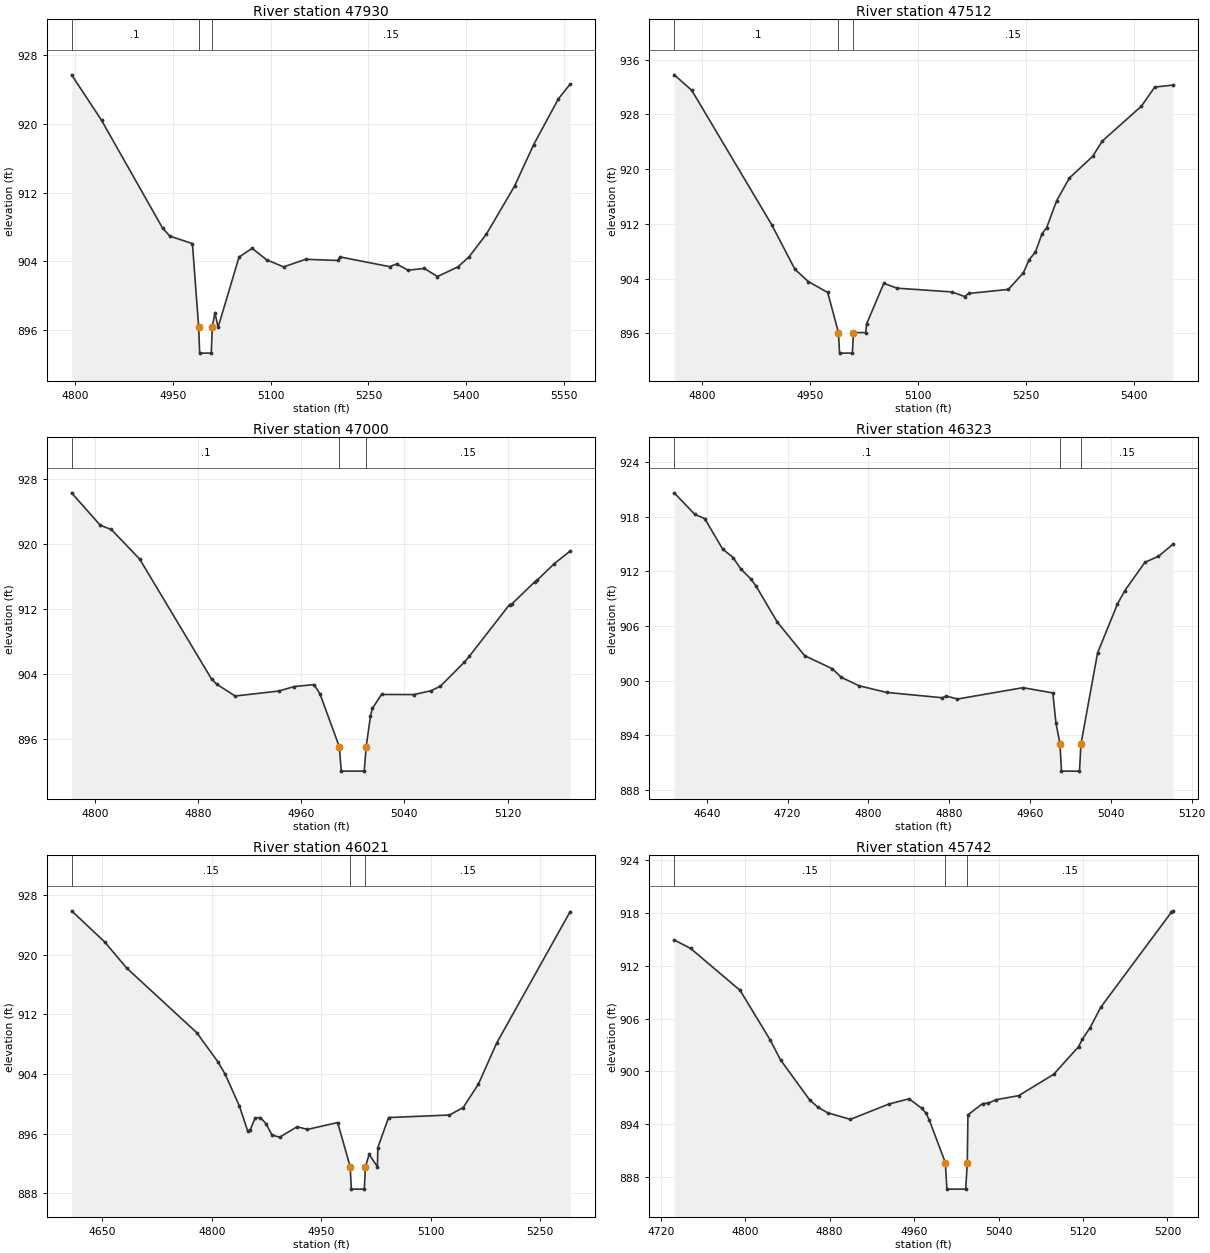
Type RM Length L Ch R = 1,47930,418,418,418
BEGIN DESCRIPTION:
Howards Creek 96.0
END DESCRIPTION:
XS GIS Cut Line= 3
      1289303.87       655597.89      1289211.38       655496.74
      1288760.50       655060.31
#Sta/Elev= 30
  4794.7  925.73  4840.6  920.43  4934.2  907.85  4945.4  906.91  4980.0  906.04
  4989.6  896.26  4991.1  893.26  5008.9  893.26  5010.4  896.26  5014.5  897.99
  5019.3  896.26  5051.5  904.47  5071.6  905.49  5093.7  904.15  5119.9  903.32
  5153.7  904.21  5202.9  904.07  5206.1  904.49  5282.3  903.35  5293.1  903.66
  5310.6  902.94  5335.5  903.14  5355.8  902.20  5386.7  903.30  5404.2  904.49
  5430.9  907.16  5474.0  912.75  5503.2  917.57  5541.3  922.94  5559.3  924.65
#Mann=3,-1,0
  4794.7     0.1       0  4989.6    0.05       0  5010.4    0.15       0
Bank Sta=4989.6,5010.4
XS Rating Curve= 0
Exp/Cntr=0.3,0.1

Type RM Length L Ch R = 1,47512,512,512,512
BEGIN DESCRIPTION:
Howards Creek 95.0
END DESCRIPTION:
XS GIS Cut Line= 3
      1289668.04       655394.13      1289367.45       655073.32
      1289325.00       654825.00
#Sta/Elev= 30
  4761.8  933.79  4786.1  931.53  4897.0  911.89  4929.1  905.40  4947.7  903.59
  4974.7  901.99  4989.6  896.13  4991.1  893.13  5008.9  893.13  5010.4  896.13
  5027.4  896.13  5028.6  897.39  5052.5  903.32  5071.0  902.62  5147.0  902.07
  5164.6  901.40  5170.3  901.85  5225.3  902.44  5246.1  904.86  5253.9  906.74
  5262.9  907.93  5272.0  910.58  5278.4  911.46  5292.2  915.39  5309.9  918.71
  5342.4  921.90  5355.3  924.09  5409.9  929.22  5428.3  932.00  5453.4  932.29
#Mann=3,-1,0
  4761.8     0.1       0  4989.6    0.05       0  5010.4    0.15       0
Bank Sta=4989.6,5010.4
XS Rating Curve= 0
Exp/Cntr=0.3,0.1

Type RM Length L Ch R = 1,47000,677,677,677
BEGIN DESCRIPTION:
Howards Creek 94.0
END DESCRIPTION:
XS GIS Cut Line= 3
      1289939.72       655009.73      1289826.19       654823.60
      1289737.40       654680.25
#Sta/Elev= 29
  4782.0  926.35  4804.3  922.34  4812.8  921.83  4834.8  918.18  4890.5  903.40
  4894.6  902.75  4908.8  901.30  4942.5  901.91  4954.7  902.47  4970.0  902.71
  4974.6  901.56  4989.6  895.04  4991.1  892.04  5008.9  892.04  5010.4  895.04
  5013.7  898.78  5015.2  899.77  5022.3  901.49  5047.5  901.48  5060.6  901.95
  5067.9  902.50  5086.3  905.44  5090.5  906.22  5121.6  912.58  5123.7  912.70
  5141.1  915.38  5143.1  915.60  5156.2  917.61  5168.6  919.18
#Mann=3,-1,0
  4782.0     0.1       0  4989.6    0.05       0  5010.4    0.15       0
Bank Sta=4989.6,5010.4
XS Rating Curve= 0
Exp/Cntr=0.3,0.1

Type RM Length L Ch R = 1,46323,302,302,302
BEGIN DESCRIPTION:
Howards Creek 93.0
END DESCRIPTION:
XS GIS Cut Line= 3
      1290523.54       654655.68      1290442.62       654467.81
      1290211.40       654294.40
#Sta/Elev= 30
  4607.8  920.65  4628.1  918.29  4638.0  917.81  4655.7  914.47  4666.1  913.53
  4673.8  912.26  4683.8  911.16  4689.0  910.35  4709.9  906.42  4736.9  902.74
  4764.3  901.30  4773.1  900.36  4791.0  899.42  4817.9  898.70  4873.3  898.11
  4876.9  898.30  4888.1  897.97  4953.0  899.22  4982.5  898.64  4985.6  895.35
  4989.6  893.04  4991.1  890.04  5008.9  890.04  5010.4  893.04  5026.8  903.04
  5046.5  908.42  5053.8  909.90  5073.7  913.01  5087.1  913.67  5101.3  914.99
#Mann=3,-1,0
  4607.8     0.1       0  4989.6    0.05       0  5010.4    0.15       0
Bank Sta=4989.6,5010.4
XS Rating Curve= 0
Exp/Cntr=0.3,0.1

Type RM Length L Ch R = 1,46021,279,279,279
BEGIN DESCRIPTION:
Howards Creek 92.5
END DESCRIPTION:
XS GIS Cut Line= 3
      1290627.59       653820.40      1290451.29       654022.72
      1290113.13       654262.61
#Sta/Elev= 30
  4608.0  925.88  4653.3  921.71  4683.5  918.20  4779.4  909.54  4808.5  905.62
  4818.4  903.95  4837.8  899.71  4849.1  896.37  4852.5  896.48  4859.5  898.11
  4866.6  898.15  4874.1  897.35  4882.5  895.81  4892.9  895.51  4916.9  896.92
  4931.0  896.56  4972.4  897.48  4989.6  891.55  4991.1  888.55  5008.9  888.55
  5010.4  891.55  5015.6  893.21  5026.9  891.55  5027.4  894.11  5042.1  898.15
  5125.5  898.49  5144.3  899.49  5165.1  902.62  5190.2  908.14  5290.9  925.78
#Mann=3,-1,0
  4608.0    0.15       0  4989.6    0.05       0  5010.4    0.15       0
Bank Sta=4989.6,5010.4
XS Rating Curve= 0
Exp/Cntr=0.3,0.1

Type RM Length L Ch R = 1,45742,333,333,333
BEGIN DESCRIPTION:
Howards Creek 92.0
END DESCRIPTION:
XS GIS Cut Line= 3
      1290519.15       653878.56      1290363.77       653863.77
      1290048.58       653838.61
#Sta/Elev= 30
  4732.8  914.91  4748.4  913.94  4795.2  909.19  4823.6  903.59  4833.5  901.31
  4861.4  896.72  4869.2  895.93  4878.0  895.32  4899.6  894.57  4936.0  896.30
  4955.2  896.90  4967.5  895.81  4971.2  895.28  4974.4  894.50  4989.6  889.66
  4991.1  886.66  5008.9  886.66  5010.4  889.66  5011.0  895.08  5024.9  896.36
  5030.0  896.40  5037.9  896.80  5059.1  897.26  5092.2  899.67  5115.8  902.81
  5119.3  903.64  5126.7  904.96  5136.9  907.29  5203.7  918.05  5205.1  918.21
#Mann=3,-1,0
  4732.8    0.15       0  4989.6    0.05       0  5010.4    0.15       0
Bank Sta=4989.6,5010.4
XS Rating Curve= 0
Exp/Cntr=0.3,0.1

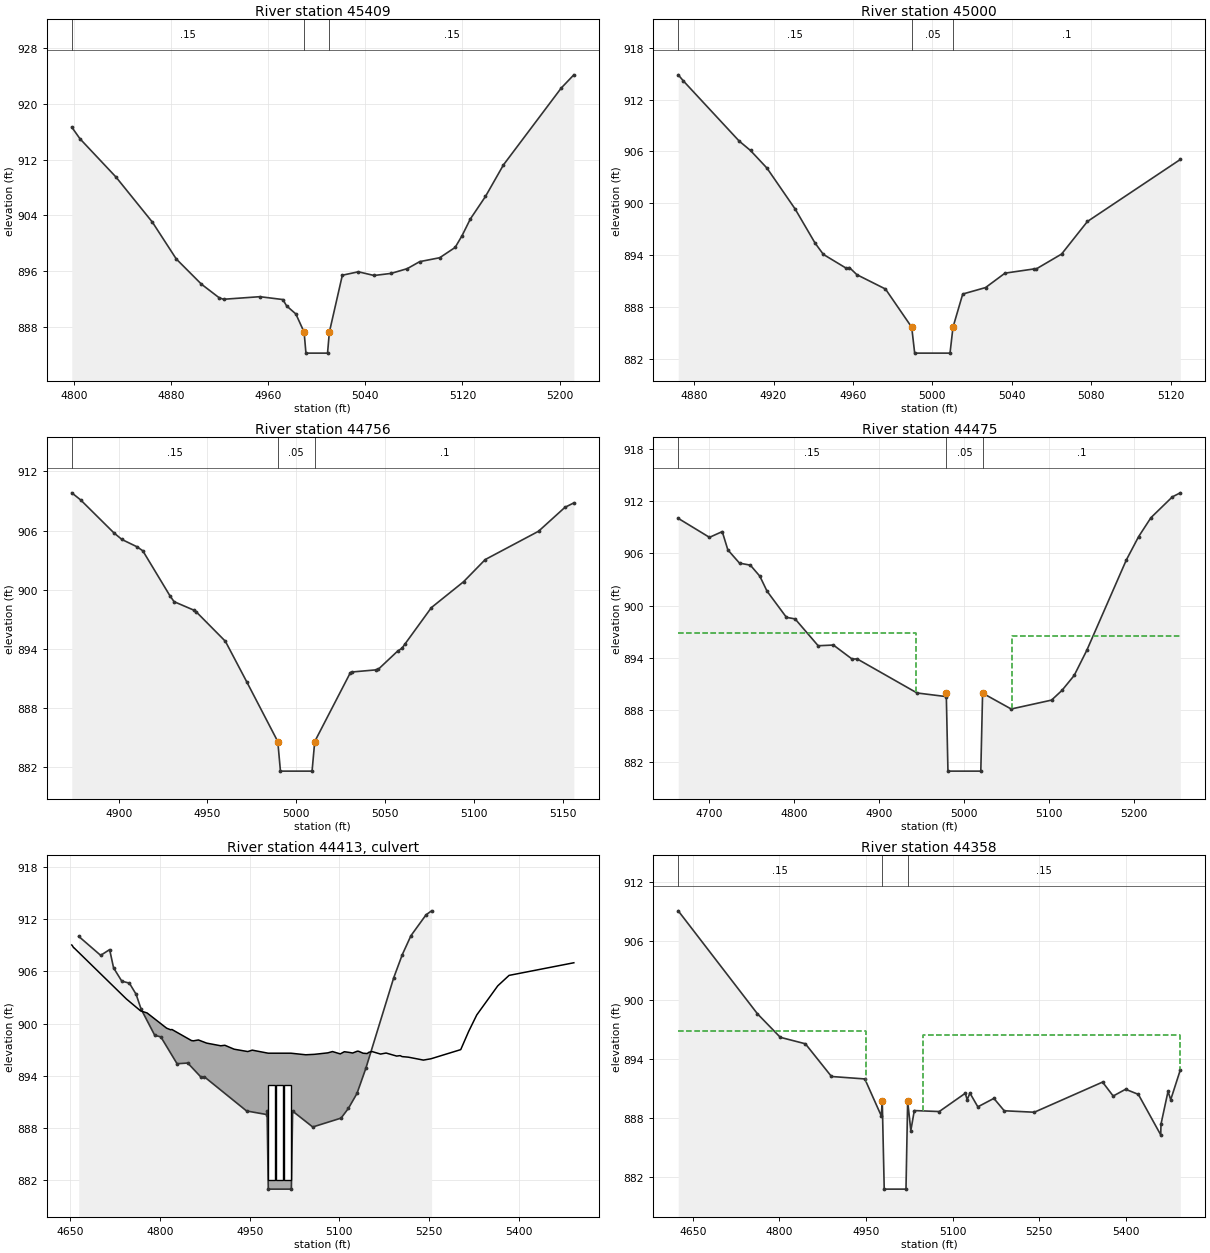
Type RM Length L Ch R = 1,45409,409,409,409
BEGIN DESCRIPTION:
Howards Creek 91.0
END DESCRIPTION:
XS GIS Cut Line= 3
      1290240.95       653405.77      1290183.24       653521.19
      1289937.59       653664.73
#Sta/Elev= 30
  4798.2  916.63  4805.0  914.96  4834.6  909.50  4864.6  903.05  4884.3  897.78
  4905.0  894.18  4919.6  892.24  4923.2  892.02  4953.2  892.39  4972.1  891.98
  4975.2  891.07  4982.8  889.92  4989.6  887.32  4991.1  884.32  5008.9  884.32
  5010.4  887.32  5021.1  895.46  5034.3  895.95  5047.2  895.42  5061.3  895.72
  5074.6  896.40  5084.8  897.40  5101.3  897.96  5114.0  899.43  5119.7  901.11
  5126.5  903.49  5139.0  906.72  5153.8  911.23  5201.5  922.24  5211.8  924.11
#Mann=3,-1,0
  4798.2    0.15       0  4989.6    0.05       0  5010.4    0.15       0
Bank Sta=4989.6,5010.4
XS Rating Curve= 0
Exp/Cntr=0.3,0.1

Type RM Length L Ch R = 1,45000,244,244,244
BEGIN DESCRIPTION:
Howards Creek 90.0
END DESCRIPTION:
XS GIS Cut Line= 3
      1290025.00       653125.00      1289935.11       653216.08
      1289825.00       653275.00
#Sta/Elev= 24
  4872.0  914.86  4874.6  914.15  4902.7  907.19  4908.4  906.10  4916.7  904.06
  4930.9  899.32  4940.9  895.39  4945.1  894.07  4956.7  892.46  4958.2  892.55
  4962.0  891.72  4976.4  890.06  4989.6  885.64  4991.1  882.64  5008.9  882.64
  5010.4  885.64  5015.3  889.48  5026.8  890.23  5036.6  891.90  5051.3  892.39
  5052.2  892.37  5065.1  894.11  5078.1  897.88  5124.9  905.06
#Mann=3,-1,0
  4872.0    0.15       0  4989.6    0.05       0  5010.4     0.1       0
Bank Sta=4989.6,5010.4
XS Rating Curve= 0
Exp/Cntr=0.3,0.1

Type RM Length L Ch R = 1,44756,281,281,281
BEGIN DESCRIPTION:
Howards Creek 89.0
END DESCRIPTION:
XS GIS Cut Line= 3
      1289868.04       652998.82      1289799.97       653010.66
      1289644.59       653157.16
#Sta/Elev= 29
  4873.6  909.83  4878.6  909.11  4897.2  905.79  4901.8  905.10  4910.3  904.36
  4913.6  903.95  4928.9  899.38  4931.2  898.79  4942.7  897.90  4943.5  897.79
  4960.1  894.77  4972.2  890.63  4989.6  884.60  4991.1  881.60  5008.9  881.60
  5010.4  884.60  5030.5  891.60  5031.6  891.66  5044.8  891.87  5046.3  891.95
  5057.1  893.78  5059.5  894.06  5061.2  894.49  5076.1  898.19  5094.2  900.81
  5106.4  903.06  5136.4  905.93  5151.3  908.36  5156.3  908.81
#Mann=3,-1,0
  4873.6    0.15       0  4989.6    0.05       0  5010.4     0.1       0
Bank Sta=4989.6,5010.4
XS Rating Curve= 0
Exp/Cntr=0.5,0.3

Type RM Length L Ch R = 1,44475,117,117,117
BEGIN DESCRIPTION:
Bill Sain Rd u/s HC
END DESCRIPTION:
XS GIS Cut Line= 5
      1289869.52       652979.59      1289626.83       652895.24
      1289542.48       652874.52      1289447.78       652870.08
      1289317.55       652947.03
#Sta/Elev= 30
  4664.2  910.01  4700.9  907.83  4715.9  908.49  4722.5  906.39  4736.2  904.87
  4748.9  904.64  4760.1  903.37  4768.5  901.66  4791.3  898.65  4801.5  898.47
  4828.6  895.39  4846.5  895.47  4868.5  893.86  4874.4  893.88  4944.8  889.97
  4978.5  889.56  4979.1  889.95  4981.1  881.00  5019.7  881.00  5021.8  889.95
  5055.4  888.13  5102.8  889.15  5115.0  890.26  5129.4  891.98  5144.2  894.86
  5190.7  905.24  5205.1  907.91  5219.6  910.09  5244.8  912.48  5254.1  912.94
#Mann=3,-1,0
  4664.2    0.15       0  4979.1    0.05       0  5021.8     0.1       0
#XS Ineff=2,0
    0.00 4943.50  896.83 5056.50    0.00  896.46
Bank Sta=4979.1,5021.8
XS Rating Curve= 0
Exp/Cntr=0.5,0.3

Type RM Length L Ch R =2,44413,,,
BEGIN DESCRIPTION:
Bill Sain Rd TOR HC
Structure ID: LDS_HC_08
Approximate Survey Structure
END DESCRIPTION:
Bridge Culvert--1,0,-1,-1,0
Deck Dist Width WeirC Skew NumUp NumDn MinLoCord MaxHiCord MaxSubmerge Is_Ogee
37.5,49,3,,51,51,,,,0,1,1,,,
  4652.6  4653.8  4655.7  4656.4  4743.8  4767.6  4778.5  4811.2  4817.8  4820.1
  4852.7  4856.0  4864.3  4878.0  4901.0  4901.4  4908.5  4924.0  4946.8  4954.3
  4981.0  5019.0  5043.7  5058.2  5080.6  5088.5  5101.4  5108.2  5116.7  5122.1
  5129.9  5132.2  5139.5  5146.4  5149.4  5154.5  5168.8  5178.0  5195.7  5201.5
  5204.8  5214.5  5215.6  5240.4  5253.0  5302.8  5316.2  5329.6  5364.7  5383.6
  5491.9
  909.02  908.92  908.70  908.69  902.83  901.46  901.22  899.47  899.29  899.32
  898.05  898.02  898.12  897.76  897.46  897.45  897.51  897.06  896.79  896.95
  896.60  896.60  896.42  896.47  896.64  896.79  896.52  896.77  896.69  896.62
  896.83  896.82  896.60  896.56  896.71  896.79  896.50  896.62  896.27  896.32
  896.21  896.15  896.14  895.81  895.96  897.01  899.12  900.99  904.33  905.53
  906.98
  861.00  861.00  861.00  861.00  861.00  861.00  861.00  861.00  861.00  861.00
  861.00  861.00  861.00  861.00  861.00  861.00  861.00  861.00  861.00  861.00
  861.00  861.00  861.00  861.00  861.00  861.00  861.00  861.00  861.00  861.00
  861.00  861.00  861.00  861.00  861.00  861.00  861.00  861.00  861.00  861.00
  861.00  861.00  861.00  861.00  861.00  861.00  861.00  861.00  861.00  861.00
  861.00
  4652.6  4653.8  4655.7  4656.4  4743.8  4767.6  4778.5  4811.2  4817.8  4820.1
  4852.7  4856.0  4864.3  4878.0  4901.0  4901.4  4908.5  4924.0  4946.8  4954.3
  4981.0  5019.0  5043.7  5058.2  5080.6  5088.5  5101.4  5108.2  5116.7  5122.1
  5129.9  5132.2  5139.5  5146.4  5149.4  5154.5  5168.8  5178.0  5195.7  5201.5
  5204.8  5214.5  5215.6  5240.4  5253.0  5302.8  5316.2  5329.6  5364.7  5383.6
  5491.9
  909.02  908.92  908.70  908.69  902.83  901.46  901.22  899.47  899.29  899.32
  898.05  898.02  898.12  897.76  897.46  897.45  897.51  897.06  896.79  896.95
  896.60  896.60  896.42  896.47  896.64  896.79  896.52  896.77  896.69  896.62
  896.83  896.82  896.60  896.56  896.71  896.79  896.50  896.62  896.27  896.32
  896.21  896.15  896.14  895.81  895.96  897.01  899.12  900.99  904.33  905.53
  906.98
  860.76  860.76  860.76  860.76  860.76  860.76  860.76  860.76  860.76  860.76
  860.76  860.76  860.76  860.76  860.76  860.76  860.76  860.76  860.76  860.76
  860.76  860.76  860.76  860.76  860.76  860.76  860.76  860.76  860.76  860.76
  860.76  860.76  860.76  860.76  860.76  860.76  860.76  860.76  860.76  860.76
  860.76  860.76  860.76  860.76  860.76  860.76  860.76  860.76  860.76  860.76
  860.76
Culvert=2,11,12,49,0.012,0.4,1,8,1,882,4987,881.76,4987,Culvert #1,0,37.5
Culvert Bottom n=0.012
Culvert Bottom Depth=0
Culvert Depth Blocked=0
Culvert=2,11,12,49,0.012,0.4,1,8,1,882,5000,881.76,5000,Culvert #2,0,37.5
Culvert Bottom n=0.012
Culvert Bottom Depth=0
Culvert Depth Blocked=0
Culvert=2,11,12,49,0.012,0.4,1,8,1,882,5013,881.76,5013,Culvert #3,0,37.5
Culvert Bottom n=0.012
Culvert Bottom Depth=0
Culvert Depth Blocked=0
BC Design=,,0,,0,,,,,,

Type RM Length L Ch R = 1,44358,415,415,415
BEGIN DESCRIPTION:
Bill Sain Road d/s HC
END DESCRIPTION:
XS GIS Cut Line= 6
      1289889.64       652938.15      1289558.17       652765.02
      1289494.54       652730.98      1289364.32       652701.38
      1289260.73       652695.47      1288934.29       652559.32
#Sta/Elev= 30
  4624.7  909.10  4762.0  898.61  4801.5  896.22  4845.0  895.56  4890.2  892.23
  4948.0  891.98  4976.5  888.22  4978.2  889.71  4981.6  880.76  5019.3  880.76
  5022.2  889.71  5027.7  886.72  5033.7  888.76  5076.9  888.66  5122.0  890.52
  5125.3  889.87  5130.1  890.54  5143.8  889.14  5171.6  890.00  5189.5  888.74
  5241.6  888.59  5359.9  891.66  5378.3  890.24  5399.8  890.93  5421.9  890.41
  5460.7  886.28  5461.1  887.37  5473.3  890.71  5478.0  889.87  5494.6  892.90
#Mann=3,-1,0
  4624.7    0.15       0  4978.2    0.05       0  5022.2    0.15       0
#XS Ineff=2,0
    0.00 4950.50  896.87 5049.50    0.00  896.44
Bank Sta=4978.2,5022.2
XS Rating Curve= 0
Exp/Cntr=0.5,0.3

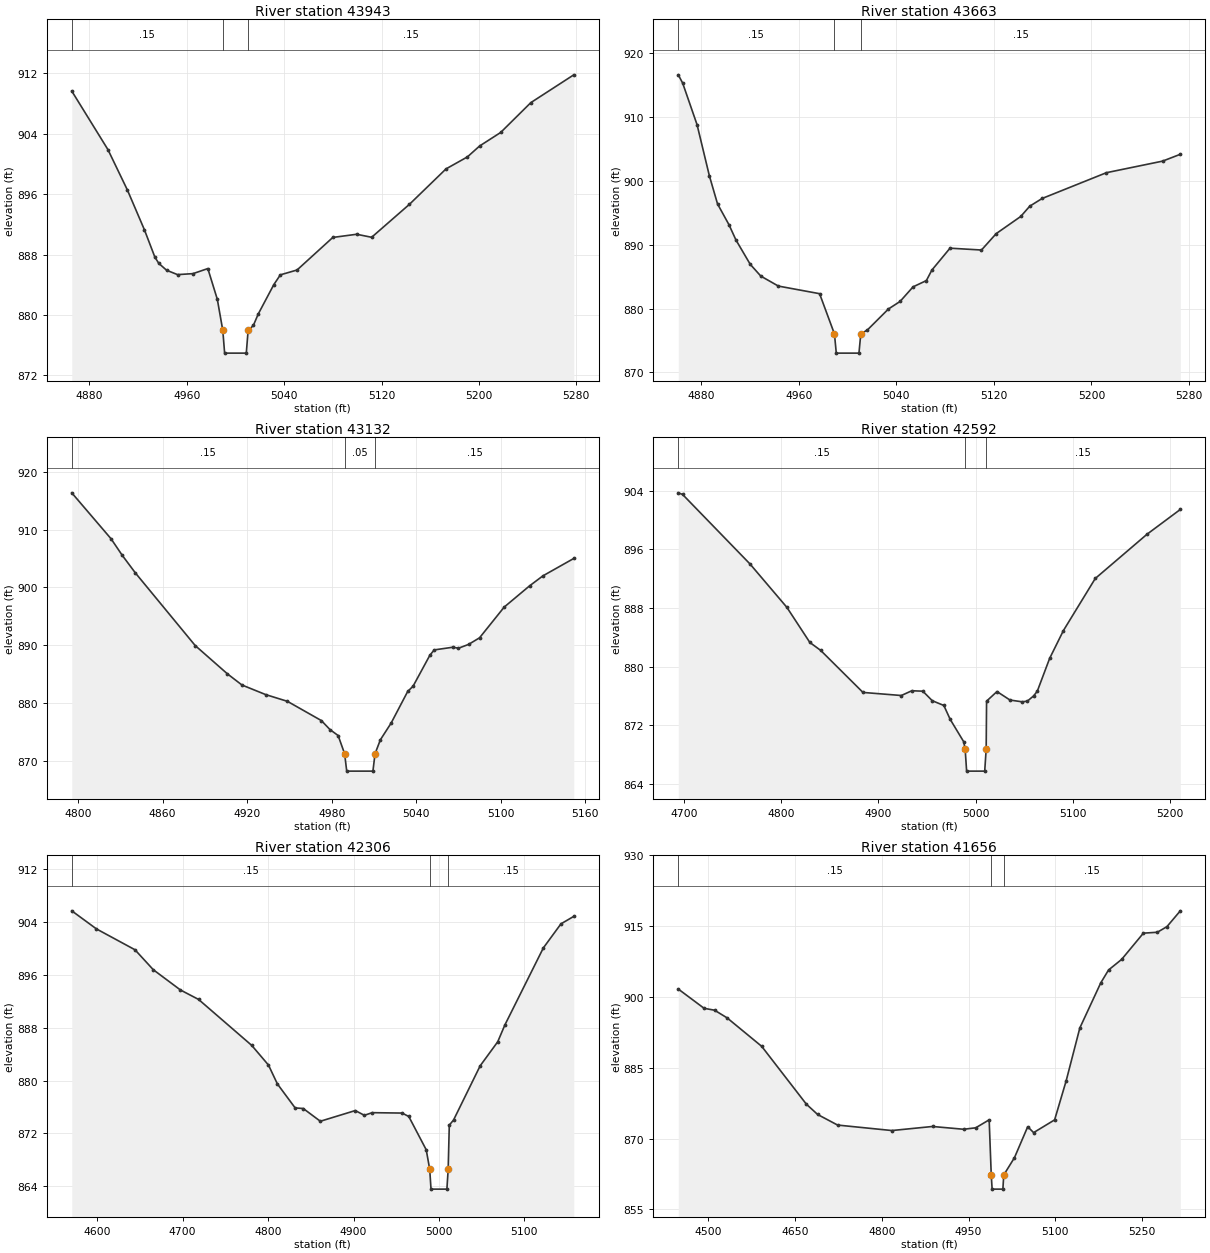
Type RM Length L Ch R = 1,43943,280,280,280
BEGIN DESCRIPTION:
Howards Creek 88.0
END DESCRIPTION:
XS GIS Cut Line= 3
      1289912.79       652924.12      1289909.30       652725.47
      1289839.60       652523.34
#Sta/Elev= 30
  4865.5  909.64  4895.2  901.90  4911.2  896.55  4925.2  891.28  4933.8  887.66
  4937.0  886.84  4943.4  885.93  4952.4  885.35  4965.1  885.48  4977.3  886.15
  4985.1  882.08  4989.6  877.96  4991.1  874.96  5008.9  874.96  5010.4  877.96
  5014.7  878.62  5018.7  880.13  5031.5  884.02  5036.9  885.32  5050.6  885.96
  5080.0  890.27  5099.6  890.69  5111.9  890.29  5143.0  894.66  5173.0  899.34
  5190.6  900.93  5200.6  902.37  5217.9  904.16  5242.7  908.11  5278.0  911.79
#Mann=3,-1,0
  4865.5    0.15       0  4989.6    0.05       0  5010.4    0.15       0
Bank Sta=4989.6,5010.4
XS Rating Curve= 0
Exp/Cntr=0.3,0.1

Type RM Length L Ch R = 1,43663,531,531,531
BEGIN DESCRIPTION:
Howards Creek 87.0
END DESCRIPTION:
XS GIS Cut Line= 3
      1290233.41       652878.82      1290181.14       652749.87
      1290010.37       652537.28
#Sta/Elev= 30
  4861.1  916.56  4864.7  915.26  4876.5  908.76  4886.6  900.76  4893.3  896.36
  4902.7  893.10  4908.4  890.72  4920.1  886.92  4928.8  885.07  4943.2  883.51
  4977.0  882.32  4989.2  876.02  4990.7  873.02  5009.3  873.02  5010.8  876.02
  5016.3  876.66  5033.5  879.93  5043.0  881.10  5053.7  883.39  5064.6  884.37
  5069.1  886.01  5084.0  889.44  5109.8  889.15  5121.9  891.72  5142.0  894.40
  5149.4  896.01  5159.6  897.22  5212.3  901.25  5258.4  903.06  5272.9  904.13
#Mann=3,-1,0
  4861.1    0.15       0  4989.2    0.05       0  5010.8    0.15       0
Bank Sta=4989.2,5010.8
XS Rating Curve= 0
Exp/Cntr=0.3,0.1

Type RM Length L Ch R = 1,43132,540,540,540
BEGIN DESCRIPTION:
Howards Creek 86.0
END DESCRIPTION:
XS GIS Cut Line= 3
      1290390.24       652310.75      1290264.78       652296.81
      1290034.77       652303.78
#Sta/Elev= 30
  4795.5  916.33  4823.4  908.40  4831.3  905.56  4840.6  902.53  4883.1  889.99
  4906.0  885.10  4916.3  883.18  4933.2  881.52  4948.6  880.36  4972.7  877.04
  4978.8  875.49  4984.6  874.46  4989.2  871.32  4990.7  868.32  5009.3  868.32
  5010.8  871.32  5014.6  873.73  5022.2  876.60  5034.0  882.07  5037.8  882.97
  5049.7  888.30  5052.8  889.23  5066.2  889.70  5070.0  889.52  5077.2  890.18
  5085.0  891.32  5102.5  896.62  5120.5  900.28  5130.0  902.01  5151.9  905.01
#Mann=3,-1,0
  4795.5    0.15       0  4989.2    0.05       0  5010.8    0.15       0
Bank Sta=4989.2,5010.8
XS Rating Curve= 0
Exp/Cntr=0.3,0.1

Type RM Length L Ch R = 1,42592,286,286,286
BEGIN DESCRIPTION:
Howards Creek 85.0
END DESCRIPTION:
XS GIS Cut Line= 3
      1290469.01       651838.87      1290259.90       651755.23
      1289977.61       651824.93
#Sta/Elev= 30
  4694.4  903.71  4698.8  903.49  4768.1  894.00  4806.0  888.08  4829.6  883.29
  4840.7  882.21  4884.2  876.47  4923.6  876.05  4934.4  876.70  4945.7  876.64
  4955.4  875.34  4967.3  874.69  4973.8  872.80  4987.7  869.74  4989.2  868.73
  4990.7  865.73  5009.3  865.73  5010.8  868.73  5011.2  875.28  5021.9  876.59
  5035.3  875.43  5047.8  875.19  5053.1  875.28  5059.5  875.99  5063.3  876.63
  5076.0  881.11  5090.2  884.92  5122.9  892.02  5176.1  898.06  5210.3  901.44
#Mann=3,-1,0
  4694.4    0.15       0  4989.2    0.05       0  5010.8    0.15       0
Bank Sta=4989.2,5010.8
XS Rating Curve= 0
Exp/Cntr=0.3,0.1

Type RM Length L Ch R = 1,42306,650,650,650
BEGIN DESCRIPTION:
Howards Creek 84.0
END DESCRIPTION:
XS GIS Cut Line= 3
      1290517.80       651838.52      1290340.06       651629.42
      1290113.53       651413.34
#Sta/Elev= 30
  4570.3  905.71  4599.2  902.97  4644.3  899.81  4665.7  896.79  4697.5  893.72
  4718.7  892.29  4780.9  885.33  4800.5  882.35  4810.9  879.50  4831.7  875.86
  4841.2  875.77  4861.2  873.84  4902.1  875.46  4912.7  874.74  4921.9  875.14
  4956.9  875.08  4964.7  874.56  4985.1  869.52  4989.2  866.56  4990.7  863.56
  5009.3  863.56  5010.8  866.56  5012.1  873.25  5017.1  874.03  5048.2  882.23
  5068.8  885.88  5077.1  888.41  5122.2  900.10  5142.8  903.74  5157.8  904.87
#Mann=3,-1,0
  4570.3    0.15       0  4989.2    0.05       0  5010.8    0.15       0
Bank Sta=4989.2,5010.8
XS Rating Curve= 0
Exp/Cntr=0.3,0.1

Type RM Length L Ch R = 1,41656,291,291,291
BEGIN DESCRIPTION:
Howards Creek 83.0
END DESCRIPTION:
XS GIS Cut Line= 3
      1290894.19       651831.55      1290852.36       651340.15
      1290671.14       651012.56
#Sta/Elev= 30
  4448.4  901.67  4493.0  897.59  4511.1  897.19  4532.7  895.57  4592.5  889.54
  4669.7  877.29  4689.2  875.10  4723.7  872.86  4817.5  871.70  4887.7  872.56
  4941.5  871.97  4962.4  872.28  4985.6  873.97  4989.2  862.29  4990.7  859.29
  5009.3  859.29  5010.8  862.29  5029.3  865.95  5052.2  872.51  5062.4  871.26
  5098.7  873.96  5118.6  882.21  5142.3  893.44  5178.4  902.97  5191.9  905.71
  5214.5  907.95  5252.1  913.51  5276.2  913.70  5292.8  914.89  5315.9  918.24
#Mann=3,-1,0
  4448.4    0.15       0  4989.2    0.05       0  5010.8    0.15       0
Bank Sta=4989.2,5010.8
XS Rating Curve= 0
Exp/Cntr=0.3,0.1

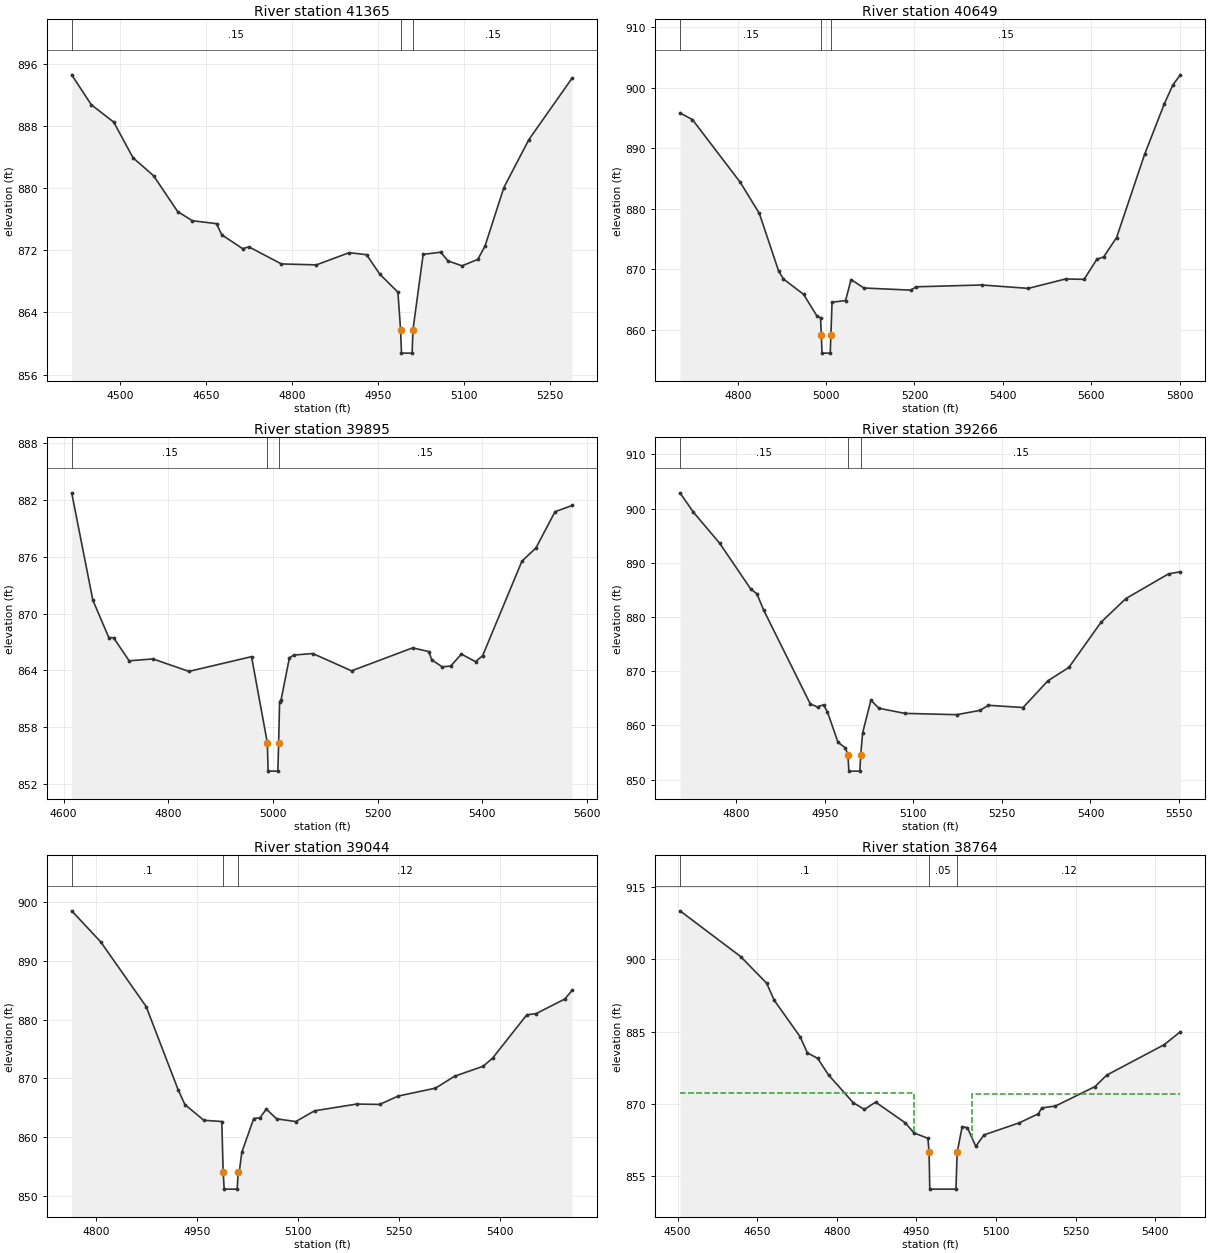
Type RM Length L Ch R = 1,41365,716,716,716
BEGIN DESCRIPTION:
Howards Creek 82.0
END DESCRIPTION:
XS GIS Cut Line= 3
      1291204.36       651803.67      1291068.44       651120.59
      1290974.34       650970.74
#Sta/Elev= 30
  4415.1  894.55  4449.4  890.70  4488.5  888.47  4522.2  883.88  4558.2  881.56
  4600.0  876.97  4625.6  875.79  4667.9  875.41  4677.0  873.98  4713.6  872.19
  4724.4  872.43  4781.1  870.23  4842.2  870.11  4899.5  871.68  4929.8  871.42
  4953.2  868.89  4984.5  866.60  4989.2  861.76  4990.7  858.76  5009.3  858.76
  5010.8  861.76  5028.6  871.46  5059.3  871.74  5071.9  870.62  5096.4  869.99
  5123.9  870.81  5136.5  872.52  5169.5  880.06  5213.1  886.22  5288.5  894.12
#Mann=3,-1,0
  4415.1    0.15       0  4989.2    0.05       0  5010.8    0.15       0
Bank Sta=4989.2,5010.8
XS Rating Curve= 0
Exp/Cntr=0.3,0.1

Type RM Length L Ch R = 1,40649,754,754,754
BEGIN DESCRIPTION:
Howards Creek 81.0
END DESCRIPTION:
XS GIS Cut Line= 3
      1291922.28       651316.46      1291727.12       651193.78
      1291089.35       650556.01
#Sta/Elev= 30
  4669.3  895.81  4697.5  894.71  4805.9  884.35  4848.9  879.23  4892.8  869.67
  4903.4  868.43  4949.0  865.89  4979.5  862.29  4987.3  862.05  4989.2  859.20
  4990.7  856.20  5009.3  856.20  5010.8  859.20  5013.4  864.60  5044.0  864.87
  5056.5  868.33  5085.6  866.94  5191.6  866.59  5204.1  867.14  5352.3  867.44
  5457.5  866.88  5542.0  868.43  5583.9  868.37  5612.7  871.67  5628.3  872.08
  5657.4  875.27  5720.7  888.96  5765.2  897.28  5784.7  900.43  5801.8  902.10
#Mann=3,-1,0
  4669.3    0.15       0  4989.2    0.05       0  5010.8    0.15       0
Bank Sta=4989.2,5010.8
XS Rating Curve= 0
Exp/Cntr=0.3,0.1

Type RM Length L Ch R = 1,39895,629,629,629
BEGIN DESCRIPTION:
Howards Creek 80.0
END DESCRIPTION:
XS GIS Cut Line= 3
      1292225.00       650325.00      1291783.58       650524.30
      1291312.39       650501.99
#Sta/Elev= 30
  4615.4  882.78  4655.8  871.43  4686.3  867.47  4695.4  867.45  4725.2  865.01
  4770.7  865.21  4839.3  863.89  4959.0  865.45  4989.2  856.34  4990.7  853.34
  5009.3  853.34  5010.8  856.34  5012.6  860.67  5015.4  860.87  5031.4  865.33
  5039.6  865.62  5076.0  865.78  5150.1  863.95  5266.8  866.38  5297.6  865.99
  5303.4  865.10  5323.5  864.37  5339.6  864.46  5359.9  865.72  5386.9  864.92
  5400.5  865.55  5475.6  875.55  5502.4  876.95  5538.8  880.78  5571.4  881.44
#Mann=3,-1,0
  4615.4    0.15       0  4989.2    0.05       0  5010.8    0.15       0
Bank Sta=4989.2,5010.8
XS Rating Curve= 0
Exp/Cntr=0.3,0.1

Type RM Length L Ch R = 1,39266,222,222,222
BEGIN DESCRIPTION:
Howards Creek 79.0
END DESCRIPTION:
XS GIS Cut Line= 3
      1292059.60       649828.96      1291716.66       649929.33
      1291301.24       650189.73
#Sta/Elev= 30
  4704.7  902.92  4727.2  899.37  4771.7  893.64  4824.9  885.11  4834.9  884.31
  4846.3  881.30  4925.4  863.94  4937.6  863.40  4947.8  863.79  4954.5  862.47
  4972.3  856.87  4984.7  855.85  4989.2  854.55  4990.7  851.55  5009.3  851.55
  5010.8  854.55  5014.0  858.60  5028.1  864.65  5041.5  863.16  5085.6  862.21
  5173.2  861.97  5212.7  862.76  5227.2  863.70  5285.8  863.29  5327.9  868.23
  5363.4  870.69  5417.8  879.02  5459.8  883.39  5532.2  887.96  5552.3  888.35
#Mann=3,-1,0
  4704.7    0.15       0  4989.2    0.05       0  5010.8    0.15       0
Bank Sta=4989.2,5010.8
XS Rating Curve= 0
Exp/Cntr=0.3,0.1

Type RM Length L Ch R = 1,39044,280,280,280
BEGIN DESCRIPTION:
Howards Creek 78.0
END DESCRIPTION:
XS GIS Cut Line= 3
      1292051.23       649763.71      1291738.97       649680.07
      1291398.82       649431.94
#Sta/Elev= 30
  4763.5  898.55  4806.7  893.26  4874.3  882.24  4922.2  867.96  4931.9  865.55
  4960.1  862.87  4986.8  862.66  4988.8  854.14  4990.3  851.14  5009.7  851.14
  5011.2  854.14  5012.9  854.14  5016.5  857.39  5034.3  863.17  5043.6  863.31
  5053.0  864.77  5068.3  863.12  5096.8  862.65  5124.9  864.49  5187.5  865.63
  5221.6  865.57  5249.3  867.00  5304.6  868.34  5333.0  870.37  5375.5  872.07
  5389.6  873.46  5440.5  880.84  5454.4  881.04  5496.9  883.52  5507.8  884.99
#Mann=3,-1,0
  4763.5     0.1       0  4988.8    0.05       0  5011.2    0.12       0
Bank Sta=4988.8,5011.2
XS Rating Curve= 0
Exp/Cntr=0.5,0.3

Type RM Length L Ch R = 1,38764,105,105,105
BEGIN DESCRIPTION:
SR 1197 u/s HC
END DESCRIPTION:
XS GIS Cut Line= 6
      1292257.55       649788.81      1292129.30       649607.58
      1292062.38       649549.03      1291950.86       649468.18
      1291858.85       649404.05      1291527.08       649214.47
#Sta/Elev= 30
  4504.4  910.04  4618.6  900.56  4667.7  895.02  4681.9  891.49  4730.8  883.92
  4744.3  880.59  4763.9  879.42  4784.3  875.99  4830.7  870.25  4851.8  868.84
  4873.0  870.35  4929.1  866.04  4945.2  863.97  4971.6  862.84  4973.8  859.90
  4975.1  852.30  5024.4  852.30  5026.7  859.90  5036.1  865.26  5046.0  865.05
  5061.8  861.18  5077.3  863.55  5143.9  866.06  5179.8  867.94  5186.1  869.15
  5211.9  869.54  5286.6  873.58  5308.5  875.95  5416.8  882.26  5447.4  884.96
#Mann=3,-1,0
  4504.4     0.1       0  4973.8    0.05       0  5026.7    0.12       0
#XS Ineff=2,0
    0.00 4944.50  872.27 5055.50    0.00  872.10
Bank Sta=4973.8,5026.7
XS Rating Curve= 0
Exp/Cntr=0.5,0.3