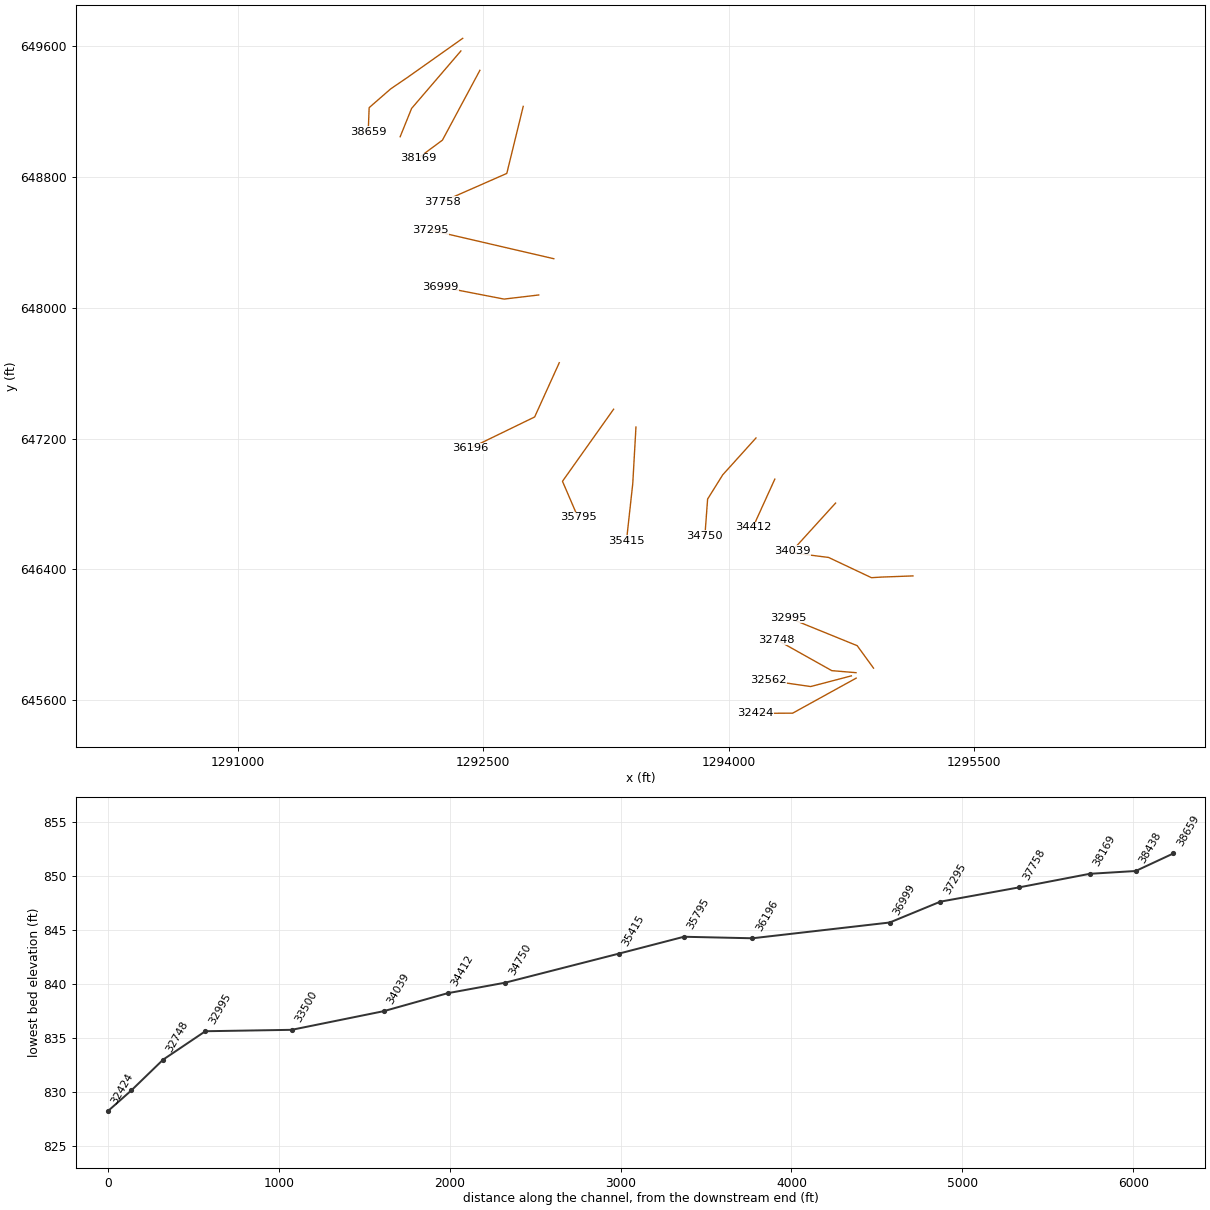
HEC-RAS study Howards Creek.prj: Howards Creek Limited Detail Study

--- Howards Creek.g01 (geometry) --- (continued)

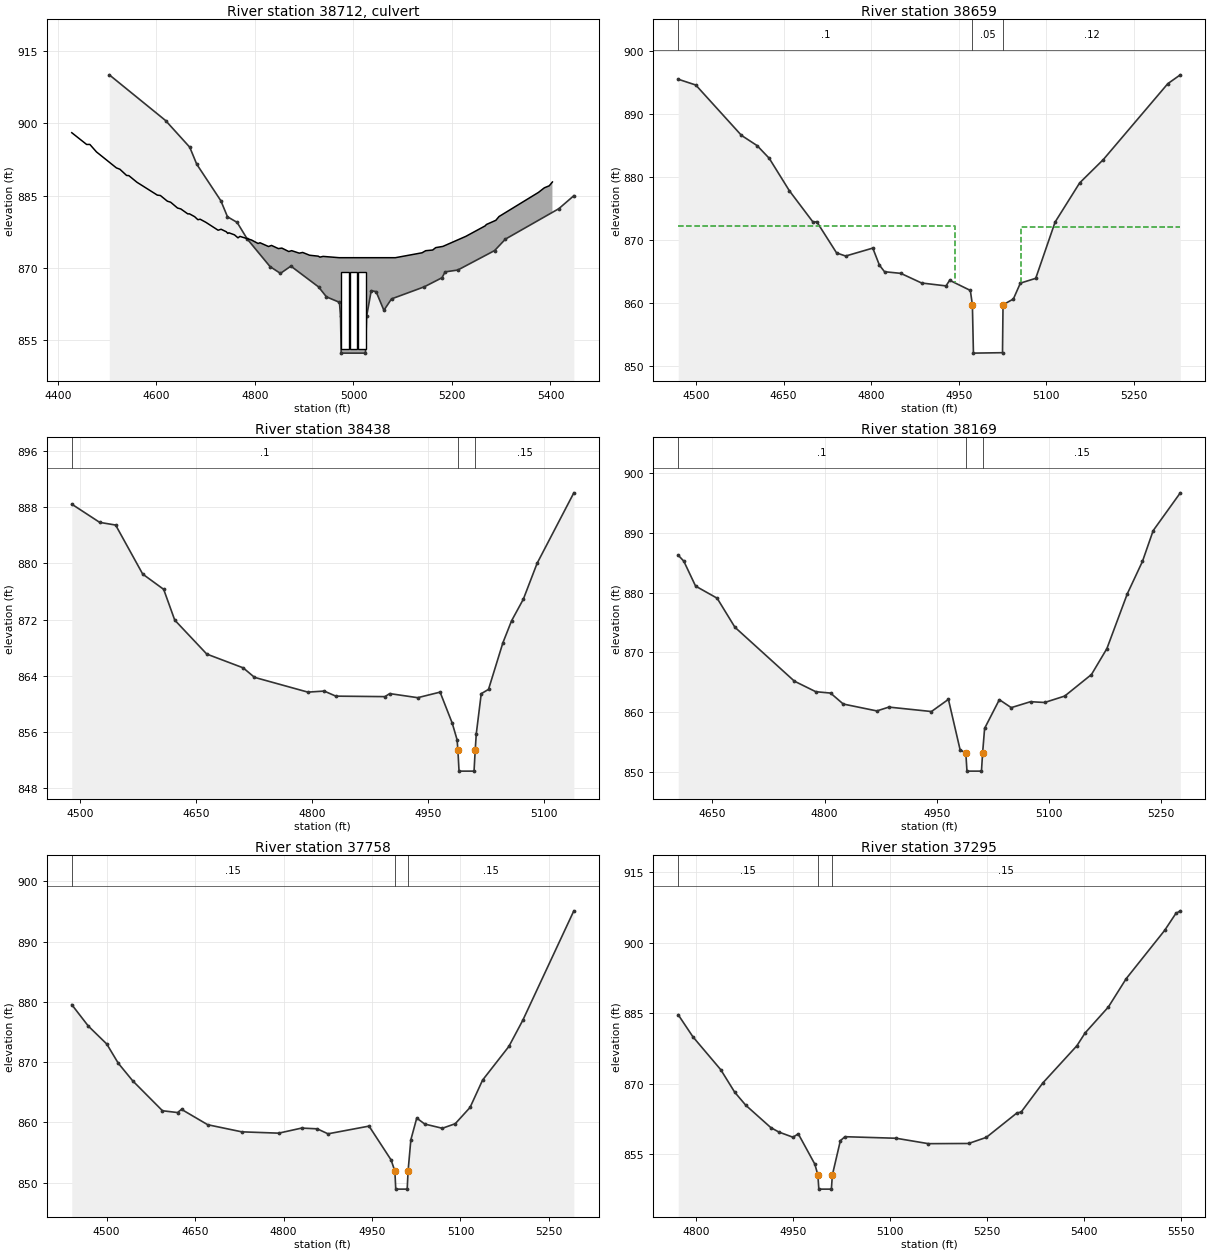
Type RM Length L Ch R =2,38712,,,
BEGIN DESCRIPTION:
SR 1197 TOR HC
Structure ID: LDS_HC_07
Approximate Survey Structure
END DESCRIPTION:
Bridge Culvert--1,0,-1,-1,0
Deck Dist Width WeirC Skew NumUp NumDn MinLoCord MaxHiCord MaxSubmerge Is_Ogee
30.5,43,3,, 60, 60,,,,0,1,1,,,
  4428.2  4458.4  4464.9  4478.4  4518.8  4525.9  4539.5  4544.0  4560.5  4601.9
  4608.1  4622.3  4628.9  4642.9  4649.5  4663.7  4667.1  4677.6  4684.2  4688.8
  4700.4  4725.3  4731.3  4742.0  4745.0  4747.0  4758.5  4765.6  4769.6  4793.1
  4806.4  4810.3  4827.6  4833.6  4847.6  4854.7  4868.7  4874.6  4890.0  4896.9
  4911.0  4928.4  4931.9  4938.4  4971.1  5085.1  5139.3  5146.6  5160.8  5167.0
  5181.5  5228.2  5267.3  5269.9  5289.1  5295.5  5375.6  5387.5  5397.5  5403.9
  898.03  895.59  895.60  894.04  890.73  890.45  889.16  889.13  887.75  885.08
  885.00  883.82  883.61  882.40  882.22  881.19  881.20  880.61  879.98  880.08
  879.44  877.80  878.00  877.47  877.13  877.27  876.84  876.22  876.52  875.77
  875.05  875.20  874.42  874.65  873.99  874.09  873.38  873.56  873.04  873.19
  872.61  872.42  872.22  872.37  872.10  872.10  873.12  873.55  873.69  874.19
  874.44  876.53  878.70  878.99  879.86  880.64  885.65  886.60  887.02  887.81
  832.30  832.30  832.30  832.30  832.30  832.30  832.30  832.30  832.30  832.30
  832.30  832.30  832.30  832.30  832.30  832.30  832.30  832.30  832.30  832.30
  832.30  832.30  832.30  832.30  832.30  832.30  832.30  832.30  832.30  832.30
  832.30  832.30  832.30  832.30  832.30  832.30  832.30  832.30  832.30  832.30
  832.30  832.30  832.30  832.30  832.30  832.30  832.30  832.30  832.30  832.30
  832.30  832.30  832.30  832.30  832.30  832.30  832.30  832.30  832.30  832.30
  4428.2  4458.4  4464.9  4478.4  4518.8  4525.9  4539.5  4544.0  4560.5  4601.9
  4608.1  4622.3  4628.9  4642.9  4649.5  4663.7  4667.1  4677.6  4684.2  4688.8
  4700.4  4725.3  4731.3  4742.0  4745.0  4747.0  4758.5  4765.6  4769.6  4793.1
  4806.4  4810.3  4827.6  4833.6  4847.6  4854.7  4868.7  4874.6  4890.0  4896.9
  4911.0  4928.4  4931.9  4938.4  4971.1  5085.1  5139.3  5146.6  5160.8  5167.0
  5181.5  5228.2  5267.3  5269.9  5289.1  5295.5  5375.6  5387.5  5397.5  5403.9
  898.03  895.59  895.60  894.04  890.73  890.45  889.16  889.13  887.75  885.08
  885.00  883.82  883.61  882.40  882.22  881.19  881.20  880.61  879.98  880.08
  879.44  877.80  878.00  877.47  877.13  877.27  876.84  876.22  876.52  875.77
  875.05  875.20  874.42  874.65  873.99  874.09  873.38  873.56  873.04  873.19
  872.61  872.42  872.22  872.37  872.10  872.10  873.12  873.55  873.69  874.19
  874.44  876.53  878.70  878.99  879.86  880.64  885.65  886.60  887.02  887.81
  832.08  832.08  832.08  832.08  832.08  832.08  832.08  832.08  832.08  832.08
  832.08  832.08  832.08  832.08  832.08  832.08  832.08  832.08  832.08  832.08
  832.08  832.08  832.08  832.08  832.08  832.08  832.08  832.08  832.08  832.08
  832.08  832.08  832.08  832.08  832.08  832.08  832.08  832.08  832.08  832.08
  832.08  832.08  832.08  832.08  832.08  832.08  832.08  832.08  832.08  832.08
  832.08  832.08  832.08  832.08  832.08  832.08  832.08  832.08  832.08  832.08
Culvert=2,16,16,43,0.012,0.4,1,8,2,853.1,4983,852.89,4983,Culvert #1,0,30.5
Culvert Bottom n=0.012
Culvert Bottom Depth=0
Culvert Depth Blocked=0
Culvert=2,16,16,43,0.012,0.4,1,8,2,853.1,5000,852.89,5000,Culvert #2,0,30.5
Culvert Bottom n=0.012
Culvert Bottom Depth=0
Culvert Depth Blocked=0
Culvert=2,16,16,43,0.012,0.4,1,8,2,853.1,5017,852.89,5017,Culvert #3,0,30.5
Culvert Bottom n=0.012
Culvert Bottom Depth=0
Culvert Depth Blocked=0
BC Design=,,0,,0,,,,,,

Type RM Length L Ch R = 1,38659,221,221,221
BEGIN DESCRIPTION:
SR 1197 d/s HC
END DESCRIPTION:
XS GIS Cut Line= 5
      1292374.65       649646.62      1292040.08       649409.63
      1291934.13       649337.14      1291803.09       649222.83
      1291797.52       649075.06
#Sta/Elev= 30
  4469.4  895.55  4499.5  894.63  4577.7  886.64  4604.6  885.01  4625.2  883.01
  4659.8  877.85  4700.7  872.83  4706.6  872.95  4740.7  867.98  4756.2  867.49
  4802.7  868.75  4814.0  866.05  4822.8  865.00  4850.7  864.74  4886.3  863.21
  4928.1  862.75  4934.4  863.64  4969.8  862.03  4973.3  859.75  4975.1  852.08
  5024.9  852.15  5025.8  859.75  5043.5  860.67  5055.5  863.19  5081.8  863.95
  5115.0  872.88  5157.1  879.10  5197.6  882.80  5308.1  894.85  5329.5  896.25
#Mann=3,-1,0
  4469.4     0.1       0  4973.3    0.05       0  5025.8    0.12       0
#XS Ineff=2,0
    0.00 4943.50  872.29 5056.50    0.00  872.10
Bank Sta=4973.3,5025.8
XS Rating Curve= 0
Exp/Cntr=0.5,0.3

Type RM Length L Ch R = 1,38438,269,269,269
BEGIN DESCRIPTION:
Howards Creek 77.0
END DESCRIPTION:
XS GIS Cut Line= 3
      1292363.49       649569.39      1292062.38       649218.09
      1291992.68       649045.23
#Sta/Elev= 30
  4489.7  888.40  4525.8  885.81  4546.4  885.43  4581.4  878.46  4608.5  876.29
  4622.8  871.92  4664.2  867.09  4711.3  865.13  4725.9  863.78  4794.9  861.68
  4816.0  861.83  4831.0  861.11  4894.5  861.04  4900.7  861.47  4936.9  860.89
  4965.8  861.68  4981.5  857.27  4987.8  854.90  4988.8  853.45  4990.3  850.45
  5009.7  850.45  5011.2  853.45  5012.6  855.77  5019.0  861.46  5028.4  862.07
  5047.0  868.70  5058.2  871.82  5073.4  874.89  5091.2  879.99  5138.7  890.01
#Mann=3,-1,0
  4489.7     0.1       0  4988.8    0.05       0  5011.2    0.15       0
Bank Sta=4988.8,5011.2
XS Rating Curve= 0
Exp/Cntr=0.3,0.1

Type RM Length L Ch R = 1,38169,411,411,411
BEGIN DESCRIPTION:
Howards Creek 76.5
END DESCRIPTION:
XS GIS Cut Line= 3
      1292479.48       649450.89      1292250.86       649024.32
      1292100.30       648912.80
#Sta/Elev= 30
  4604.2  886.23  4611.6  885.25  4627.4  881.08  4656.2  879.06  4680.0  874.21
  4759.5  865.21  4788.1  863.45  4807.9  863.22  4824.9  861.39  4869.8  860.24
  4885.9  860.88  4942.8  860.14  4965.5  862.17  4981.1  853.77  4988.8  853.19
  4990.3  850.19  5009.7  850.19  5011.2  853.19  5013.9  857.33  5033.6  862.12
  5049.5  860.79  5075.3  861.78  5094.2  861.65  5121.0  862.72  5156.8  866.32
  5177.4  870.64  5204.7  879.79  5225.0  885.21  5239.3  890.34  5275.6  896.65
#Mann=3,-1,0
  4604.2     0.1       0  4988.8    0.05       0  5011.2    0.15       0
Bank Sta=4988.8,5011.2
XS Rating Curve= 0
Exp/Cntr=0.3,0.1

Type RM Length L Ch R = 1,37758,463,463,463
BEGIN DESCRIPTION:
Howards Creek 76.0
END DESCRIPTION:
XS GIS Cut Line= 3
      1292744.34       649230.64      1292643.97       648820.79
      1292250.86       648647.93
#Sta/Elev= 30
  4440.9  879.56  4469.0  876.00  4500.2  873.03  4519.8  869.83  4544.2  866.92
  4594.7  861.95  4620.2  861.65  4627.0  862.18  4671.4  859.63  4729.1  858.45
  4791.8  858.23  4830.6  859.07  4857.1  858.95  4875.4  858.12  4945.0  859.40
  4982.3  853.80  4988.8  851.94  4990.3  848.94  5009.7  848.94  5011.2  851.94
  5015.9  857.13  5025.9  860.73  5039.5  859.74  5069.3  859.04  5091.2  859.80
  5116.3  862.50  5137.5  867.03  5182.1  872.62  5205.7  876.96  5292.3  895.13
#Mann=3,-1,0
  4440.9    0.15       0  4988.8    0.05       0  5011.2    0.15       0
Bank Sta=4988.8,5011.2
XS Rating Curve= 0
Exp/Cntr=0.3,0.1

Type RM Length L Ch R = 1,37295,296,296,296
BEGIN DESCRIPTION:
Howards Creek 75.0
END DESCRIPTION:
XS GIS Cut Line= 2
      1292931.14       648299.42      1292175.00       648475.00
#Sta/Elev= 30
  4772.9  884.66  4795.7  879.96  4838.7  872.98  4860.2  868.21  4877.3  865.44
  4916.1  860.68  4928.5  859.74  4950.3  858.64  4958.5  859.36  4984.1  852.92
  4988.8  850.61  4990.3  847.61  5009.7  847.61  5011.2  850.61  5023.6  857.91
  5030.7  858.75  5109.9  858.42  5159.7  857.27  5221.9  857.31  5249.3  858.61
  5296.5  863.79  5303.1  863.99  5336.8  870.20  5389.3  878.08  5402.0  880.80
  5438.0  886.32  5465.5  892.33  5524.9  902.58  5542.3  906.19  5549.2  906.75
#Mann=3,-1,0
  4772.9    0.15       0  4988.8    0.05       0  5011.2    0.15       0
Bank Sta=4988.8,5011.2
XS Rating Curve= 0
Exp/Cntr=0.3,0.1

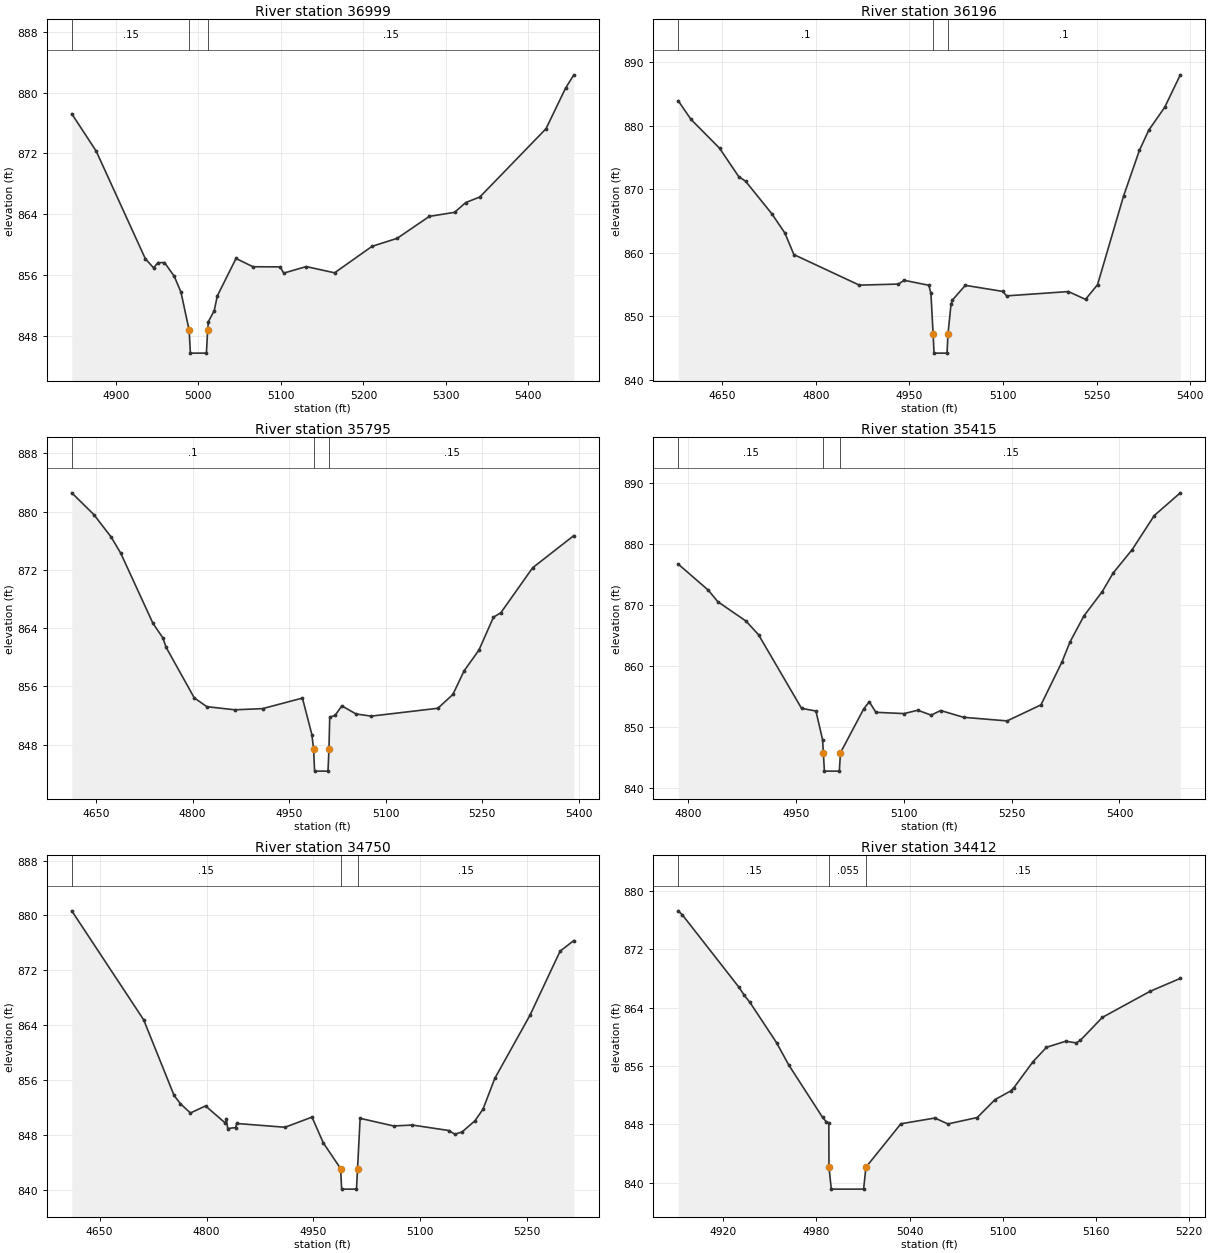
Type RM Length L Ch R = 1,36999,803,803,803
BEGIN DESCRIPTION:
Howards Creek 74.0
END DESCRIPTION:
XS GIS Cut Line= 3
      1292838.94       648077.79      1292627.24       648052.68
      1292238.94       648127.79
#Sta/Elev= 30
  4846.5  877.21  4876.1  872.29  4935.6  858.13  4945.6  856.92  4951.1  857.60
  4958.9  857.61  4970.7  855.81  4978.9  853.70  4988.8  848.68  4990.3  845.68
  5009.7  845.68  5011.2  848.68  5012.1  849.83  5019.2  851.28  5022.9  853.21
  5045.6  858.15  5066.1  857.06  5099.0  857.04  5103.4  856.22  5130.7  857.08
  5165.1  856.26  5210.5  859.75  5240.9  860.80  5279.9  863.69  5310.6  864.23
  5324.0  865.51  5341.3  866.26  5421.4  875.25  5445.3  880.64  5455.1  882.34
#Mann=3,-1,0
  4846.5    0.15       0  4988.8    0.05       0  5011.2    0.15       0
Bank Sta=4988.8,5011.2
XS Rating Curve= 0
Exp/Cntr=0.3,0.1

Type RM Length L Ch R = 1,36196,401,401,401
BEGIN DESCRIPTION:
Howards Creek 73.0
END DESCRIPTION:
XS GIS Cut Line= 3
      1292964.60       647663.75      1292814.05       647331.97
      1292418.14       647139.59
#Sta/Elev= 30
  4579.7  883.94  4600.1  881.01  4645.9  876.47  4676.7  871.99  4687.5  871.29
  4729.7  866.15  4750.6  863.12  4765.0  859.73  4869.9  854.92  4932.5  855.09
  4941.7  855.68  4981.3  854.90  4984.6  853.61  4988.1  847.22  4989.6  844.22
  5010.4  844.22  5011.9  847.22  5016.8  851.89  5019.0  852.57  5039.7  854.89
  5099.9  853.93  5105.8  853.23  5204.9  853.91  5232.3  852.68  5251.6  855.00
  5293.2  868.92  5318.8  876.17  5333.7  879.32  5359.1  882.90  5384.2  888.02
#Mann=3,-1,0
  4579.7     0.1       0  4988.1    0.05       0  5011.9     0.1       0
Bank Sta=4988.1,5011.9
XS Rating Curve= 0
Exp/Cntr=0.3,0.1

Type RM Length L Ch R = 1,35795,380,380,380
BEGIN DESCRIPTION:
Howards Creek 72.0
END DESCRIPTION:
XS GIS Cut Line= 3
      1293296.38       647379.36      1292984.12       646938.85
      1293078.91       646718.59
#Sta/Elev= 30
  4612.5  882.57  4646.8  879.58  4673.7  876.50  4688.5  874.29  4738.6  864.65
  4754.0  862.65  4759.0  861.36  4802.8  854.41  4822.3  853.21  4865.8  852.78
  4908.8  852.94  4970.7  854.39  4985.4  849.37  4988.1  847.36  4989.6  844.36
  5010.4  844.36  5011.9  847.36  5013.1  851.78  5021.3  852.00  5031.9  853.32
  5053.9  852.21  5077.5  851.91  5181.0  852.99  5204.4  854.89  5221.7  858.12
  5244.8  860.98  5267.4  865.50  5278.8  866.10  5328.2  872.28  5392.2  876.70
#Mann=3,-1,0
  4612.5     0.1       0  4988.1    0.05       0  5011.9    0.15       0
Bank Sta=4988.1,5011.9
XS Rating Curve= 0
Exp/Cntr=0.3,0.1

Type RM Length L Ch R = 1,35415,665,665,665
BEGIN DESCRIPTION:
Howards Creek 71.0
END DESCRIPTION:
XS GIS Cut Line= 3
      1293432.99       647270.63      1293413.48       646924.91
      1293375.00       646575.00
#Sta/Elev= 30
  4786.3  876.73  4828.2  872.45  4841.3  870.57  4880.7  867.38  4898.0  865.15
  4957.8  853.09  4977.8  852.65  4987.1  847.92  4988.1  845.80  4989.6  842.80
  5010.4  842.80  5011.9  845.80  5044.4  853.03  5052.0  854.16  5061.2  852.44
  5100.4  852.23  5119.4  852.78  5138.1  851.98  5151.3  852.73  5183.3  851.62
  5243.7  851.03  5290.8  853.66  5319.8  860.64  5331.3  864.00  5350.5  868.23
  5375.8  872.18  5391.2  875.27  5417.5  879.08  5448.4  884.69  5484.6  888.41
#Mann=3,-1,0
  4786.3    0.15       0  4988.1    0.05       0  5011.9    0.15       0
Bank Sta=4988.1,5011.9
XS Rating Curve= 0
Exp/Cntr=0.3,0.1

Type RM Length L Ch R = 1,34750,338,338,338
BEGIN DESCRIPTION:
Howards Creek 70.0
END DESCRIPTION:
XS GIS Cut Line= 4
      1294166.26       647203.72      1293962.73       646977.88
      1293870.72       646830.12      1293853.99       646604.28
#Sta/Elev= 30
  4610.9  880.68  4711.8  864.79  4754.5  853.76  4763.2  852.58  4777.4  851.21
  4798.6  852.24  4826.5  849.73  4827.8  850.38  4829.7  848.94  4840.9  849.09
  4842.2  849.68  4910.1  849.13  4948.0  850.61  4963.7  846.88  4988.1  843.11
  4989.6  840.11  5010.4  840.11  5011.9  843.11  5015.5  850.43  5062.5  849.32
  5089.0  849.45  5140.3  848.65  5148.3  848.11  5158.6  848.45  5176.8  850.09
  5188.0  851.78  5204.5  856.26  5253.8  865.45  5296.1  874.80  5315.4  876.35
#Mann=3,-1,0
  4610.9    0.15       0  4988.1    0.05       0  5011.9    0.15       0
Bank Sta=4988.1,5011.9
XS Rating Curve= 0
Exp/Cntr=0.3,0.1

Type RM Length L Ch R = 1,34412,373,373,373
BEGIN DESCRIPTION:
Howards Creek 69.0
END DESCRIPTION:
XS GIS Cut Line= 2
      1294281.23       646951.95      1294147.41       646657.53
#Sta/Elev= 29
  4891.0  877.29  4893.7  876.73  4930.2  866.79  4933.4  865.75  4937.2  864.73
  4954.3  859.22  4962.2  856.15  4984.0  848.96  4986.3  848.38  4988.0  848.22
  4988.1  842.13  4989.6  839.13  5010.4  839.13  5011.9  842.13  5034.4  848.09
  5056.3  848.88  5064.7  848.07  5083.6  848.95  5095.1  851.41  5105.1  852.59
  5107.2  853.04  5119.5  856.60  5128.2  858.58  5140.6  859.41  5147.4  859.18
  5150.0  859.53  5164.2  862.68  5194.8  866.24  5214.4  868.03
#Mann=3,-1,0
  4891.0    0.15       0  4988.1   0.055       0  5011.9    0.15       0
Bank Sta=4988.1,5011.9
XS Rating Curve= 0
Exp/Cntr=0.3,0.1

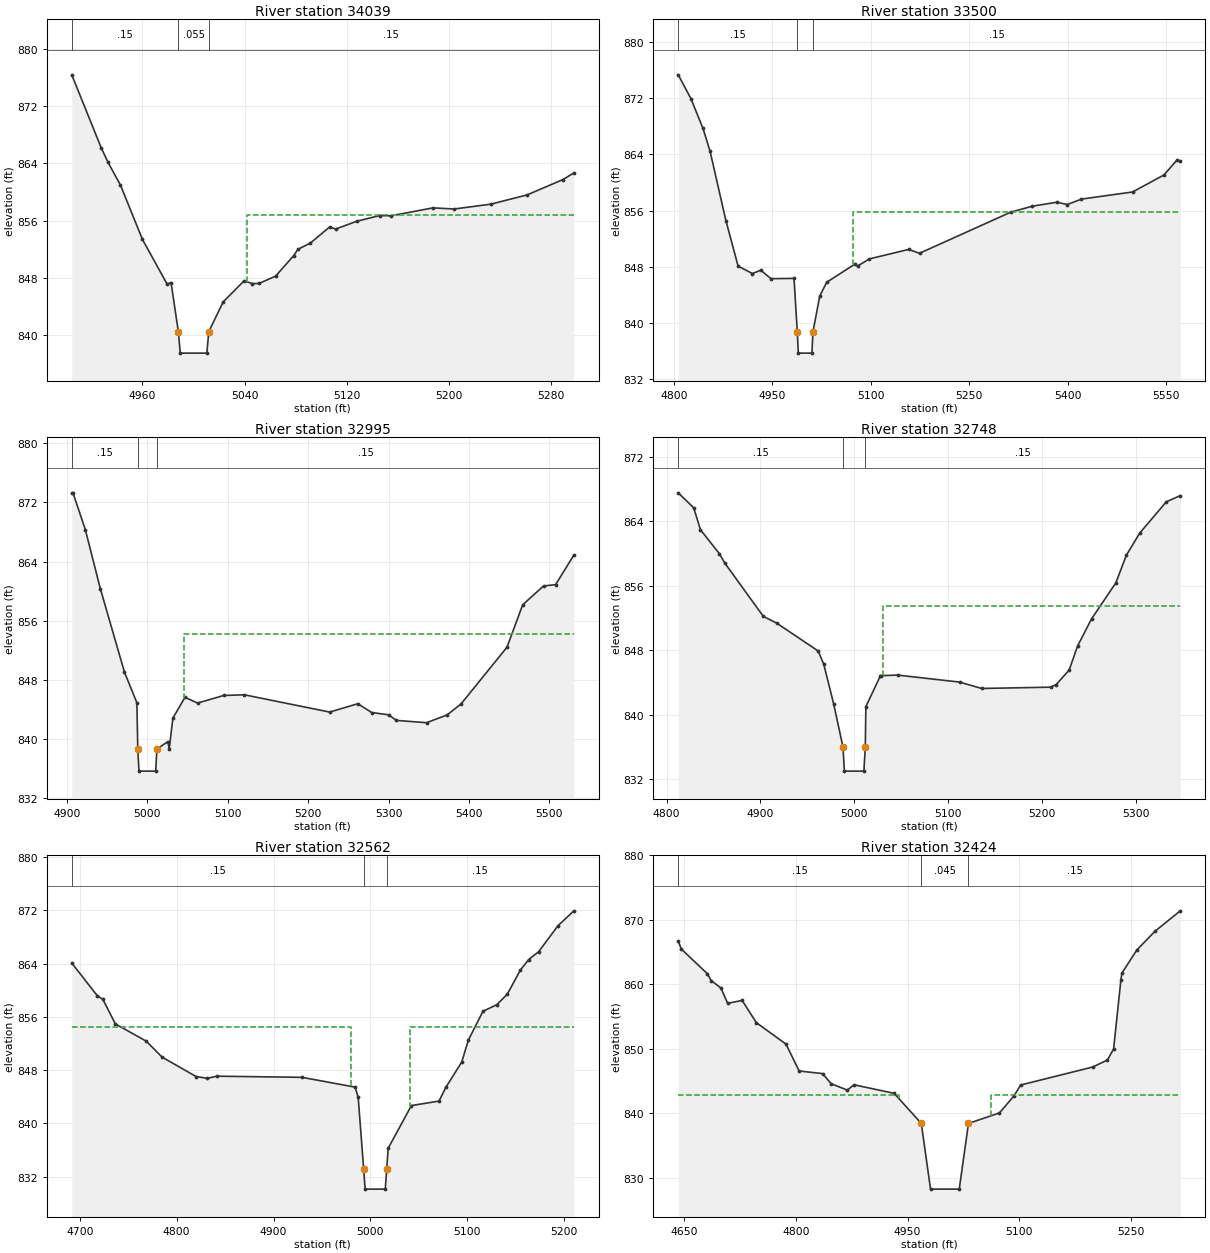
Type RM Length L Ch R = 1,34039,539,539,539
BEGIN DESCRIPTION:
Howards Creek 68.0
END DESCRIPTION:
XS GIS Cut Line= 2
      1294652.38       646805.64      1294388.30       646514.79
#Sta/Elev= 30
  4904.7  876.36  4927.7  866.18  4933.1  864.12  4942.8  860.96  4960.0  853.36
  4979.3  847.12  4982.4  847.33  4988.1  840.47  4989.6  837.47  5010.4  837.47
  5011.9  840.47  5023.2  844.63  5039.5  847.57  5046.0  847.19  5051.1  847.20
  5064.2  848.23  5078.4  851.10  5081.7  851.98  5091.4  852.85  5106.5  855.10
  5111.2  854.81  5127.8  855.90  5145.7  856.70  5154.6  856.66  5187.4  857.77
  5203.9  857.61  5232.7  858.29  5261.0  859.58  5288.9  861.71  5297.6  862.65
#Mann=3,-1,0
  4904.7    0.15       0  4988.1   0.055       0  5011.9    0.15       0
#XS Ineff=2,0
       0                 5041.50    0.00  856.71
Bank Sta=4988.1,5011.9
XS Rating Curve= 0
Exp/Cntr=0.3,0.1

Type RM Length L Ch R = 1,33500,505,505,505
BEGIN DESCRIPTION:
Howards Creek 67.0
END DESCRIPTION:
XS GIS Cut Line= 5
      1295125.24       646360.44      1294932.05       646353.28
      1294871.76       646349.55      1294609.77       646473.29
      1294390.08       646501.40
#Sta/Elev= 30
  4806.7  875.29  4826.0  871.91  4844.4  867.67  4855.1  864.46  4879.3  854.58
  4897.9  848.11  4919.7  847.05  4932.5  847.52  4948.0  846.32  4983.1  846.36
  4988.1  838.74  4989.6  835.74  5010.4  835.74  5011.9  838.74  5022.3  843.86
  5032.9  845.81  5075.6  848.38  5079.9  848.11  5097.9  849.13  5157.9  850.48
  5174.3  849.93  5313.0  855.76  5346.0  856.62  5383.4  857.18  5399.7  856.86
  5421.0  857.63  5498.8  858.64  5546.7  861.06  5566.7  863.20  5571.6  863.06
#Mann=3,-1,0
  4806.7    0.15       0  4988.1    0.06       0  5011.9    0.15       0
#XS Ineff=2,0
       0                 5073.60    0.00  855.86
Bank Sta=4988.1,5011.9
XS Rating Curve= 0
Exp/Cntr=0.3,0.1

Type RM Length L Ch R = 1,32995,247,247,247
BEGIN DESCRIPTION:
Howards Creek 66.0
END DESCRIPTION:
XS GIS Cut Line= 3
      1294884.35       645796.58      1294784.42       645933.98
      1294363.32       646105.28
#Sta/Elev= 30
  4906.0  873.22  4907.5  873.31  4922.9  868.31  4941.5  860.34  4971.5  849.03
  4987.0  844.87  4988.1  838.61  4989.6  835.61  5010.4  835.61  5011.9  838.61
  5025.6  839.61  5027.2  838.61  5031.8  842.79  5046.8  845.61  5062.5  844.83
  5095.0  845.86  5120.7  845.95  5226.8  843.61  5261.8  844.74  5279.1  843.55
  5300.0  843.24  5309.9  842.48  5347.3  842.17  5372.8  843.22  5390.1  844.70
  5447.3  852.39  5466.9  858.15  5492.8  860.69  5507.8  860.87  5530.5  864.88
#Mann=3,-1,0
  4906.0    0.15       0  4988.1    0.06       0  5011.9    0.15       0
#XS Ineff=2,0
       0                 5045.50    0.00  854.13
Bank Sta=4988.1,5011.9
XS Rating Curve= 0
Exp/Cntr=0.3,0.1

Type RM Length L Ch R = 1,32748,186,186,186
BEGIN DESCRIPTION:
Howards Creek 65.5
END DESCRIPTION:
XS GIS Cut Line= 3
      1294777.29       645768.92      1294629.18       645781.41
      1294291.94       645970.56
#Sta/Elev= 30
  4812.5  867.52  4829.0  865.66  4836.2  862.94  4856.4  859.96  4862.1  858.81
  4903.2  852.19  4917.7  851.33  4961.7  847.89  4967.6  846.25  4978.1  841.37
  4988.1  835.98  4989.6  832.98  5010.4  832.98  5011.9  835.98  5012.5  840.99
  5027.9  844.78  5029.0  844.83  5046.5  844.90  5112.4  844.03  5135.9  843.24
  5209.6  843.40  5215.4  843.73  5229.2  845.52  5238.3  848.54  5253.1  851.88
  5279.0  856.35  5290.2  859.78  5304.5  862.53  5332.7  866.40  5347.7  867.18
#Mann=3,-1,0
  4812.5    0.15       0  4988.1    0.06       0  5011.9    0.15       0
#XS Ineff=2,0
       0                 5030.40    0.00  853.45
Bank Sta=4988.1,5011.9
XS Rating Curve= 0
Exp/Cntr=0.3,0.1

Type RM Length L Ch R = 1,32562,138,138,138
BEGIN DESCRIPTION:
Howards Ceek 65.0
END DESCRIPTION:
XS GIS Cut Line= 3
      1294749.04       645749.44      1294500.28       645684.13
      1294241.79       645721.65
#Sta/Elev= 30
  4691.7  864.08  4717.9  859.20  4723.8  858.63  4736.7  854.94  4768.6  852.35
  4785.0  849.95  4820.0  847.04  4831.8  846.76  4841.3  847.09  4929.3  846.92
  4984.2  845.45  4987.4  843.97  4993.1  833.13  4994.6  830.13  5015.4  830.13
  5016.9  833.13  5018.4  836.27  5042.4  842.68  5070.9  843.35  5078.0  845.43
  5094.3  849.20  5101.2  852.51  5116.3  856.84  5130.7  857.83  5141.5  859.43
  5154.9  863.03  5163.5  864.61  5173.8  865.79  5193.7  869.68  5210.1  871.92
#Mann=3,-1,0
  4691.7    0.15       0  4993.1    0.06       0  5016.9    0.15       0
#XS Ineff=2,0
    0.00 4979.80  854.45 5041.00    0.00  854.45
Bank Sta=4993.1,5016.9
XS Rating Curve= 0
Exp/Cntr=0.3,0.1

Type RM Length L Ch R = 1,32424,74,74,74
BEGIN DESCRIPTION:
Howards Creek Mill Rd u/s HC
END DESCRIPTION:
XS GIS Cut Line= 3
      1294778.22       645735.55      1294390.49       645521.53
      1294159.79       645520.14
#Sta/Elev= 30
  4642.3  866.67  4646.6  865.45  4681.3  861.64  4686.6  860.56  4699.5  859.43
  4708.6  857.04  4728.1  857.49  4747.1  854.04  4786.9  850.71  4804.5  846.54
  4836.1  846.13  4847.4  844.56  4869.3  843.57  4878.0  844.40  4932.0  843.07
  4968.4  838.40  4980.8  828.20  5019.3  828.20  5031.7  838.40  5073.3  840.03
  5092.9  842.70  5101.7  844.36  5198.2  847.15  5218.0  848.23  5226.4  849.95
  5236.2  860.69  5237.5  861.72  5257.5  865.31  5281.8  868.22  5315.9  871.40
#Mann=3,-1,0
  4642.3    0.15       0  4968.4   0.045       0  5031.7    0.15       0
#XS Ineff=2,0
    0.00 4938.50  842.80 5061.50    0.00  842.80
Bank Sta=4968.4,5031.7
XS Rating Curve= 0
Exp/Cntr=0.5,0.3