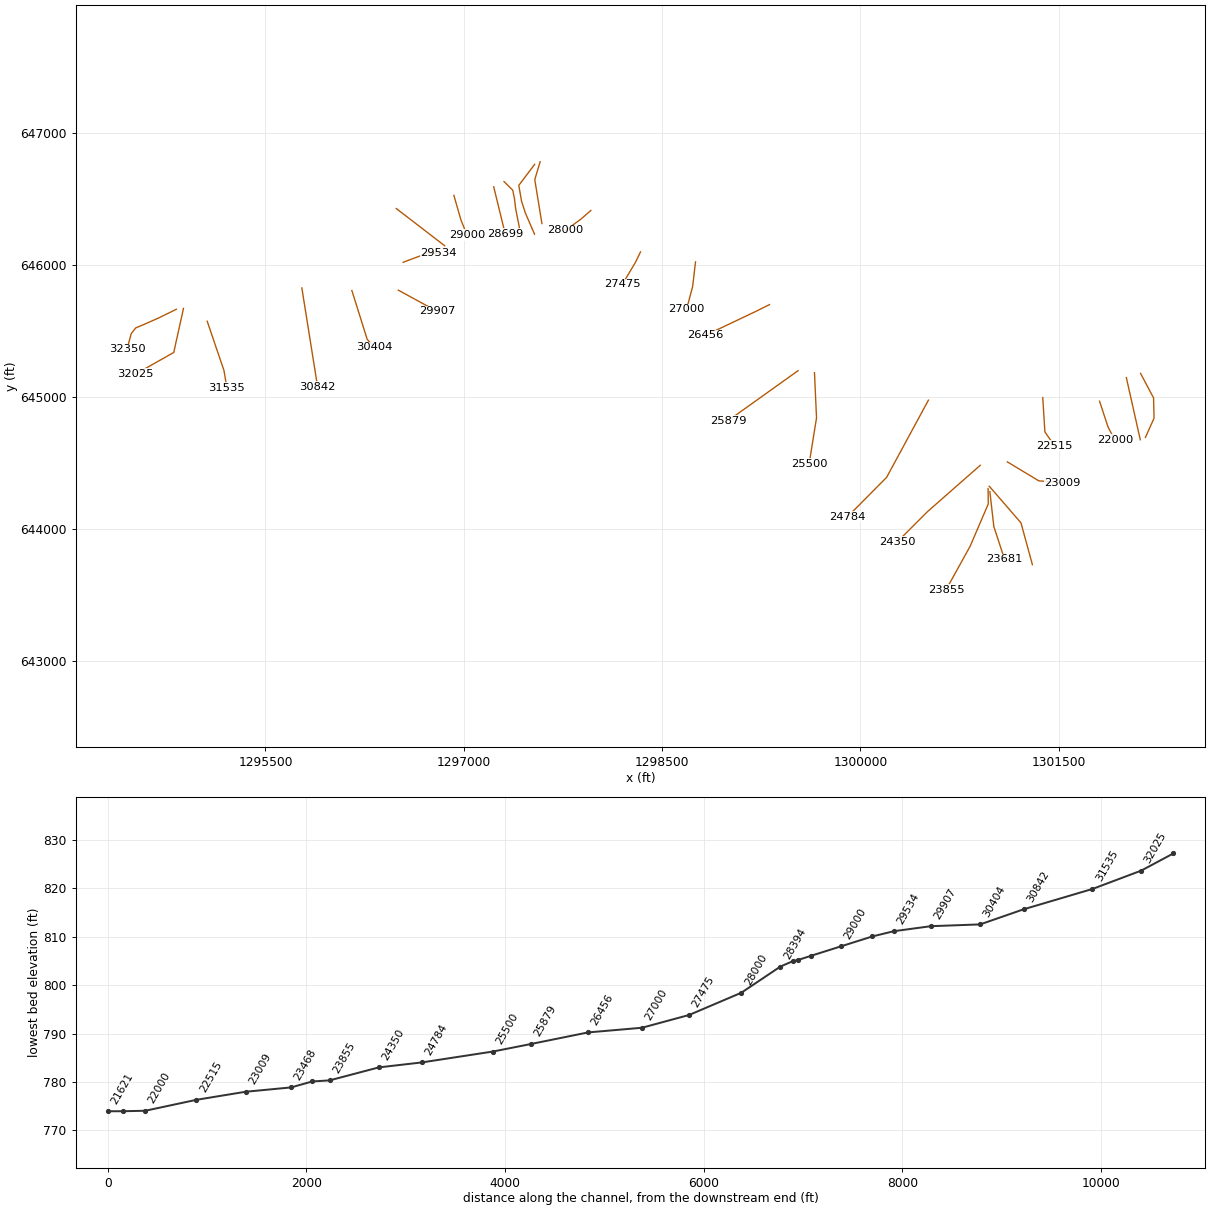
HEC-RAS study Howards Creek.prj: Howards Creek Limited Detail Study

--- Howards Creek.g01 (geometry) --- (continued)

Type RM Length L Ch R =3,32395,,,
BEGIN DESCRIPTION:
Howards Creek Mill Rd TOR HC
Structure ID: LDS_HC_06
Approximate Survey Structure
END DESCRIPTION:
Bridge Culvert--1,0,-1,-1,0
Deck Dist Width WeirC Skew NumUp NumDn MinLoCord MaxHiCord MaxSubmerge Is_Ogee
16.5,25,3,,43,43,,,,0,1,1,,,
  4606.8  4626.7  4670.4  4678.7  4764.0  4771.5  4842.9  4866.9  4873.7  4930.0
  4955.0  4955.0  5045.0  5045.0  5081.1  5092.6  5100.7  5111.8  5150.3  5153.3
  5159.7  5160.5  5197.3  5203.8  5210.7  5215.5  5223.1  5238.0  5239.1  5247.5
  5249.4  5269.4  5287.0  5300.8  5303.1  5306.2  5320.0  5335.3  5335.5  5347.7
  5360.0  5363.9  5378.9
  867.93  866.47  862.67  862.19  854.61  853.50  847.57  846.04  845.35  842.80
  842.80  842.80  842.80  842.80  842.80  842.98  842.87  843.07  843.71  843.77
  843.72  843.74  845.03  844.66  845.13  845.20  845.81  846.93  846.98  848.41
  848.94  854.79  857.83  858.81  858.89  859.31  861.60  863.07  863.08  864.82
  867.11  867.58  869.63
  808.20  808.20  808.20  808.20  808.20  808.20  808.20  808.20  808.20  808.20
  808.20  840.30  840.30  808.20  808.20  808.20  808.20  808.20  808.20  808.20
  808.20  808.20  808.20  808.20  808.20  808.20  808.20  808.20  808.20  808.20
  808.20  808.20  808.20  808.20  808.20  808.20  808.20  808.20  808.20  808.20
  808.20  808.20  808.20
  4606.8  4626.7  4670.4  4678.7  4764.0  4771.5  4842.9  4866.9  4873.7  4930.0
  4955.0  4955.0  5045.0  5045.0  5081.1  5092.6  5100.7  5111.8  5150.3  5153.3
  5159.7  5160.5  5197.3  5203.8  5210.7  5215.5  5223.1  5238.0  5239.1  5247.5
  5249.4  5269.4  5287.0  5300.8  5303.1  5306.2  5320.0  5335.3  5335.5  5347.7
  5360.0  5363.9  5378.9
  867.93  866.47  862.67  862.19  854.61  853.50  847.57  846.04  845.35  842.80
  842.80  842.80  842.80  842.80  842.80  842.98  842.87  843.07  843.71  843.77
  843.72  843.74  845.03  844.66  845.13  845.20  845.81  846.93  846.98  848.41
  848.94  854.79  857.83  858.81  858.89  859.31  861.60  863.07  863.08  864.82
  867.11  867.58  869.63
  808.20  808.20  808.20  808.20  808.20  808.20  808.20  808.20  808.20  808.20
  808.20  840.30  840.30  808.20  808.20  808.20  808.20  808.20  808.20  808.20
  808.20  808.20  808.20  808.20  808.20  808.20  808.20  808.20  808.20  808.20
  808.20  808.20  808.20  808.20  808.20  808.20  808.20  808.20  808.20  808.20
  808.20  808.20  808.20
Pier Skew, UpSta & Num, DnSta & Num=,4977.5,2,4977.5,2,0,0,0,0,0
       1       1
  830.91  840.30
       1       1
  830.66  840.30
Pier Skew, UpSta & Num, DnSta & Num=,5022.5,2,5022.5,2,0,0,0,0,0
       1       1
  830.83  840.30
       1       1
  830.58  840.30
BR Coef=1,1,0,1.25,0,,,0.8,0,2,0,
WSPro=,,,, 1 ,,,, 0 ,,,, 0 ,,,,-1 ,-1 ,-1 , 0 , 0 , 0 , 0 , 0
BC Design=,,0,,0,,,,,,

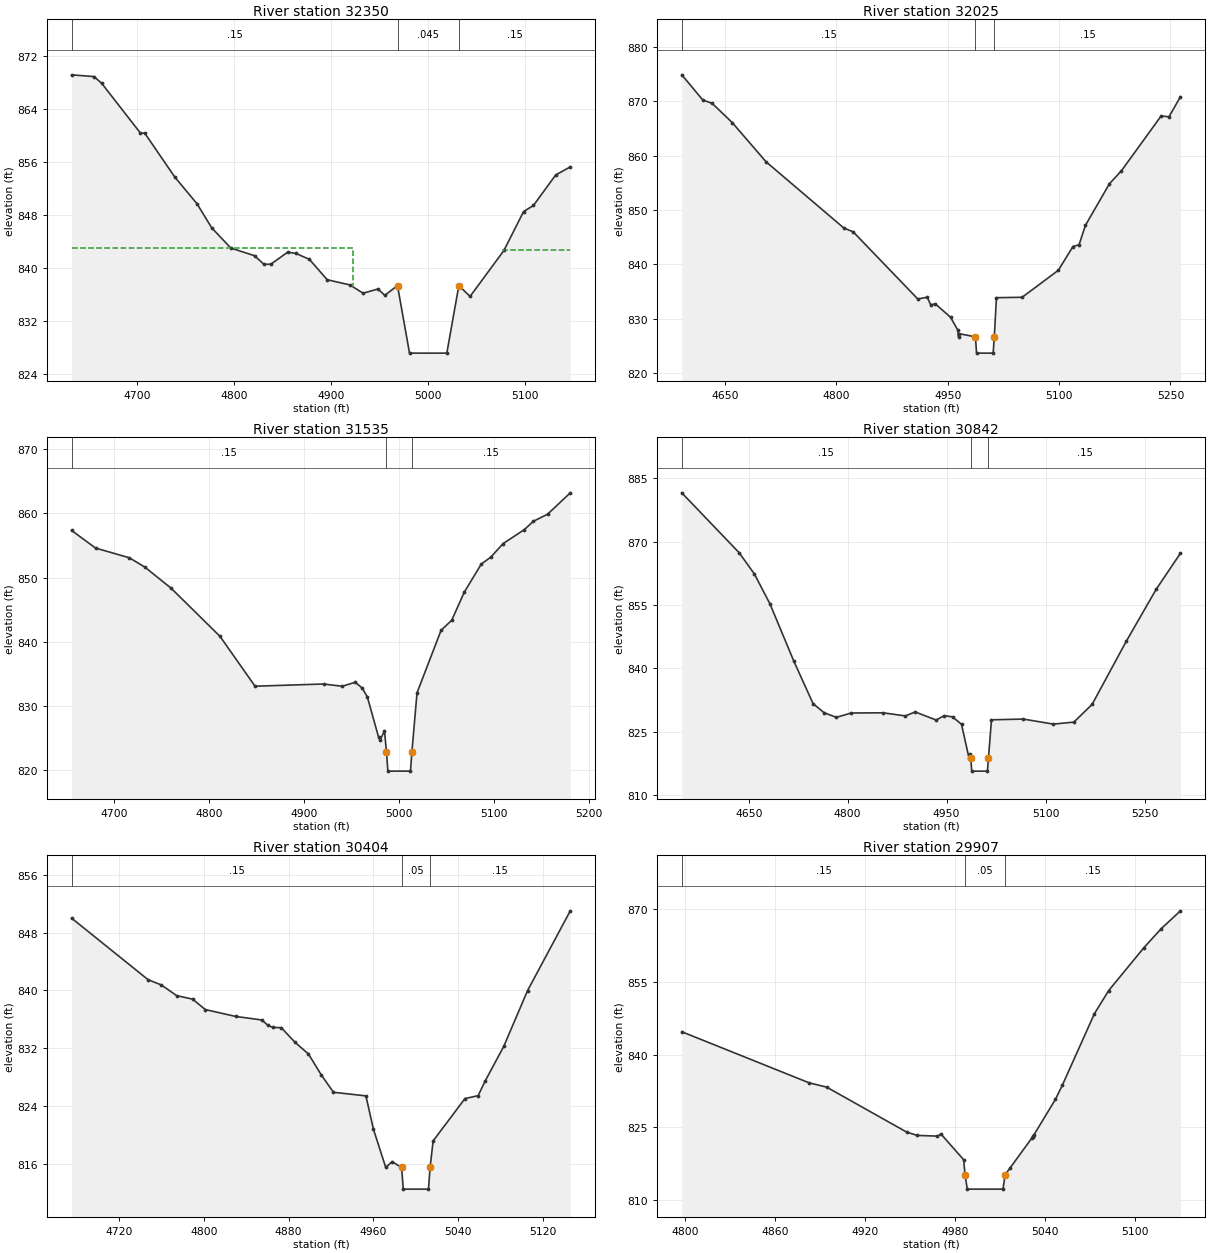
Type RM Length L Ch R = 1,32350,325,325,325
BEGIN DESCRIPTION:
Howards Creek Mill Rd d/s HC
END DESCRIPTION:
XS GIS Cut Line= 6
      1294825.46       645663.65      1294691.64       645597.63
      1294586.36       645551.23      1294518.55       645522.68
      1294484.65       645479.86      1294452.53       645362.09
#Sta/Elev= 30
  4632.1  869.23  4655.3  868.96  4663.2  867.94  4703.1  860.44  4707.6  860.42
  4738.5  853.81  4761.5  849.76  4776.7  846.12  4796.4  843.07  4820.9  841.91
  4830.6  840.61  4837.7  840.63  4855.0  842.44  4863.5  842.26  4877.5  841.36
  4895.9  838.28  4919.3  837.50  4932.9  836.25  4948.2  836.88  4955.3  835.93
  4968.4  837.40  4980.8  827.20  5019.3  827.20  5031.7  837.40  5043.3  835.76
  5078.2  842.70  5098.5  848.58  5108.7  849.50  5131.6  854.10  5146.7  855.33
#Mann=3,-1,0
  4632.1    0.15       0  4968.4   0.045       0  5031.7    0.15       0
#XS Ineff=2,0
    0.00 4922.50  843.14 5077.50    0.00  842.80
Bank Sta=4968.4,5031.7
XS Rating Curve= 0
Exp/Cntr=0.5,0.3

Type RM Length L Ch R = 1,32025,490,490,490
BEGIN DESCRIPTION:
Howards Creek 64.0
END DESCRIPTION:
XS GIS Cut Line= 3
      1294879.67       645670.23      1294806.02       645336.69
      1294518.34       645174.10
#Sta/Elev= 30
  4591.6  874.88  4619.8  870.26  4632.5  869.63  4659.5  866.10  4705.2  858.86
  4810.1  846.66  4822.5  845.98  4909.6  833.61  4922.4  833.93  4927.1  832.52
  4933.1  832.73  4953.7  830.26  4963.6  827.86  4964.6  826.64  4964.7  827.23
  4987.3  826.64  4988.8  823.64  5011.2  823.64  5012.7  826.64  5015.6  833.85
  5050.2  833.92  5099.0  838.89  5118.7  843.27  5126.9  843.59  5135.6  847.19
  5167.9  854.83  5184.1  857.23  5237.5  867.30  5248.1  867.16  5263.6  870.85
#Mann=3,-1,0
  4591.6    0.15       0  4987.3    0.05       0  5012.7    0.15       0
Bank Sta=4987.3,5012.7
XS Rating Curve= 0
Exp/Cntr=0.3,0.1

Type RM Length L Ch R = 1,31535,693,693,693
BEGIN DESCRIPTION:
Howards Creek 63.0
END DESCRIPTION:
XS GIS Cut Line= 3
      1295058.99       645573.05      1295186.00       645200.13
      1295207.62       645070.42
#Sta/Elev= 30
  4654.8  857.35  4680.0  854.61  4715.7  853.09  4732.0  851.64  4759.6  848.36
  4811.2  840.85  4848.1  833.09  4920.5  833.43  4939.9  833.08  4953.7  833.70
  4960.9  832.82  4966.4  831.44  4978.3  825.15  4980.0  824.75  4984.5  826.13
  4986.6  822.86  4988.1  819.86  5011.9  819.86  5013.4  822.86  5018.8  832.06
  5044.1  841.78  5055.4  843.37  5068.6  847.74  5086.5  852.11  5096.6  853.20
  5109.5  855.30  5132.0  857.49  5141.3  858.77  5156.3  859.87  5180.3  863.21
#Mann=3,-1,0
  4654.8    0.15       0  4986.6    0.05       0  5013.4    0.15       0
Bank Sta=4986.6,5013.4
XS Rating Curve= 0
Exp/Cntr=0.3,0.1

Type RM Length L Ch R = 1,30842,438,438,438
BEGIN DESCRIPTION:
Howards Creek 62.0
END DESCRIPTION:
XS GIS Cut Line= 2
      1295775.00       645825.00      1295894.00       645078.53
#Sta/Elev= 30
  4548.6  881.59  4635.6  867.39  4658.6  862.38  4682.2  855.30  4718.4  841.72
  4747.6  831.65  4764.5  829.48  4782.8  828.40  4805.5  829.43  4853.5  829.48
  4887.6  828.74  4902.3  829.68  4934.3  827.76  4946.3  828.81  4959.0  828.51
  4972.6  826.76  4984.1  818.66  4985.8  819.81  4986.6  818.66  4988.1  815.66
  5011.9  815.66  5013.4  818.66  5018.0  827.82  5066.3  827.99  5111.8  826.80
  5142.9  827.27  5170.6  831.48  5222.2  846.39  5267.6  858.72  5304.5  867.29
#Mann=3,-1,0
  4548.6    0.15       0  4986.6    0.05       0  5013.4    0.15       0
Bank Sta=4986.6,5013.4
XS Rating Curve= 0
Exp/Cntr=0.3,0.1

Type RM Length L Ch R = 1,30404,497,497,497
BEGIN DESCRIPTION:
Howards Creek 61.0
END DESCRIPTION:
XS GIS Cut Line= 3
      1296153.42       645805.45      1296269.62       645435.23
      1296326.37       645375.78
#Sta/Elev= 30
  4675.4  850.00  4747.6  841.48  4760.1  840.76  4774.4  839.29  4789.5  838.80
  4801.5  837.36  4830.1  836.41  4854.8  835.92  4860.4  835.19  4865.1  834.89
  4873.1  834.86  4886.0  832.84  4898.7  831.23  4910.8  828.33  4922.3  825.93
  4952.9  825.43  4960.0  820.81  4971.6  815.54  4977.5  816.33  4986.6  815.54
  4988.1  812.54  5011.9  812.54  5013.4  815.54  5016.3  819.21  5046.3  825.06
  5058.7  825.46  5065.5  827.53  5082.9  832.28  5105.3  839.98  5145.6  851.01
#Mann=3,-1,0
  4675.4    0.15       0  4986.6    0.05       0  5013.4    0.15       0
Bank Sta=4986.6,5013.4
XS Rating Curve= 0
Exp/Cntr=0.3,0.1

Type RM Length L Ch R = 1,29907,373,373,373
BEGIN DESCRIPTION:
Howards Creek 60.0
END DESCRIPTION:
XS GIS Cut Line= 2
      1296504.72       645808.15      1296796.57       645648.72
#Sta/Elev= 24
  4797.7  844.71  4882.6  834.15  4894.3  833.26  4947.6  823.98  4954.6  823.28
  4968.0  823.13  4970.7  823.52  4985.7  818.24  4986.6  815.17  4988.1  812.17
  5011.9  812.17  5013.4  815.17  5016.5  816.48  5031.1  822.70  5031.7  822.95
  5032.0  823.10  5032.3  823.26  5046.9  830.73  5051.5  833.65  5072.9  848.44
  5082.4  853.22  5105.9  862.09  5117.5  866.04  5130.3  869.71
#Mann=3,-1,0
  4797.7    0.15       0  4986.6    0.05       0  5013.4    0.15       0
Bank Sta=4986.6,5013.4
XS Rating Curve= 0
Exp/Cntr=0.3,0.1

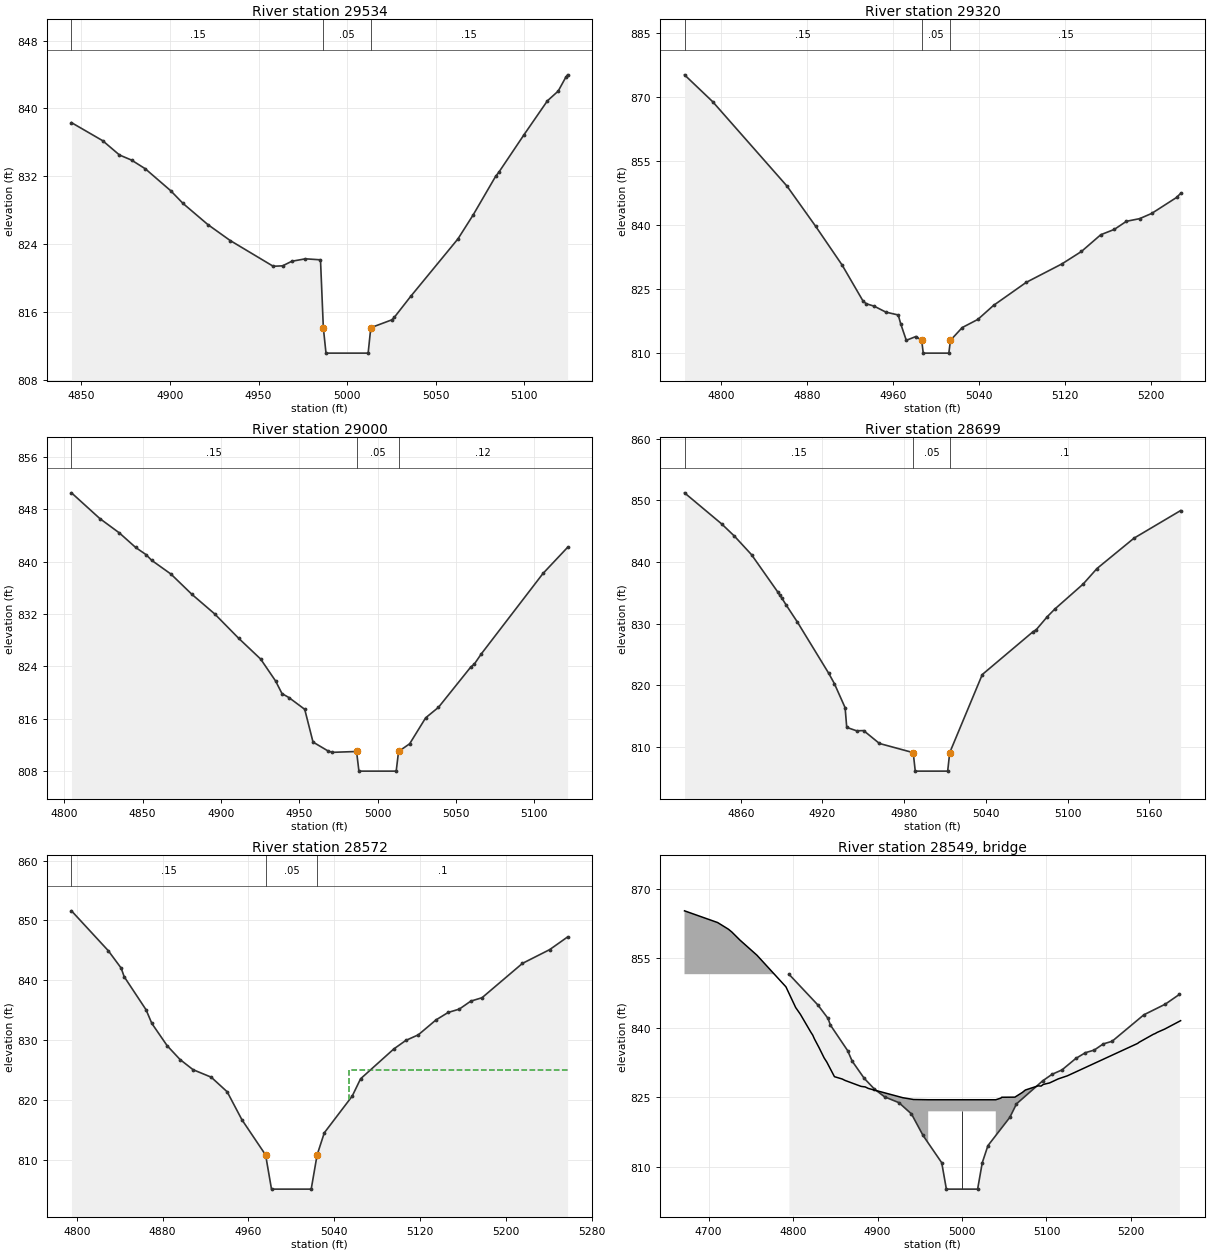
Type RM Length L Ch R = 1,29534,214,214,214
BEGIN DESCRIPTION:
Howards Creek 59.5
END DESCRIPTION:
XS GIS Cut Line= 3
      1296541.30       646018.90      1296720.53       646086.35
      1296809.17       646088.28
#Sta/Elev= 30
  4844.4  838.33  4862.0  836.20  4871.5  834.51  4878.3  833.91  4886.1  832.88
  4900.4  830.30  4907.4  828.79  4921.4  826.30  4934.0  824.42  4958.3  821.38
  4963.6  821.43  4968.8  821.97  4976.5  822.26  4985.0  822.14  4986.6  814.13
  4988.1  811.13  5011.9  811.13  5013.4  814.13  5025.3  815.06  5026.7  815.36
  5035.9  817.82  5062.6  824.61  5071.2  827.44  5083.9  832.00  5085.6  832.45
  5099.9  836.90  5113.1  840.90  5119.2  842.05  5123.5  843.69  5124.5  843.97
#Mann=3,-1,0
  4844.4    0.15       0  4986.6    0.05       0  5013.4    0.15       0
Bank Sta=4986.6,5013.4
XS Rating Curve= 0
Exp/Cntr=0.3,0.1

Type RM Length L Ch R = 1,29320,320,320,320
BEGIN DESCRIPTION:
Howards Creek 59.0
END DESCRIPTION:
XS GIS Cut Line= 2
      1296489.27       646425.52      1296855.43       646144.16
#Sta/Elev= 30
  4765.9  875.20  4792.1  868.92  4861.3  849.15  4888.0  839.73  4912.6  830.67
  4932.2  822.19  4935.2  821.61  4942.5  821.04  4953.3  819.66  4964.8  818.99
  4967.1  816.93  4972.3  813.06  4981.3  813.95  4986.6  813.06  4988.1  810.06
  5011.9  810.06  5013.4  813.06  5024.4  816.05  5038.9  817.95  5053.5  821.23
  5083.9  826.62  5117.1  830.94  5135.3  833.85  5153.3  837.77  5165.9  839.02
  5177.2  840.92  5189.4  841.53  5200.7  842.76  5223.8  846.49  5227.6  847.45
#Mann=3,-1,0
  4765.9    0.15       0  4986.6    0.05       0  5013.4    0.15       0
Bank Sta=4986.6,5013.4
XS Rating Curve= 0
Exp/Cntr=0.3,0.1

Type RM Length L Ch R = 1,29000,301,301,301
BEGIN DESCRIPTION:
Howards Creek 58.0
END DESCRIPTION:
XS GIS Cut Line= 3
      1296925.00       646525.00      1296979.14       646337.28
      1297025.00       646225.00
#Sta/Elev= 30
  4804.6  850.50  4822.7  846.57  4835.2  844.37  4845.6  842.15  4852.2  841.06
  4855.8  840.19  4868.1  838.09  4881.5  834.99  4896.0  832.01  4911.3  828.29
  4925.4  825.10  4934.9  821.76  4939.0  819.83  4943.4  819.23  4953.5  817.43
  4958.8  812.43  4968.6  811.04  4971.2  810.86  4986.6  810.99  4988.1  807.99
  5011.9  807.99  5013.4  810.99  5020.5  812.17  5030.7  816.13  5038.9  817.74
  5059.4  823.86  5061.8  824.35  5066.2  825.89  5105.6  838.18  5121.3  842.17
#Mann=3,-1,0
  4804.6    0.15       0  4986.6    0.05       0  5013.4    0.12       0
Bank Sta=4986.6,5013.4
XS Rating Curve= 0
Exp/Cntr=0.3,0.1

Type RM Length L Ch R = 1,28699,127,127,127
BEGIN DESCRIPTION:
Howard Creek 57.5
END DESCRIPTION:
XS GIS Cut Line= 2
      1297226.36       646590.05      1297312.78       646236.28
#Sta/Elev= 29
  4818.7  851.22  4846.0  846.17  4855.4  844.18  4867.9  841.18  4887.2  835.11
  4888.5  834.65  4890.1  834.15  4893.5  832.95  4901.6  830.23  4924.6  821.91
  4928.7  820.26  4936.6  816.34  4937.8  813.14  4945.0  812.59  4950.2  812.62
  4961.8  810.53  4986.6  809.04  4988.1  806.04  5011.9  806.04  5013.4  809.04
  5037.3  821.72  5074.5  828.66  5076.9  829.00  5085.1  831.13  5090.5  832.34
  5111.3  836.40  5121.5  838.93  5148.7  843.86  5182.9  848.34
#Mann=3,-1,0
  4818.7    0.15       0  4986.6    0.05       0  5013.4     0.1       0
Bank Sta=4986.6,5013.4
XS Rating Curve= 0
Exp/Cntr=0.5,0.3

Type RM Length L Ch R = 1,28572,54,54,54
BEGIN DESCRIPTION:
SR 1193 u/s HC
END DESCRIPTION:
XS GIS Cut Line= 6
      1297304.38       646629.51      1297370.02       646564.89
      1297383.36       646500.27      1297392.59       646423.35
      1297420.28       646283.86      1297399.77       646201.81
#Sta/Elev= 30
  4795.1  851.61  4829.4  844.96  4841.4  842.06  4844.2  840.63  4864.6  835.11
  4870.0  832.83  4884.3  829.11  4896.3  826.81  4908.4  825.12  4925.3  823.87
  4940.2  821.43  4953.9  816.78  4976.0  810.90  4981.5  805.20  5018.5  805.20
  5024.0  810.90  5030.7  814.59  5056.7  820.71  5064.5  823.60  5095.5  828.58
  5106.7  830.00  5118.3  830.93  5134.8  833.42  5146.1  834.66  5156.5  835.22
  5167.2  836.55  5177.7  837.12  5215.3  842.84  5240.7  845.14  5257.4  847.25
#Mann=3,-1,0
  4795.1    0.15       0  4976.0    0.05       0  5024.0     0.1       0
#XS Ineff=2,0
    0.00 4946.00  818.02 5054.00    0.00  825.05
Bank Sta=4976,5024
XS Rating Curve= 0
Exp/Cntr=0.5,0.3

Type RM Length L Ch R =3,28549,,,
BEGIN DESCRIPTION:
SR 1193 TOR HC
Structure ID: LDS_HC_05
Approximate Survey Structure
END DESCRIPTION:
Bridge Culvert--1,0,-1,-1,0
Deck Dist Width WeirC Skew NumUp NumDn MinLoCord MaxHiCord MaxSubmerge Is_Ogee
14,18,3,,45,45,,,,0,1,1,,,
  4671.5  4710.7  4723.5  4727.5  4737.1  4757.3  4791.6  4803.1  4808.7  4821.4
  4823.3  4825.2  4830.8  4836.8  4839.9  4849.0  4858.3  4861.4  4880.6  4885.4
  4889.1  4929.9  4942.7  4960.0  4960.0  5040.0  5040.0  5045.9  5047.0  5062.6
  5071.4  5075.0  5090.1  5093.6  5096.3  5103.7  5113.9  5124.8  5207.9  5209.6
  5226.5  5228.9  5230.9  5240.0  5258.8
  865.29  862.76  861.32  860.72  858.98  855.70  848.87  844.41  842.94  838.98
  838.46  837.67  835.74  833.53  832.65  829.48  828.97  828.68  827.38  827.27
  826.94  824.94  824.55  824.50  824.50  824.50  824.50  824.85  825.04  825.06
  826.07  826.60  827.50  827.45  827.81  828.13  829.00  829.67  836.66  836.90
  838.63  838.81  839.03  839.76  841.57
  785.20  785.20  785.20  785.20  785.20  785.20  785.20  785.20  785.20  785.20
  785.20  785.20  785.20  785.20  785.20  785.20  785.20  785.20  785.20  785.20
  785.20  785.20  785.20  785.20  822.00  822.00  785.20  785.20  785.20  785.20
  785.20  785.20  785.20  785.20  785.20  785.20  785.20  785.20  785.20  785.20
  785.20  785.20  785.20  785.20  785.20
  4671.5  4710.7  4723.5  4727.5  4737.1  4757.3  4791.6  4803.1  4808.7  4821.4
  4823.3  4825.2  4830.8  4836.8  4839.9  4849.0  4858.3  4861.4  4880.6  4885.4
  4889.1  4929.9  4942.7  4960.0  4960.0  5040.0  5040.0  5045.9  5047.0  5062.6
  5071.4  5075.0  5090.1  5093.6  5096.3  5103.7  5113.9  5124.8  5207.9  5209.6
  5226.5  5228.9  5230.9  5240.0  5258.8
  865.29  862.76  861.32  860.72  858.98  855.70  848.87  844.41  842.94  838.98
  838.46  837.67  835.74  833.53  832.65  829.48  828.97  828.68  827.38  827.27
  826.94  824.94  824.55  824.50  824.50  824.50  824.50  824.85  825.04  825.06
  826.07  826.60  827.50  827.45  827.81  828.13  829.00  829.67  836.66  836.90
  838.63  838.81  839.03  839.76  841.57
  785.20  785.20  785.20  785.20  785.20  785.20  785.20  785.20  785.20  785.20
  785.20  785.20  785.20  785.20  785.20  785.20  785.20  785.20  785.20  785.20
  785.20  785.20  785.20  785.20  822.00  822.00  785.20  785.20  785.20  785.20
  785.20  785.20  785.20  785.20  785.20  785.20  785.20  785.20  785.20  785.20
  785.20  785.20  785.20  785.20  785.20
Pier Skew, UpSta & Num, DnSta & Num=,5000,2,5000,2,0,0,0,0,0
       1       1
  805.20  822.00
       1       1
  804.95  822.00
BR Coef=1,1,0,1.25,0,,,0.8,0,2,0,
WSPro=,,,, 1 ,,,, 0 ,,,, 0 ,,,,-1 ,-1 ,-1 , 0 , 0 , 0 , 0 , 0
BC Design=,,0,,0,,,,,,

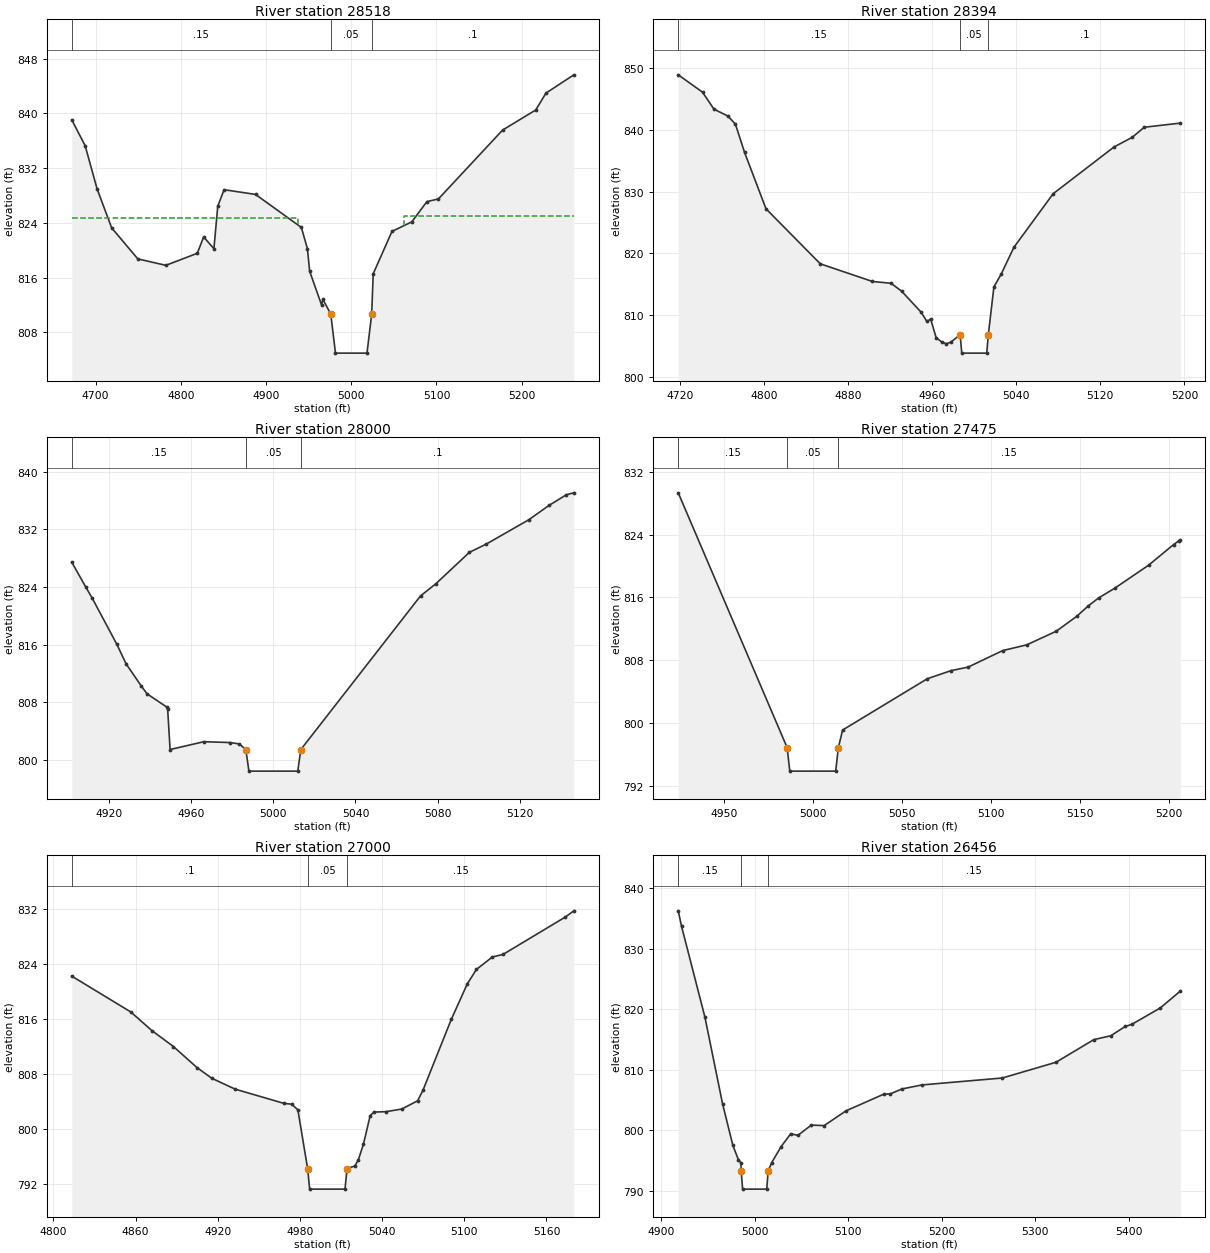
Type RM Length L Ch R = 1,28518,124,124,124
BEGIN DESCRIPTION:
SR 1193 d/s HC
END DESCRIPTION:
XS GIS Cut Line= 5
      1297536.18       646759.77      1297416.18       646600.79
      1297436.69       646482.84      1297464.38       646395.66
      1297535.15       646231.55
#Sta/Elev= 30
  4672.1  839.07  4687.8  835.28  4701.8  828.97  4718.9  823.27  4749.6  818.73
  4782.5  817.79  4819.4  819.55  4826.8  821.94  4838.9  820.23  4843.4  826.44
  4850.8  828.85  4887.7  828.16  4941.5  823.33  4948.6  820.22  4951.2  816.93
  4965.2  811.99  4966.7  812.84  4976.0  810.65  4981.5  804.95  5018.5  804.95
  5024.0  810.65  5025.8  816.56  5047.8  822.75  5071.1  824.15  5088.8  827.11
  5102.3  827.50  5177.6  837.57  5216.5  840.51  5228.5  842.98  5261.2  845.65
#Mann=3,-1,0
  4672.1    0.15       0  4976.0    0.05       0  5024.0     0.1       0
#XS Ineff=2,0
    0.00 4938.00  824.69 5062.00    0.00  825.06
Bank Sta=4976,5024
XS Rating Curve= 0
Exp/Cntr=0.5,0.3

Type RM Length L Ch R = 1,28394,394,394,394
BEGIN DESCRIPTION:
Howards Creek 57.0
END DESCRIPTION:
XS GIS Cut Line= 3
      1297577.54       646779.63      1297537.00       646644.51
      1297591.05       646312.13
#Sta/Elev= 30
  4718.3  848.97  4741.4  846.16  4752.3  843.40  4765.5  842.29  4772.7  840.98
  4781.4  836.40  4801.8  827.25  4853.5  818.32  4903.1  815.46  4920.8  815.17
  4930.8  813.90  4949.5  810.47  4954.9  808.98  4958.5  809.36  4963.8  806.32
  4969.4  805.62  4973.5  805.36  4977.9  805.63  4986.6  806.84  4988.1  803.84
  5011.9  803.84  5013.4  806.84  5018.7  814.57  5025.6  816.64  5037.7  820.99
  5075.1  829.69  5133.1  837.28  5150.3  838.83  5161.8  840.47  5196.1  841.14
#Mann=3,-1,0
  4718.3    0.15       0  4986.6    0.05       0  5013.4     0.1       0
Bank Sta=4986.6,5013.4
XS Rating Curve= 0
Exp/Cntr=0.3,0.1

Type RM Length L Ch R = 1,28000,525,525,525
BEGIN DESCRIPTION:
Howards Creek 56.0
END DESCRIPTION:
XS GIS Cut Line= 3
      1297961.26       646411.03      1297887.30       646346.47
      1297769.40       646259.71
#Sta/Elev= 25
  4901.8  827.46  4908.5  824.06  4911.7  822.49  4923.7  816.08  4928.3  813.32
  4935.7  810.24  4938.5  809.16  4948.1  807.33  4948.5  807.10  4949.7  801.43
  4966.2  802.52  4978.9  802.40  4983.4  802.21  4986.6  801.43  4988.1  798.43
  5011.9  798.43  5013.4  801.43  5071.7  822.77  5079.1  824.44  5095.5  828.82
  5103.8  829.98  5124.4  833.34  5134.3  835.34  5142.8  836.83  5146.4  837.09
#Mann=3,-1,0
  4901.8    0.15       0  4986.6    0.05       0  5013.4     0.1       0
Bank Sta=4986.6,5013.4
XS Rating Curve= 0
Exp/Cntr=0.3,0.1

Type RM Length L Ch R = 1,27475,475,475,475
BEGIN DESCRIPTION:
Howards Creek 55.0
END DESCRIPTION:
XS GIS Cut Line= 3
      1298336.88       646097.57      1298299.05       646019.20
      1298199.06       645851.66
#Sta/Elev= 20
  4924.4  829.32  4985.6  796.84  4987.1  793.84  5012.9  793.84  5014.4  796.84
  5016.8  799.08  5064.4  805.62  5077.7  806.65  5087.3  807.10  5106.8  809.21
  5120.3  809.94  5136.9  811.68  5148.4  813.58  5154.9  814.91  5160.7  815.92
  5169.9  817.18  5188.8  820.10  5202.8  822.72  5206.0  823.23  5206.6  823.34
#Mann=3,-1,0
  4924.4    0.15       0  4985.6    0.05       0  5014.4    0.15       0
Bank Sta=4985.6,5014.4
XS Rating Curve= 0
Exp/Cntr=0.3,0.1

Type RM Length L Ch R = 1,27000,544,544,544
BEGIN DESCRIPTION:
Howards Creek 54.0
END DESCRIPTION:
XS GIS Cut Line= 3
      1298753.03       646021.90      1298731.22       645836.63
      1298685.48       645662.50
#Sta/Elev= 30
  4813.4  822.22  4856.5  817.00  4871.9  814.29  4887.6  811.97  4904.9  808.89
  4915.6  807.35  4932.7  805.76  4968.3  803.69  4974.0  803.57  4978.5  802.74
  4985.6  794.20  4987.1  791.20  5012.9  791.20  5014.4  794.20  5020.0  794.56
  5022.6  795.43  5026.4  797.77  5031.3  801.91  5034.1  802.42  5042.8  802.48
  5054.3  802.86  5065.9  804.06  5069.9  805.63  5090.5  815.92  5102.2  821.09
  5108.9  823.20  5120.5  825.01  5128.3  825.38  5173.9  830.84  5180.0  831.73
#Mann=3,-1,0
  4813.4     0.1       0  4985.6    0.05       0  5014.4    0.15       0
Bank Sta=4985.6,5014.4
XS Rating Curve= 0
Exp/Cntr=0.3,0.1

Type RM Length L Ch R = 1,26456,577,577,577
BEGIN DESCRIPTION:
Howards Creek 53.0
END DESCRIPTION:
XS GIS Cut Line= 3
      1299312.41       645698.98      1299209.72       645647.63
      1298828.70       645466.58
#Sta/Elev= 30
  4918.3  836.28  4921.8  833.74  4946.8  818.70  4965.7  804.33  4976.7  797.46
  4982.6  795.10  4985.3  794.61  4985.6  793.23  4987.1  790.23  5012.9  790.23
  5014.4  793.23  5018.1  794.59  5028.1  797.23  5038.5  799.39  5046.2  799.13
  5060.6  800.83  5074.2  800.74  5097.7  803.19  5137.9  805.94  5144.7  805.97
  5157.2  806.80  5178.7  807.47  5264.7  808.62  5322.0  811.22  5362.5  814.97
  5380.5  815.60  5396.0  817.14  5403.0  817.49  5433.6  820.22  5454.9  823.00
#Mann=3,-1,0
  4918.3    0.15       0  4985.6    0.05       0  5014.4    0.15       0
Bank Sta=4985.6,5014.4
XS Rating Curve= 0
Exp/Cntr=0.3,0.1

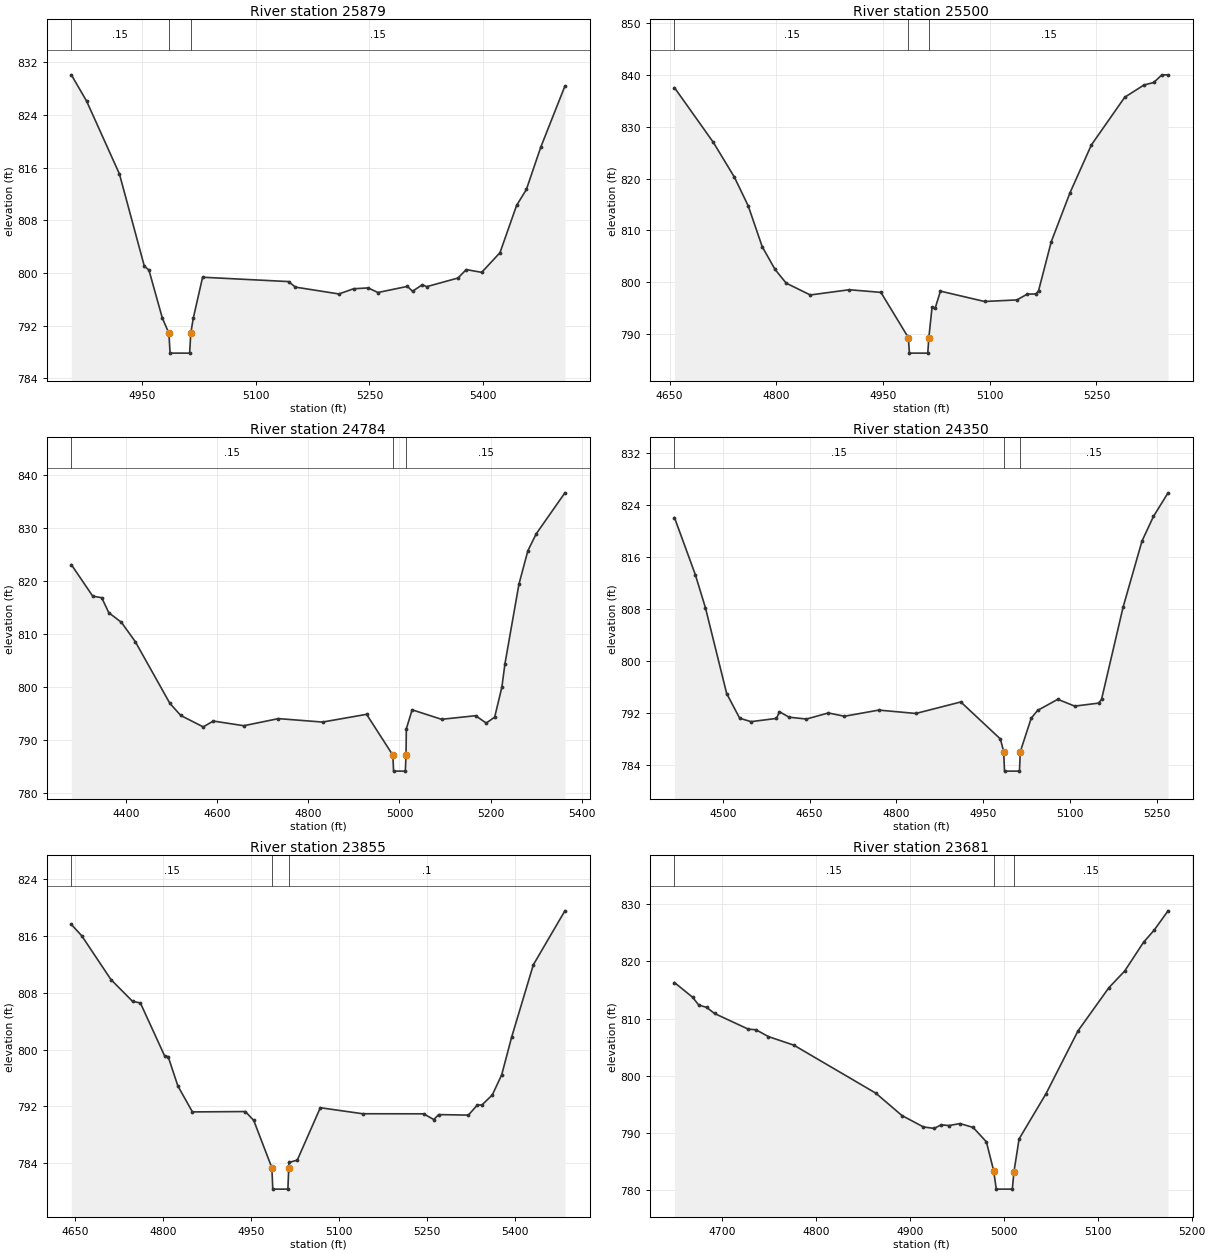
Type RM Length L Ch R = 1,25879,379,379,379
BEGIN DESCRIPTION:
Howards Creek 52.0
END DESCRIPTION:
XS GIS Cut Line= 2
      1299528.59       645199.05      1298998.94       644820.73
#Sta/Elev= 30
  4856.9  830.07  4877.0  826.09  4920.3  815.03  4953.2  801.01  4959.2  800.45
  4976.8  793.19  4985.6  790.83  4987.1  787.83  5012.9  787.83  5014.4  790.83
  5017.7  793.13  5030.0  799.35  5143.4  798.69  5152.4  797.85  5209.8  796.81
  5229.1  797.60  5248.4  797.73  5261.2  797.03  5300.1  797.96  5306.9  797.22
  5319.7  798.21  5325.6  797.92  5366.8  799.23  5377.7  800.51  5398.1  800.09
  5422.2  803.08  5444.1  810.25  5457.0  812.67  5476.0  819.10  5507.8  828.36
#Mann=3,-1,0
  4856.9    0.15       0  4985.6    0.05       0  5014.4    0.15       0
Bank Sta=4985.6,5014.4
XS Rating Curve= 0
Exp/Cntr=0.3,0.1

Type RM Length L Ch R = 1,25500,716,716,716
BEGIN DESCRIPTION:
Howards Creek 51.0
END DESCRIPTION:
XS GIS Cut Line= 3
      1299652.90       645184.19      1299668.35       644841.31
      1299612.37       644495.10
#Sta/Elev= 30
  4656.8  837.59  4711.5  827.00  4740.9  820.33  4760.5  814.74  4780.1  806.87
  4798.2  802.46  4813.8  799.82  4847.7  797.53  4902.5  798.54  4947.0  798.03
  4985.6  789.29  4987.1  786.29  5012.9  786.29  5014.4  789.29  5018.9  795.12
  5023.3  794.98  5030.7  798.27  5092.7  796.27  5138.2  796.57  5152.7  797.69
  5165.1  797.73  5168.7  798.37  5186.5  807.82  5212.8  817.26  5242.9  826.52
  5289.8  835.74  5316.8  838.10  5330.6  838.59  5342.0  840.06  5350.7  840.07
#Mann=3,-1,0
  4656.8    0.15       0  4985.6    0.05       0  5014.4    0.15       0
Bank Sta=4985.6,5014.4
XS Rating Curve= 0
Exp/Cntr=0.3,0.1

Type RM Length L Ch R = 1,24784,434,434,434
BEGIN DESCRIPTION:
Howards Creek 50.0
END DESCRIPTION:
XS GIS Cut Line= 3
      1300514.93       644976.11      1300198.76       644392.42
      1299904.21       644095.16
#Sta/Elev= 30
  4280.5  823.01  4327.5  817.05  4347.1  816.77  4362.6  813.94  4390.4  812.11
  4420.7  808.48  4496.5  796.84  4520.5  794.54  4569.7  792.39  4591.8  793.49
  4658.6  792.61  4734.7  793.95  4831.3  793.30  4927.9  794.76  4985.6  787.04
  4987.1  784.04  5012.9  784.04  5014.4  787.04  5015.1  792.04  5027.8  795.61
  5092.3  793.82  5166.9  794.50  5190.3  793.11  5208.8  794.23  5224.6  799.89
  5231.4  804.34  5262.0  819.31  5281.5  825.61  5299.9  828.82  5362.8  836.56
#Mann=3,-1,0
  4280.5    0.15       0  4985.6    0.05       0  5014.4    0.15       0
Bank Sta=4985.6,5014.4
XS Rating Curve= 0
Exp/Cntr=0.3,0.1

Type RM Length L Ch R = 1,24350,495,495,495
BEGIN DESCRIPTION:
Howards Creek 49.0
END DESCRIPTION:
XS GIS Cut Line= 3
      1300906.77       644483.21      1300506.83       644131.92
      1300279.83       643904.92
#Sta/Elev= 30
  4416.5  822.01  4452.5  813.24  4470.0  808.14  4506.7  794.95  4529.2  791.15
  4548.8  790.62  4592.8  791.12  4598.0  792.15  4614.5  791.31  4644.6  791.02
  4682.6  791.96  4710.3  791.45  4769.7  792.40  4833.8  791.88  4911.5  793.65
  4980.0  787.95  4985.6  786.01  4987.1  783.01  5012.9  783.01  5014.4  786.01
  5033.2  791.15  5044.3  792.35  5079.2  794.06  5108.4  793.01  5149.6  793.47
  5154.8  794.04  5192.1  808.24  5224.8  818.41  5244.6  822.19  5269.8  825.82
#Mann=3,-1,0
  4416.5    0.15       0  4985.6    0.05       0  5014.4    0.15       0
Bank Sta=4985.6,5014.4
XS Rating Curve= 0
Exp/Cntr=0.3,0.1

Type RM Length L Ch R = 1,23855,174,174,174
BEGIN DESCRIPTION:
Howards Creek 48.0
END DESCRIPTION:
XS GIS Cut Line= 4
      1300966.22       644307.57      1300967.52       644190.81
      1300831.10       643872.50      1300647.35       643540.11
#Sta/Elev= 30
  4643.1  817.62  4660.9  816.02  4710.8  809.85  4747.6  806.79  4761.0  806.56
  4802.3  799.12  4808.5  798.98  4825.1  794.85  4849.9  791.21  4940.3  791.26
  4954.6  790.01  4985.6  783.33  4987.1  780.33  5012.9  780.33  5014.4  783.33
  5014.6  784.09  5028.9  784.41  5068.3  791.80  5140.6  790.95  5244.7  790.94
  5262.1  790.13  5270.4  790.83  5321.2  790.76  5336.2  792.16  5344.6  792.21
  5362.1  793.61  5378.1  796.45  5394.9  801.70  5432.1  811.94  5486.0  819.54
#Mann=3,-1,0
  4643.1    0.15       0  4985.6    0.05       0  5014.4     0.1       0
Bank Sta=4985.6,5014.4
XS Rating Curve= 0
Exp/Cntr=0.3,0.1

Type RM Length L Ch R = 1,23681,213,213,213
BEGIN DESCRIPTION:
Howards Creek 47.5
END DESCRIPTION:
XS GIS Cut Line= 3
      1300979.73       644283.24      1301009.45       644021.12
      1301090.52       643772.51
#Sta/Elev= 30
  4649.6  816.31  4669.0  813.72  4675.4  812.37  4683.8  811.96  4692.2  810.89
  4728.2  808.14  4736.3  808.04  4749.6  806.84  4776.6  805.34  4863.8  796.93
  4891.7  793.00  4914.5  791.01  4925.9  790.75  4933.4  791.38  4941.6  791.25
  4953.5  791.60  4967.4  790.92  4981.5  788.40  4989.3  783.29  4992.0  780.11
  5009.1  780.11  5010.8  783.11  5016.3  788.91  5045.0  796.85  5079.0  807.85
  5111.8  815.40  5128.7  818.34  5148.8  823.39  5159.8  825.45  5174.8  828.88
#Mann=3,-1,0
  4649.6    0.15       0  4989.3    0.06       0  5010.8    0.15       0
Bank Sta=4989.3,5010.8
XS Rating Curve= 0
Exp/Cntr=0.3,0.1

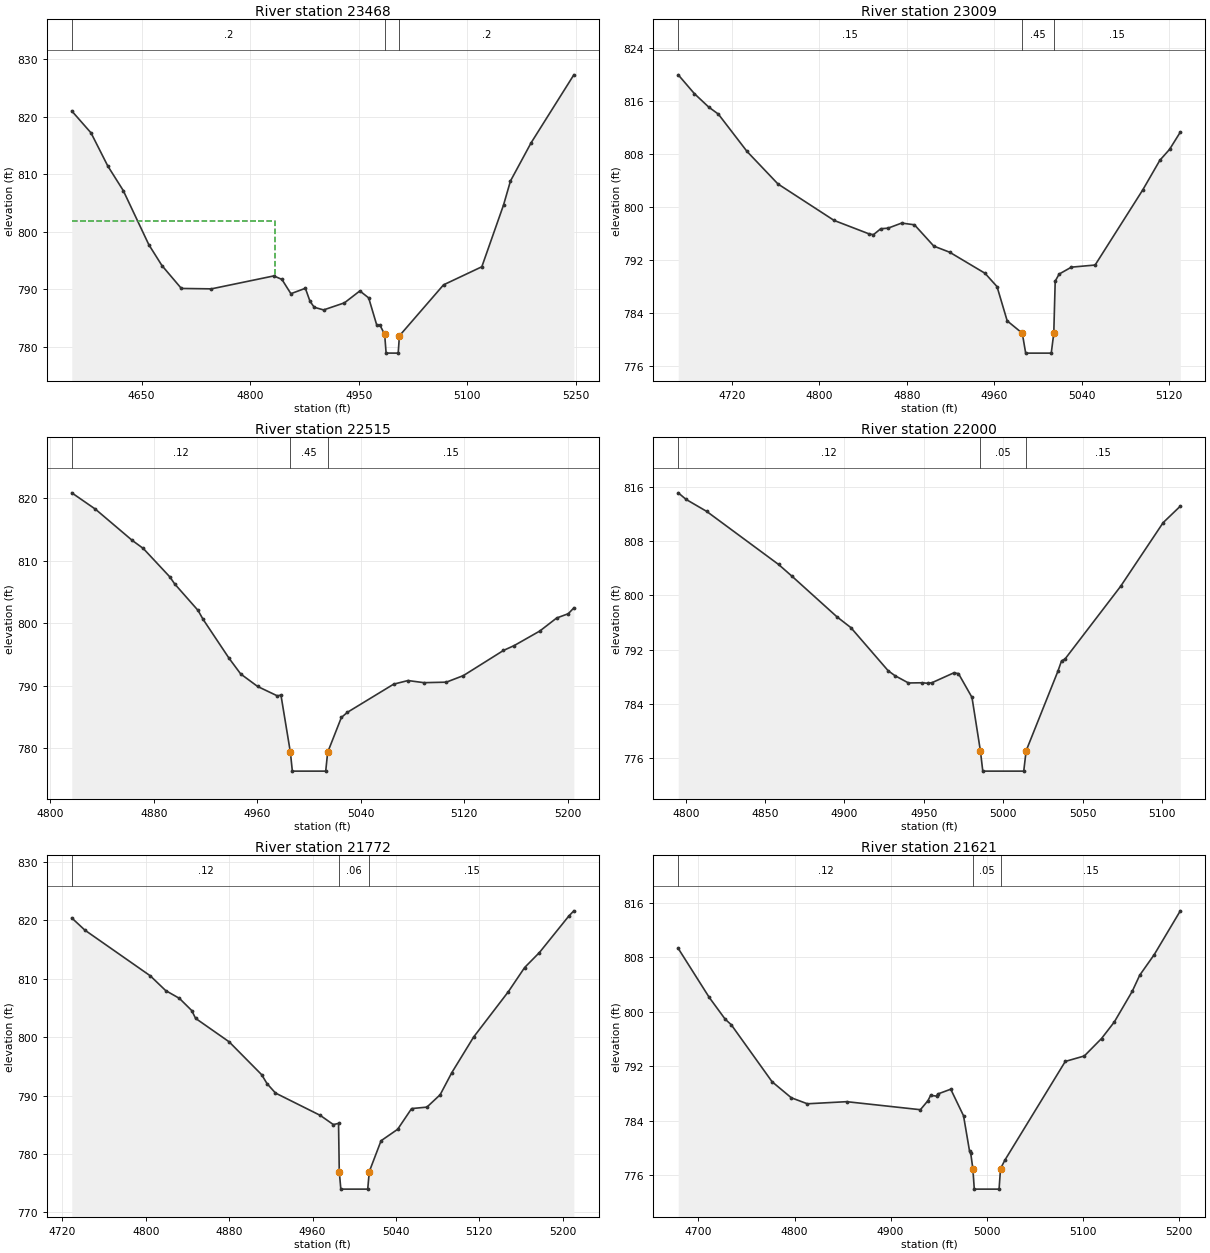
Type RM Length L Ch R = 1,23468,459,459,459
BEGIN DESCRIPTION:
Howards Creek 47.0
END DESCRIPTION:
XS GIS Cut Line= 3
      1300975.00       644325.00      1301214.83       644048.14
      1301301.30       643731.98
#Sta/Elev= 30
  4553.4  820.97  4580.0  817.16  4603.2  811.40  4624.6  807.13  4659.9  797.73
  4678.1  794.09  4704.9  790.12  4746.4  790.05  4832.7  792.30  4843.9  791.69
  4856.3  789.21  4876.3  790.15  4882.6  787.92  4888.5  786.85  4901.5  786.39
  4930.3  787.62  4951.6  789.69  4963.8  788.48  4975.0  783.74  4979.6  783.69
  4985.9  782.14  4987.9  778.89  5004.6  778.88  5006.3  781.89  5067.3  790.75
  5120.2  793.89  5150.2  804.62  5159.8  808.80  5188.3  815.43  5247.4  827.25
#Mann=3,-1,0
  4553.4     0.2       0  4985.9    0.06       0  5006.3     0.2       0
#XS Ineff=2,0
    0.00 4833.70  801.88               0
Bank Sta=4985.9,5006.3
XS Rating Curve= 0
Exp/Cntr=0.3,0.1

Type RM Length L Ch R = 1,23009,494,494,494
BEGIN DESCRIPTION:
Howards Creek 46.0
END DESCRIPTION:
XS GIS Cut Line= 3
      1301112.14       644508.89      1301349.94       644365.66
      1301531.00       644352.15
#Sta/Elev= 30
  4671.1  819.90  4685.9  817.06  4699.0  815.04  4707.8  813.98  4734.0  808.36
  4762.3  803.46  4813.6  797.97  4845.3  795.96  4849.6  795.82  4856.3  796.72
  4862.9  796.80  4875.4  797.57  4887.1  797.31  4904.8  794.10  4919.3  793.18
  4951.6  790.01  4962.6  788.00  4971.9  782.84  4985.7  780.98  4988.8  777.98
  5012.2  777.98  5014.5  780.98  5015.8  788.82  5019.4  789.89  5030.6  790.93
  5052.3  791.25  5095.8  802.55  5111.5  807.03  5120.4  808.68  5130.2  811.27
#Mann=3,-1,0
  4671.1    0.15       0  4985.7    0.45       0  5014.5    0.15       0
Bank Sta=4985.7,5014.5
XS Rating Curve= 0
Exp/Cntr=0.3,0.1

Type RM Length L Ch R = 1,22515,515,515,515
BEGIN DESCRIPTION:
Howards Creek 45.0
END DESCRIPTION:
XS GIS Cut Line= 3
      1301379.67       644995.30      1301395.88       644735.88
      1301468.84       644630.49
#Sta/Elev= 30
  4816.6  820.87  4834.9  818.25  4863.3  813.26  4871.9  811.96  4892.5  807.39
  4896.1  806.30  4914.2  802.05  4918.1  800.62  4938.2  794.38  4947.2  791.87
  4960.3  789.87  4975.5  788.37  4978.3  788.49  4985.6  779.32  4987.1  776.32
  5012.9  776.32  5014.4  779.32  5025.0  784.91  5029.7  785.74  5065.4  790.24
  5076.5  790.82  5088.8  790.48  5106.1  790.56  5119.3  791.61  5150.3  795.64
  5158.7  796.43  5178.4  798.75  5191.4  800.83  5200.4  801.52  5204.7  802.45
#Mann=3,-1,0
  4816.6    0.12       0  4985.6    0.45       0  5014.4    0.15       0
Bank Sta=4985.6,5014.4
XS Rating Curve= 0
Exp/Cntr=0.3,0.1

Type RM Length L Ch R = 1,22000,228,228,228
BEGIN DESCRIPTION:
Howards Creek 44.0
END DESCRIPTION:
XS GIS Cut Line= 3
      1301809.33       644968.28      1301873.19       644773.78
      1301925.00       644675.00
#Sta/Elev= 26
  4795.3  815.16  4800.3  814.18  4813.2  812.42  4858.5  804.58  4867.0  802.83
  4895.3  796.84  4904.0  795.26  4927.5  788.89  4931.7  788.17  4940.3  787.08
  4949.0  787.11  4952.6  787.03  4955.2  787.13  4968.9  788.58  4971.8  788.46
  4980.3  784.95  4985.6  777.06  4987.1  774.06  5012.9  774.06  5014.4  777.06
  5034.4  788.81  5036.7  790.34  5038.9  790.62  5073.9  801.35  5100.7  810.76
  5111.5  813.19
#Mann=3,-1,0
  4795.3    0.12       0  4985.6    0.05       0  5014.4    0.15       0
Bank Sta=4985.6,5014.4
XS Rating Curve= 0
Exp/Cntr=0.3,0.1

Type RM Length L Ch R = 1,21772,151,151,151
BEGIN DESCRIPTION:
Howards Creek 43.5
END DESCRIPTION:
XS GIS Cut Line= 2
      1302012.01       645146.63      1302117.40       644676.43
#Sta/Elev= 30
  4728.9  820.42  4741.5  818.33  4804.2  810.51  4819.0  807.98  4832.2  806.64
  4844.0  804.56  4847.7  803.22  4879.9  799.20  4911.1  793.57  4916.3  792.03
  4924.4  790.42  4967.4  786.59  4979.9  785.02  4984.9  785.22  4985.6  776.96
  4987.1  773.96  5012.9  773.96  5014.4  776.96  5025.7  782.25  5041.6  784.21
  5055.0  787.76  5069.7  788.01  5082.4  790.13  5093.6  793.92  5114.5  800.01
  5147.9  807.80  5163.5  811.93  5177.7  814.50  5205.8  820.73  5210.7  821.64
#Mann=3,-1,0
  4728.9    0.12       0  4985.6    0.06       0  5014.4    0.15       0
Bank Sta=4985.6,5014.4
XS Rating Curve= 0
Exp/Cntr=0.3,0.1

Type RM Length L Ch R = 1,21621,121,121,121
BEGIN DESCRIPTION:
Howards Creek 43.2
END DESCRIPTION:
XS GIS Cut Line= 4
      1302119.78       645178.12      1302218.05       644992.51
      1302221.69       644839.65      1302156.17       644694.07
#Sta/Elev= 30
  4679.0  809.30  4711.3  802.10  4727.8  798.92  4734.2  798.09  4776.7  789.72
  4796.7  787.37  4813.4  786.49  4854.3  786.80  4931.0  785.62  4938.9  786.95
  4941.6  787.72  4947.9  787.62  4949.0  787.92  4962.6  788.63  4975.9  784.73
  4982.2  779.51  4983.4  779.22  4985.6  776.96  4987.1  773.96  5012.9  773.96
  5014.4  776.96  5018.9  778.21  5081.8  792.71  5101.6  793.51  5119.5  796.07
  5132.8  798.50  5151.5  803.01  5159.3  805.38  5174.4  808.40  5201.5  814.82
#Mann=3,-1,0
  4679.0    0.12       0  4985.6    0.05       0  5014.4    0.15       0
Bank Sta=4985.6,5014.4
XS Rating Curve= 0
Exp/Cntr=0.3,0.1