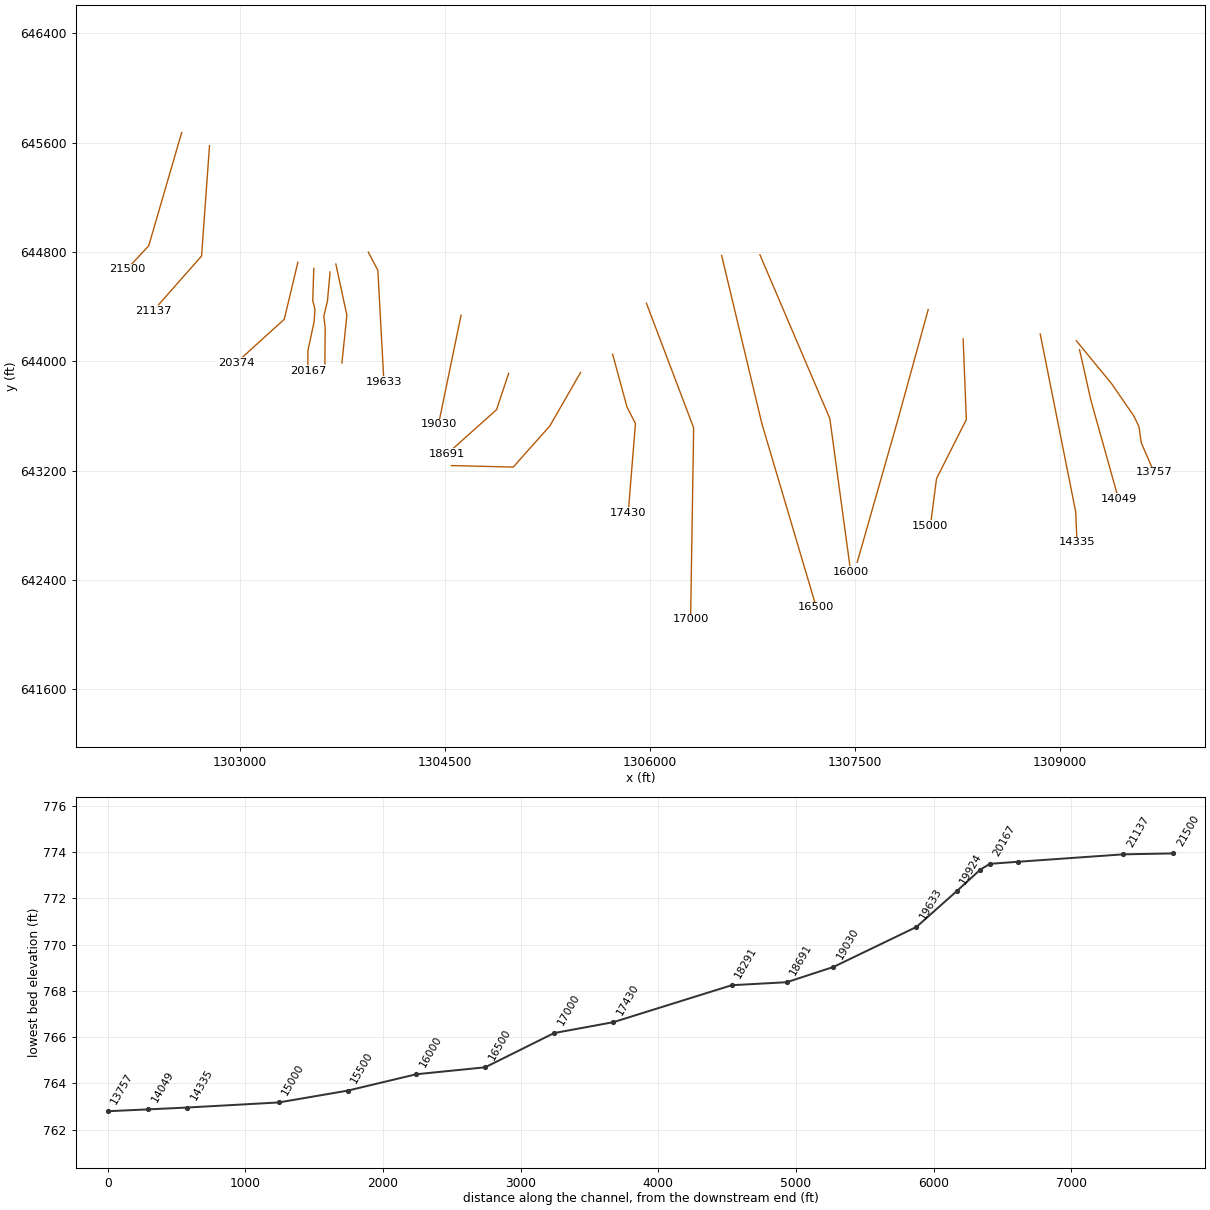
HEC-RAS study Howards Creek.prj: Howards Creek Limited Detail Study

--- Howards Creek.g01 (geometry) --- (continued)

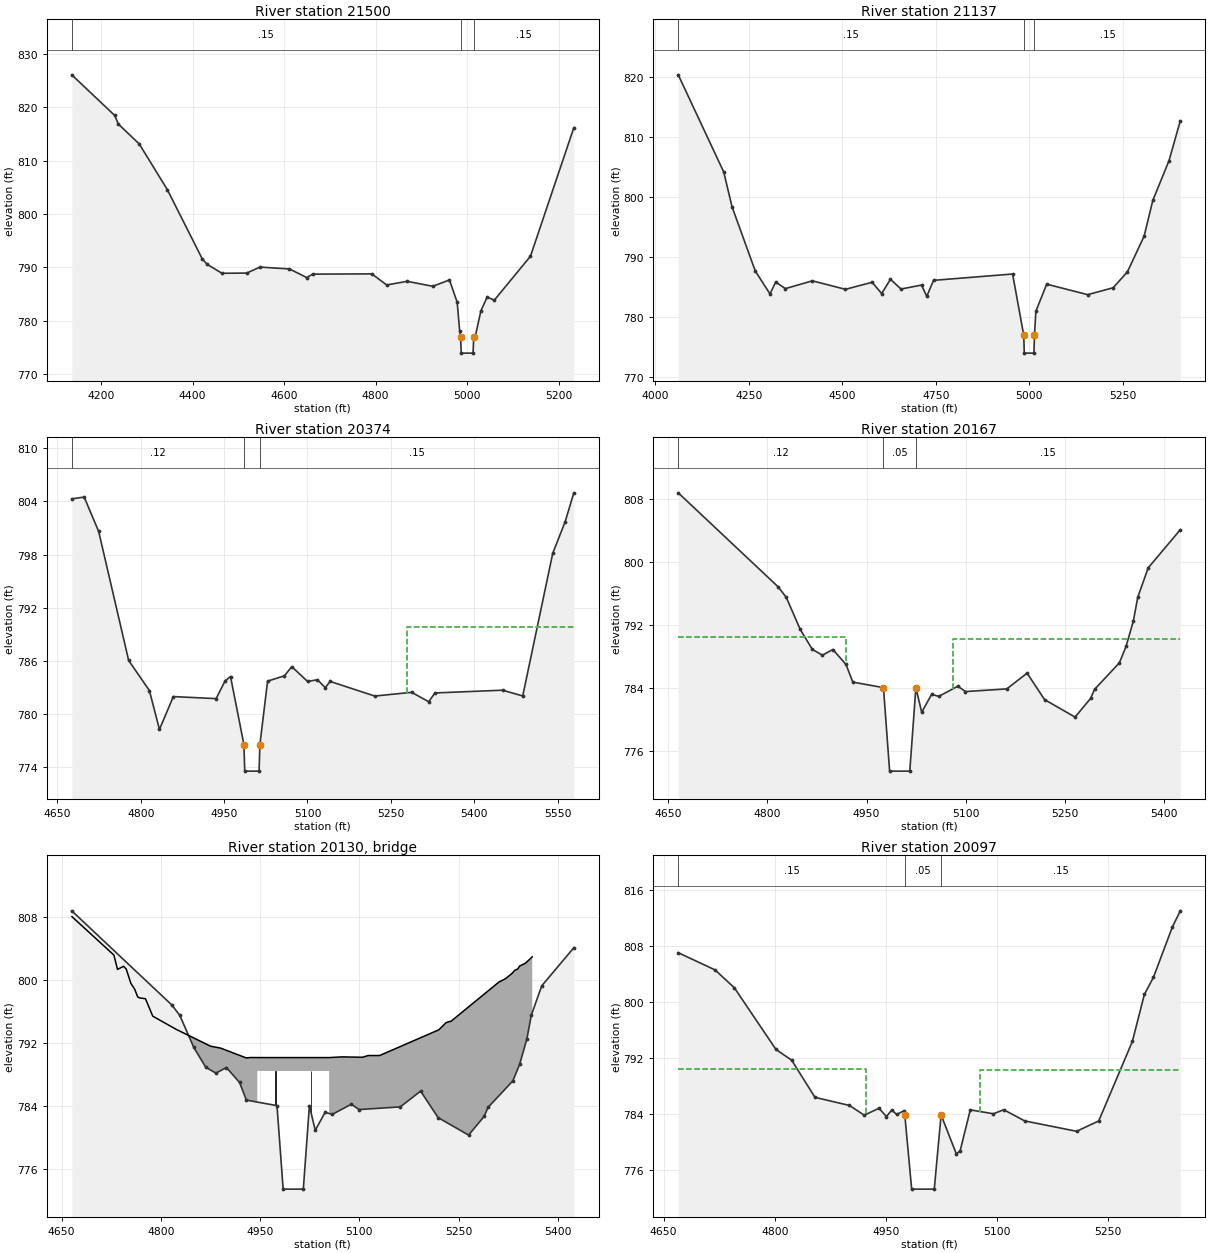
Type RM Length L Ch R = 1,21500,363,363,363
BEGIN DESCRIPTION:
Howards Creek 43.0
END DESCRIPTION:
XS GIS Cut Line= 3
      1302575.00       645675.00      1302333.78       644845.60
      1302175.00       644675.00
#Sta/Elev= 30
  4136.2  826.09  4230.1  818.47  4237.8  816.88  4283.6  813.14  4345.0  804.58
  4420.9  791.67  4431.7  790.60  4464.3  788.91  4518.6  788.95  4547.3  790.07
  4611.8  789.72  4649.8  788.10  4662.3  788.75  4791.7  788.80  4824.2  786.72
  4868.8  787.40  4924.9  786.47  4961.3  787.66  4978.2  783.50  4983.6  778.15
  4985.6  776.95  4987.1  773.95  5012.9  773.95  5014.4  776.95  5017.4  776.95
  5030.0  781.87  5043.7  784.45  5059.3  783.87  5138.3  792.10  5233.1  816.19
#Mann=3,-1,0
  4136.2    0.15       0  4985.6    0.06       0  5014.4    0.15       0
Bank Sta=4985.6,5014.4
XS Rating Curve= 0
Exp/Cntr=0.3,0.1

Type RM Length L Ch R = 1,21137,763,763,763
BEGIN DESCRIPTION:
Howards Creek 42.0
END DESCRIPTION:
XS GIS Cut Line= 3
      1302778.52       645578.46      1302720.29       644770.50
      1302367.26       644370.16
#Sta/Elev= 30
  4060.9  820.41  4182.7  804.17  4205.1  798.32  4267.1  787.63  4306.5  783.80
  4321.7  785.78  4347.8  784.69  4419.8  785.99  4508.5  784.57  4579.8  785.75
  4605.4  783.86  4628.9  786.25  4657.1  784.62  4712.1  785.28  4726.0  783.39
  4744.2  786.07  4955.8  787.13  4985.6  776.91  4987.1  773.91  5012.9  773.91
  5014.4  776.91  5018.1  780.91  5047.1  785.43  5156.9  783.68  5224.9  784.83
  5263.1  787.49  5307.8  793.45  5331.1  799.43  5374.5  806.08  5404.7  812.73
#Mann=3,-1,0
  4060.9    0.15       0  4985.6    0.05       0  5014.4    0.15       0
Bank Sta=4985.6,5014.4
XS Rating Curve= 0
Exp/Cntr=0.3,0.1

Type RM Length L Ch R = 1,20374,207,207,207
BEGIN DESCRIPTION:
Howards Creek 41.0
END DESCRIPTION:
XS GIS Cut Line= 3
      1303425.00       644725.00      1303325.32       644307.57
      1302974.02       643988.69
#Sta/Elev= 30
  4675.8  804.27  4698.1  804.47  4724.2  800.60  4778.2  786.06  4815.5  782.67
  4833.6  778.29  4858.6  781.99  4935.6  781.76  4951.6  783.74  4961.5  784.25
  4985.6  776.59  4987.1  773.59  5012.9  773.59  5014.4  776.59  5028.2  783.73
  5058.5  784.33  5071.7  785.36  5100.3  783.69  5117.9  783.89  5132.1  782.99
  5140.7  783.70  5221.1  782.05  5287.5  782.47  5318.2  781.41  5329.4  782.40
  5451.0  782.71  5487.4  782.06  5541.4  798.13  5563.8  801.70  5579.4  804.95
#Mann=3,-1,0
  4675.8    0.12       0  4985.6    0.05       0  5014.4    0.15       0
#XS Ineff=2,0
       0                 5280.00    0.00  789.80
Bank Sta=4985.6,5014.4
XS Rating Curve= 0
Exp/Cntr=0.5,0.3

Type RM Length L Ch R = 1,20167,70,70,70
BEGIN DESCRIPTION:
Alf Hoover Road u/s HC
END DESCRIPTION:
XS GIS Cut Line= 6
      1303541.51       644680.48      1303533.81       644443.50
      1303550.20       644380.28      1303543.18       644287.20
      1303498.27       644077.87      1303498.27       643929.24
#Sta/Elev= 30
  4665.3  808.83  4816.4  796.89  4828.6  795.56  4849.7  791.49  4868.0  788.95
  4883.3  788.22  4899.0  788.94  4918.9  787.04  4929.2  784.80  4975.5  784.10
  4984.8  773.50  5015.3  773.50  5024.5  784.10  5033.3  780.97  5048.3  783.25
  5059.1  782.99  5087.9  784.28  5099.5  783.60  5161.9  783.94  5192.6  785.94
  5219.0  782.58  5265.1  780.36  5288.6  782.73  5294.5  783.87  5332.1  787.25
  5342.2  789.33  5353.2  792.55  5359.9  795.58  5375.7  799.31  5424.2  804.15
#Mann=3,-1,0
  4665.3    0.12       0  4975.5    0.05       0  5024.5    0.15       0
#XS Ineff=2,0
    0.00 4918.80  790.49 5081.30    0.00  790.28
Bank Sta=4975.5,5024.5
XS Rating Curve= 0
Exp/Cntr=0.5,0.3

Type RM Length L Ch R =3,20130,,,
BEGIN DESCRIPTION:
Alf Hoover Road TOR HC
Structure ID: LDS_HC_04
Approximate Survey Structure
END DESCRIPTION:
Bridge Culvert--1,0,-1,-1,0
Deck Dist Width WeirC Skew NumUp NumDn MinLoCord MaxHiCord MaxSubmerge Is_Ogee
27,20,3,,38,38,,,,0,1,1,,,
  4665.6  4729.0  4734.4  4743.6  4747.7  4754.6  4760.3  4764.9  4768.0  4776.7
  4787.6  4788.1  4823.2  4875.0  4890.4  4928.9  4936.2  4945.8  4945.8  5054.3
  5054.3  5074.1  5104.7  5113.3  5130.6  5220.0  5227.3  5230.7  5235.7  5238.1
  5310.8  5320.8  5331.3  5334.8  5339.4  5342.2  5350.9  5361.3
  808.09  803.21  801.39  801.79  801.42  799.63  798.89  797.91  797.77  797.67
  795.48  795.44  793.78  791.65  791.40  790.16  790.21  790.20  790.20  790.20
  790.20  790.29  790.24  790.46  790.46  793.72  794.32  794.61  794.78  794.78
  799.78  800.21  800.93  801.28  801.45  801.82  802.17  802.99
  753.50  753.50  753.50  753.50  753.50  753.50  753.50  753.50  753.50  753.50
  753.50  753.50  753.50  753.50  753.50  753.50  753.50  753.50  788.50  788.50
  753.50  753.50  753.50  753.50  753.50  753.50  753.50  753.50  753.50  753.50
  753.50  753.50  753.50  753.50  753.50  753.50  753.50  753.50
  4665.6  4729.0  4734.4  4743.6  4747.7  4754.6  4760.3  4764.9  4768.0  4776.7
  4787.6  4788.1  4823.2  4875.0  4890.4  4928.9  4936.2  4945.8  4945.8  5054.3
  5054.3  5074.1  5104.7  5113.3  5130.6  5220.0  5227.3  5230.7  5235.7  5238.1
  5310.8  5320.8  5331.3  5334.8  5339.4  5342.2  5350.9  5361.3
  808.09  803.21  801.39  801.79  801.42  799.63  798.89  797.91  797.77  797.67
  795.48  795.44  793.78  791.65  791.40  790.16  790.21  790.20  790.20  790.20
  790.20  790.29  790.24  790.46  790.46  793.72  794.32  794.61  794.78  794.78
  799.78  800.21  800.93  801.28  801.45  801.82  802.17  802.99
  753.50  753.50  753.50  753.50  753.50  753.50  753.50  753.50  753.50  753.50
  753.50  753.50  753.50  753.50  753.50  753.50  753.50  753.50  788.50  788.50
  753.50  753.50  753.50  753.50  753.50  753.50  753.50  753.50  753.50  753.50
  753.50  753.50  753.50  753.50  753.50  753.50  753.50  753.50
Pier Skew, UpSta & Num, DnSta & Num=,4972.9,2,4972.9,2,0,0,0,0,0
       1       1
  784.26  788.50
       1       1
  784.37  788.50
Pier Skew, UpSta & Num, DnSta & Num=,5027.1,2,5027.1,2,0,0,0,0,0
       1       1
  783.18  788.50
       1       1
  783.15  788.50
BR Coef=1,1,0,1.25,0,,,0.8,0,2,0,
WSPro=,,,, 1 ,,,, 0 ,,,, 0 ,,,,-1 ,-1 ,-1 , 0 , 0 , 0 , 0 , 0
BC Design=,,0,,0,,,,,,

Type RM Length L Ch R = 1,20097,173,173,173
BEGIN DESCRIPTION:
Alf Hoover Road d/s HC
END DESCRIPTION:
XS GIS Cut Line= 5
      1303660.41       644653.46      1303641.49       644442.68
      1303614.60       644328.18      1303624.73       644245.64
      1303622.58       643980.59
#Sta/Elev= 30
  4669.8  807.02  4719.5  804.56  4745.5  802.01  4801.7  793.20  4822.9  791.66
  4854.3  786.36  4900.9  785.20  4920.8  783.81  4940.7  784.80  4950.8  783.61
  4957.9  784.56  4964.6  783.91  4973.8  784.42  4975.5  783.85  4984.8  773.25
  5015.3  773.25  5024.5  783.85  5045.1  778.27  5050.2  778.73  5063.9  784.57
  5095.2  784.01  5109.0  784.59  5137.4  782.99  5207.4  781.51  5237.2  782.99
  5282.6  794.34  5298.8  801.06  5311.1  803.51  5336.6  810.70  5347.3  813.00
#Mann=3,-1,0
  4669.8    0.15       0  4975.5    0.05       0  5024.5    0.15       0
#XS Ineff=2,0
    0.00 4922.80  790.36 5077.30    0.00  790.28
Bank Sta=4975.5,5024.5
XS Rating Curve= 0
Exp/Cntr=0.5,0.3

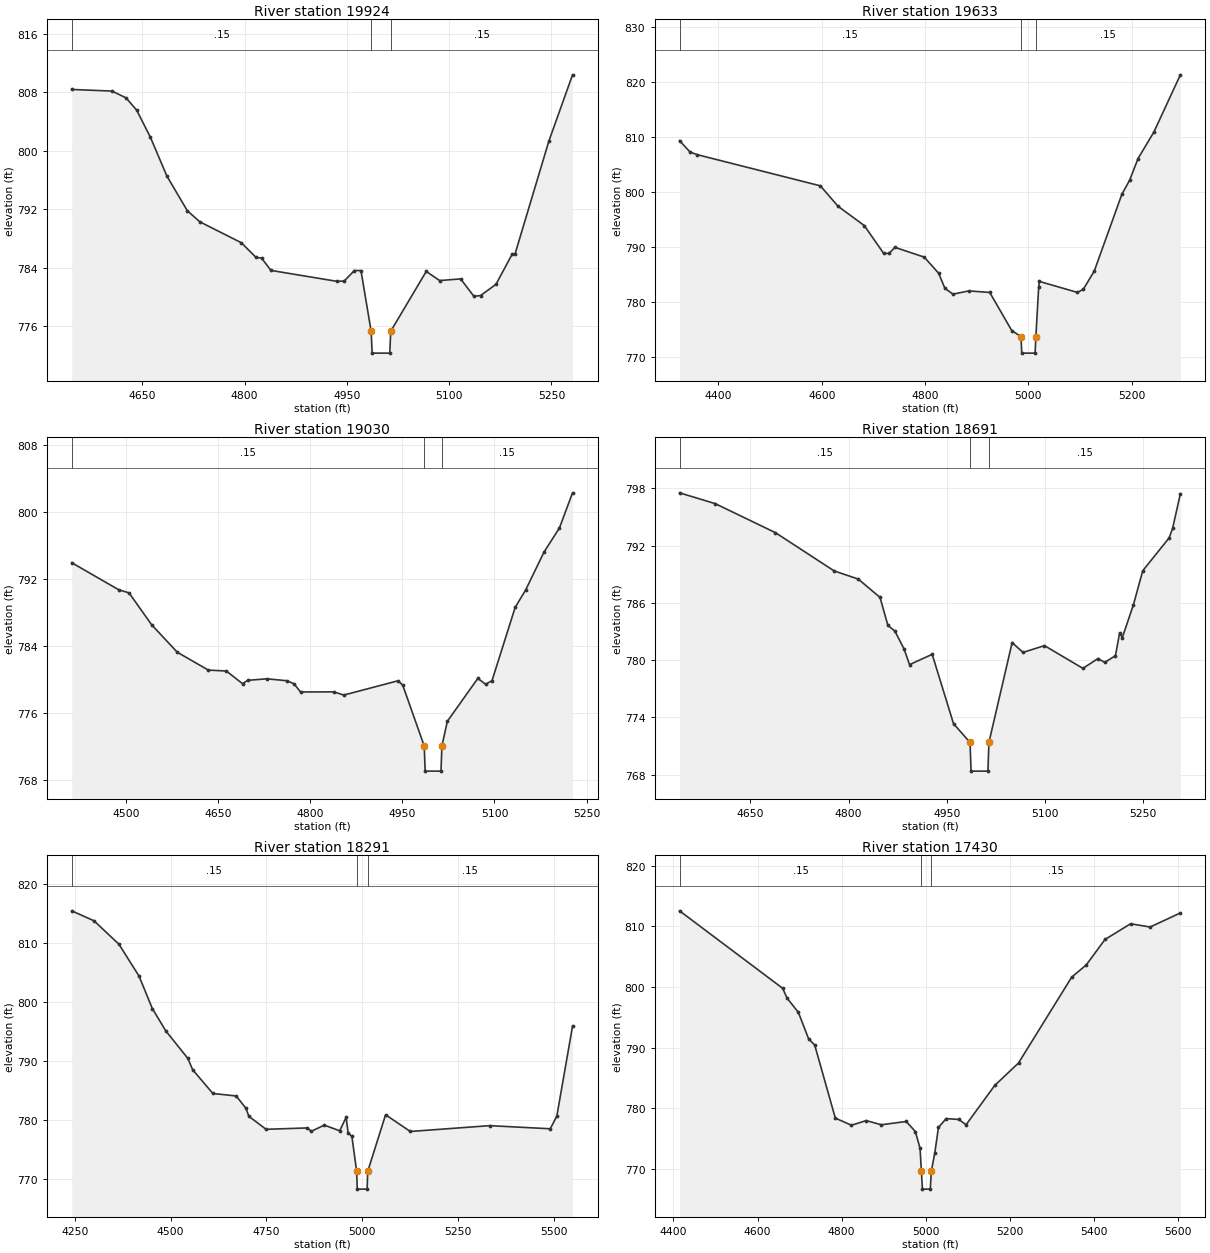
Type RM Length L Ch R = 1,19924,291,291,291
BEGIN DESCRIPTION:
Howards Creek 40.0
END DESCRIPTION:
XS GIS Cut Line= 3
      1303702.77       644711.95      1303783.49       644337.01
      1303747.04       643988.10
#Sta/Elev= 30
  4546.6  808.36  4605.6  808.14  4626.3  807.21  4641.9  805.52  4661.9  801.84
  4686.1  796.53  4716.1  791.78  4734.5  790.26  4795.2  787.41  4816.8  785.40
  4824.9  785.31  4838.7  783.62  4935.8  782.12  4946.1  782.17  4961.1  783.60
  4970.7  783.60  4985.6  775.31  4987.1  772.31  5012.9  772.31  5014.4  775.31
  5066.4  783.48  5086.1  782.23  5116.8  782.46  5136.3  780.08  5146.0  780.18
  5168.6  781.71  5192.5  785.86  5196.7  785.90  5246.2  801.30  5280.9  810.36
#Mann=3,-1,0
  4546.6    0.15       0  4985.6    0.05       0  5014.4    0.15       0
Bank Sta=4985.6,5014.4
XS Rating Curve= 0
Exp/Cntr=0.3,0.1

Type RM Length L Ch R = 1,19633,603,603,603
BEGIN DESCRIPTION:
Howards Creek 39.0
END DESCRIPTION:
XS GIS Cut Line= 3
      1303940.28       644799.33      1304010.00       644666.22
      1304054.37       643848.58
#Sta/Elev= 30
  4324.9  809.36  4345.1  807.30  4358.8  806.82  4597.4  801.15  4631.6  797.44
  4682.3  793.94  4720.0  788.87  4730.4  788.89  4741.7  789.98  4798.3  788.21
  4826.2  785.29  4838.4  782.53  4854.0  781.48  4884.8  782.07  4925.1  781.79
  4967.8  774.86  4985.6  773.77  4987.1  770.77  5012.9  770.77  5014.4  773.77
  5019.8  782.71  5021.2  783.79  5094.6  781.80  5106.0  782.34  5127.3  785.65
  5180.8  799.62  5195.9  802.18  5212.1  806.11  5242.7  810.91  5294.0  821.31
#Mann=3,-1,0
  4324.9    0.15       0  4985.6    0.05       0  5014.4    0.15       0
Bank Sta=4985.6,5014.4
XS Rating Curve= 0
Exp/Cntr=0.3,0.1

Type RM Length L Ch R = 1,19030,339,339,339
BEGIN DESCRIPTION:
Howards Creek 38.0
END DESCRIPTION:
XS GIS Cut Line= 2
      1304618.48       644336.63      1304453.69       643538.00
#Sta/Elev= 30
  4411.6  793.92  4488.1  790.69  4504.9  790.32  4542.0  786.49  4583.4  783.24
  4634.0  781.10  4663.4  780.99  4689.7  779.48  4698.5  779.88  4729.3  780.06
  4762.2  779.83  4773.6  779.46  4784.2  778.49  4838.5  778.50  4854.6  778.12
  4943.2  779.83  4950.7  779.28  4985.6  772.04  4987.1  769.04  5012.9  769.04
  5014.4  772.04  5023.2  774.98  5072.9  780.11  5085.5  779.41  5096.0  779.84
  5133.7  788.59  5150.8  790.67  5180.6  795.18  5205.8  798.07  5227.1  802.26
#Mann=3,-1,0
  4411.6    0.15       0  4985.6    0.05       0  5014.4    0.15       0
Bank Sta=4985.6,5014.4
XS Rating Curve= 0
Exp/Cntr=0.3,0.1

Type RM Length L Ch R = 1,18691,400,400,400
BEGIN DESCRIPTION:
Howards Creek 37.0
END DESCRIPTION:
XS GIS Cut Line= 3
      1304967.09       643911.96      1304878.35       643645.75
      1304517.07       643322.50
#Sta/Elev= 30
  4541.6  797.52  4596.1  796.39  4688.1  793.35  4778.0  789.34  4814.7  788.49
  4848.0  786.57  4860.0  783.64  4870.7  783.04  4884.6  781.19  4893.1  779.53
  4927.7  780.61  4960.3  773.35  4985.6  771.38  4987.1  768.38  5012.9  768.38
  5014.4  771.38  5049.9  781.84  5066.5  780.81  5099.3  781.52  5158.1  779.14
  5181.1  780.17  5191.4  779.76  5207.8  780.47  5214.2  782.87  5218.2  782.35
  5235.3  785.81  5249.5  789.36  5289.8  792.80  5295.1  793.79  5307.0  797.43
#Mann=3,-1,0
  4541.6    0.15       0  4985.6    0.05       0  5014.4    0.15       0
Bank Sta=4985.6,5014.4
XS Rating Curve= 0
Exp/Cntr=0.3,0.1

Type RM Length L Ch R = 1,18291,861,861,861
BEGIN DESCRIPTION:
Howards Creek 36.0
END DESCRIPTION:
XS GIS Cut Line= 4
      1305493.17       643918.30      1305268.71       643527.32
      1305000.46       643225.54      1304547.79       643236.72
#Sta/Elev= 30
  4241.7  815.51  4299.9  813.82  4365.1  809.83  4417.4  804.43  4452.1  798.92
  4487.4  795.12  4545.0  790.44  4557.2  788.55  4610.2  784.49  4671.1  784.07
  4696.6  781.97  4704.1  780.62  4749.0  778.41  4856.3  778.64  4867.5  778.08
  4901.0  779.12  4941.2  778.16  4958.1  780.44  4963.2  777.84  4973.1  777.20
  4985.6  771.25  4987.1  768.25  5012.9  768.25  5014.4  771.25  5061.1  780.88
  5125.6  778.04  5332.7  779.03  5490.8  778.50  5508.0  780.61  5549.1  795.93
#Mann=3,-1,0
  4241.7    0.15       0  4985.6    0.05       0  5014.4    0.15       0
Bank Sta=4985.6,5014.4
XS Rating Curve= 0
Exp/Cntr=0.3,0.1

Type RM Length L Ch R = 1,17430,430,430,430
BEGIN DESCRIPTION:
Howards Creek 35.0
END DESCRIPTION:
XS GIS Cut Line= 4
      1305727.69       644051.41      1305833.14       643664.24
      1305894.62       643544.09      1305841.78       642891.50
#Sta/Elev= 30
  4414.5  812.57  4659.8  799.78  4670.0  798.19  4697.1  795.81  4721.5  791.43
  4735.9  790.43  4784.9  778.37  4823.3  777.19  4858.3  777.96  4894.4  777.27
  4953.5  777.81  4975.3  776.15  4986.4  773.38  4989.5  769.65  4992.1  766.65
  5010.7  766.65  5013.3  769.65  5021.5  772.62  5030.1  776.82  5048.5  778.29
  5078.9  778.14  5095.8  777.27  5164.0  783.76  5220.5  787.46  5347.0  801.63
  5381.7  803.65  5426.1  807.84  5486.9  810.43  5533.6  809.90  5605.4  812.22
#Mann=3,-1,0
  4414.5    0.15       0  4989.5    0.06       0  5013.3    0.15       0
Bank Sta=4989.5,5013.3
XS Rating Curve= 0
Exp/Cntr=0.3,0.1

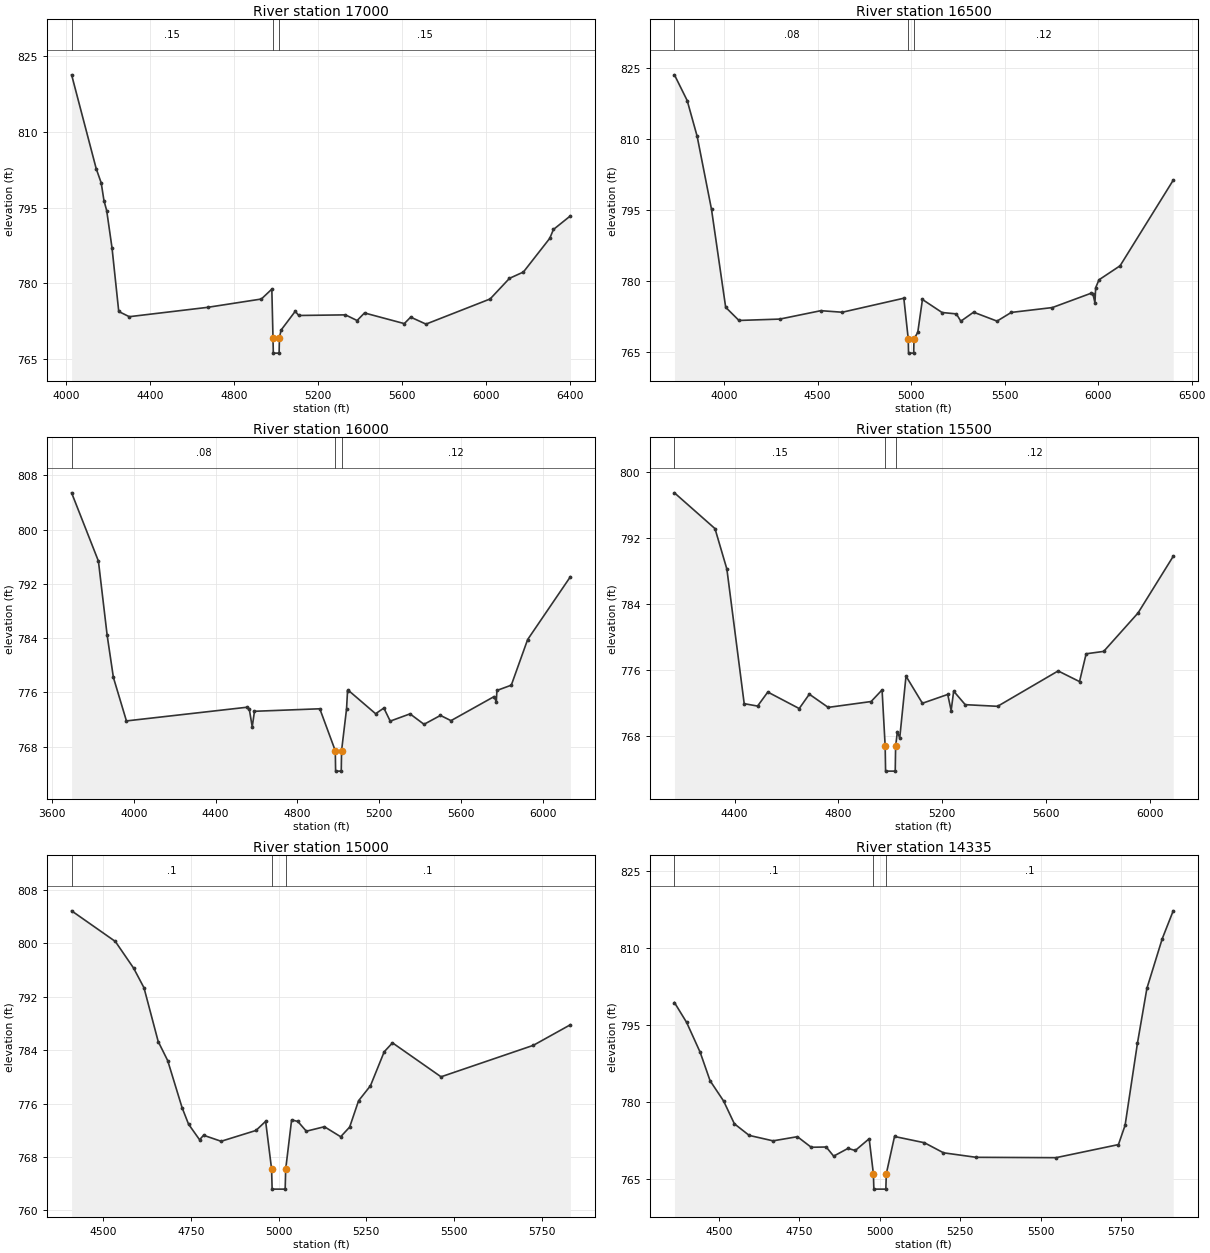
Type RM Length L Ch R = 1,17000,500,500,500
BEGIN DESCRIPTION:
Howards Creek 34.0
END DESCRIPTION:
XS GIS Cut Line= 3
      1305975.00       644425.00      1306320.31       643513.29
      1306298.14       642111.88
#Sta/Elev= 30
  4025.1  821.32  4142.3  802.73  4166.2  799.90  4179.2  796.42  4192.3  794.41
  4217.7  787.02  4249.7  774.43  4299.9  773.40  4672.9  775.25  4929.2  776.90
  4979.1  778.86  4984.7  769.18  4986.2  766.18  5013.8  766.18  5015.3  769.18
  5022.9  770.73  5090.7  774.47  5107.3  773.64  5330.0  773.76  5385.4  772.64
  5420.7  774.14  5610.2  772.03  5640.6  773.31  5713.6  771.93  6019.2  776.91
  6111.5  781.00  6177.8  782.25  6303.4  788.93  6320.9  790.68  6401.6  793.37
#Mann=3,-1,0
  4025.1    0.15       0  4984.7    0.05       0  5015.3    0.15       0
Bank Sta=4984.7,5015.3
XS Rating Curve= 0
Exp/Cntr=0.3,0.1

Type RM Length L Ch R = 1,16500,500,500,500
BEGIN DESCRIPTION:
Howards Creek 33.0
END DESCRIPTION:
XS GIS Cut Line= 3
      1306525.00       644775.00      1306819.28       643544.31
      1307217.19       642200.62
#Sta/Elev= 30
  3734.6  823.64  3802.7  818.20  3855.8  810.65  3932.8  795.14  4008.5  774.41
  4079.6  771.62  4298.0  771.91  4517.4  773.69  4632.0  773.36  4961.1  776.33
  4984.7  767.70  4986.2  764.70  5013.8  764.70  5015.3  767.70  5035.6  769.10
  5060.6  776.06  5165.6  773.30  5241.9  773.01  5265.8  771.46  5334.0  773.37
  5459.4  771.48  5535.5  773.32  5755.1  774.35  5961.3  777.37  5971.8  777.28
  5982.9  775.36  5986.7  778.56  6004.6  780.23  6117.4  783.20  6401.4  801.32
#Mann=3,-1,0
  3734.6    0.08       0  4984.7    0.05       0  5015.3    0.12       0
Bank Sta=4984.7,5015.3
XS Rating Curve= 0
Exp/Cntr=0.3,0.1

Type RM Length L Ch R = 1,16000,500,500,500
BEGIN DESCRIPTION:
Howards Creek 32.0
END DESCRIPTION:
XS GIS Cut Line= 3
      1306805.20       644779.68      1307316.75       643580.44
      1307469.46       642457.32
#Sta/Elev= 30
  3696.2  805.42  3827.2  795.36  3870.0  784.40  3900.4  778.21  3964.1  771.80
  4551.1  773.81  4564.7  773.49  4578.8  770.93  4589.8  773.22  4909.0  773.59
  4984.7  767.40  4986.2  764.40  5013.8  764.40  5015.3  767.40  5039.7  773.57
  5044.5  776.24  5048.5  776.31  5181.7  772.86  5222.1  773.70  5253.0  771.77
  5349.9  772.84  5418.3  771.30  5498.6  772.61  5550.1  771.84  5760.8  775.39
  5771.4  774.61  5774.4  776.29  5844.7  777.07  5924.5  783.79  6133.4  793.05
#Mann=3,-1,0
  3696.2    0.08       0  4984.7    0.05       0  5015.3    0.12       0
Bank Sta=4984.7,5015.3
XS Rating Curve= 0
Exp/Cntr=0.3,0.1

Type RM Length L Ch R = 1,15500,500,500,500
BEGIN DESCRIPTION:
Howards Creek 31.0
END DESCRIPTION:
XS GIS Cut Line= 3
      1308036.36       644378.59      1307815.70       643576.52
      1307517.12       642528.82
#Sta/Elev= 30
  4168.1  797.44  4324.3  793.10  4370.1  788.19  4436.8  771.87  4488.4  771.58
  4527.7  773.28  4648.7  771.28  4687.7  773.02  4760.4  771.42  4925.7  772.13
  4967.9  773.54  4979.9  766.69  4981.4  763.69  5018.6  763.69  5020.1  766.69
  5026.9  768.48  5035.9  767.70  5060.1  775.21  5123.3  771.92  5220.8  772.99
  5234.0  771.04  5243.7  773.39  5288.2  771.75  5412.9  771.55  5646.1  775.84
  5728.5  774.55  5754.0  777.92  5821.6  778.21  5953.9  782.87  6089.4  789.74
#Mann=3,-1,0
  4168.1    0.15       0  4979.9    0.05       0  5020.1    0.12       0
Bank Sta=4979.9,5020.1
XS Rating Curve= 0
Exp/Cntr=0.3,0.1

Type RM Length L Ch R = 1,15000,665,665,665
BEGIN DESCRIPTION:
Howards Creek 30.0
END DESCRIPTION:
XS GIS Cut Line= 4
      1308291.92       644163.60      1308315.29       643573.69
      1308097.20       643141.35      1308052.58       642796.55
#Sta/Elev= 30
  4409.6  804.88  4534.3  800.29  4586.6  796.28  4616.0  793.35  4656.5  785.30
  4683.6  782.44  4724.5  775.41  4743.1  772.91  4774.5  770.58  4786.0  771.25
  4836.0  770.35  4935.3  771.97  4962.9  773.34  4979.9  766.18  4981.4  763.18
  5018.6  763.18  5020.1  766.18  5037.0  773.56  5054.7  773.32  5079.0  771.86
  5130.5  772.53  5176.9  771.03  5202.5  772.48  5227.9  776.42  5261.8  778.67
  5301.0  783.76  5324.6  785.10  5463.1  780.01  5726.4  784.73  5831.9  787.81
#Mann=3,-1,0
  4409.6     0.1       0  4979.9    0.05       0  5020.1     0.1       0
Bank Sta=4979.9,5020.1
XS Rating Curve= 0
Exp/Cntr=0.3,0.1

Type RM Length L Ch R = 1,14335,286,286,286
BEGIN DESCRIPTION:
Howards Creek 29.0
END DESCRIPTION:
XS GIS Cut Line= 3
      1308855.77       644200.10      1309115.39       642897.96
      1309125.00       642675.00
#Sta/Elev= 30
  4361.3  799.33  4399.2  795.45  4441.3  789.63  4472.1  784.09  4514.2  780.13
  4547.7  775.69  4593.8  773.43  4667.9  772.37  4743.6  773.18  4786.6  771.12
  4833.2  771.17  4856.4  769.39  4901.0  770.90  4923.6  770.49  4966.8  772.78
  4979.9  765.96  4981.4  762.96  5018.6  762.96  5020.1  765.96  5045.6  773.22
  5138.7  772.00  5197.9  770.04  5299.5  769.16  5547.7  769.09  5741.9  771.64
  5762.6  775.41  5801.0  791.41  5830.4  802.09  5878.0  811.75  5912.2  817.20
#Mann=3,-1,0
  4361.3     0.1       0  4979.9    0.05       0  5020.1     0.1       0
Bank Sta=4979.9,5020.1
XS Rating Curve= 0
Exp/Cntr=0.3,0.1

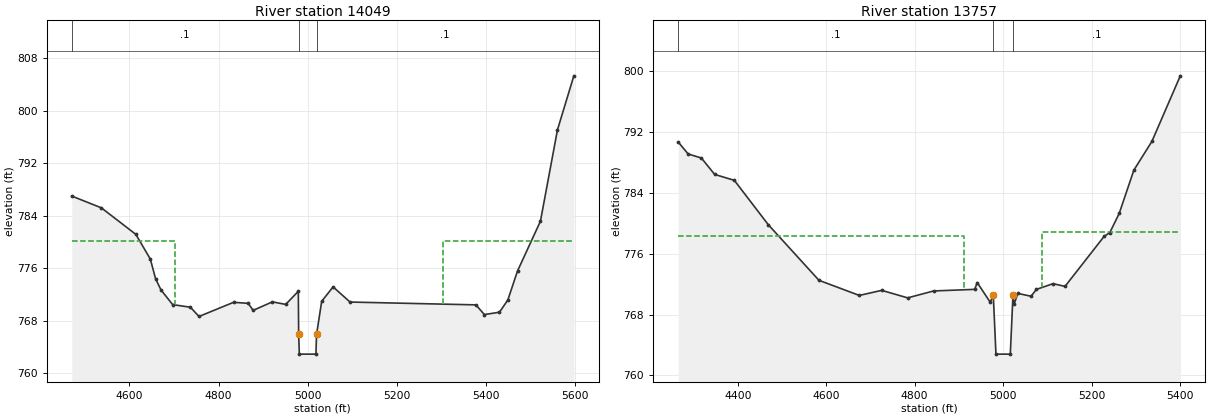
Type RM Length L Ch R = 1,14049,292,292,292
BEGIN DESCRIPTION:
Howards Creek 28.0
END DESCRIPTION:
XS GIS Cut Line= 3
      1309143.46       644085.47      1309226.54       643714.21
      1309427.74       642995.32
#Sta/Elev= 30
  4470.6  786.98  4537.1  785.18  4614.4  781.14  4646.9  777.38  4658.7  774.38
  4670.9  772.66  4697.1  770.43  4736.9  770.03  4756.2  768.62  4833.8  770.78
  4866.7  770.62  4877.7  769.55  4921.0  770.85  4950.8  770.46  4979.1  772.46
  4979.9  765.88  4981.4  762.88  5018.6  762.88  5020.1  765.88  5031.6  770.93
  5057.2  773.13  5095.2  770.82  5377.8  770.39  5396.8  768.91  5430.6  769.27
  5449.4  771.13  5471.2  775.56  5522.6  783.14  5560.9  797.09  5597.6  805.31
#Mann=3,-1,0
  4470.6     0.1       0  4979.9    0.05       0  5020.1     0.1       0
#XS Ineff=2,0
    0.00 4701.40  780.08 5304.10    0.00  780.08
Bank Sta=4979.9,5020.1
XS Rating Curve= 0
Exp/Cntr=0.5,0.3

Type RM Length L Ch R = 1,13757,78,78,78
BEGIN DESCRIPTION:
Daniels Road u/s HC
END DESCRIPTION:
XS GIS Cut Line= 6
      1309120.10       644150.37      1309379.71       643833.64
      1309540.10       643600.39      1309578.07       643522.27
      1309595.20       643402.67      1309688.66       643187.19
#Sta/Elev= 30
  4265.2  790.70  4287.6  789.13  4317.5  788.60  4347.6  786.44  4392.1  785.66
  4468.7  779.84  4583.5  772.51  4674.8  770.52  4725.4  771.19  4784.1  770.20
  4842.7  771.11  4935.8  771.32  4941.4  772.22  4970.8  769.63  4977.8  770.55
  4983.8  762.80  5016.3  762.80  5022.3  770.55  5024.7  769.34  5033.3  770.79
  5063.3  770.41  5075.1  771.31  5113.0  772.07  5140.0  771.71  5228.9  778.32
  5241.2  778.77  5262.6  781.31  5295.8  787.01  5336.5  790.78  5400.8  799.41
#Mann=3,-1,0
  4265.2     0.1       0  4977.8    0.05       0  5022.3     0.1       0
#XS Ineff=2,0
    0.00 4912.30  778.30 5087.80    0.00  778.84
Bank Sta=4977.8,5022.3
XS Rating Curve= 0
Exp/Cntr=0.5,0.3