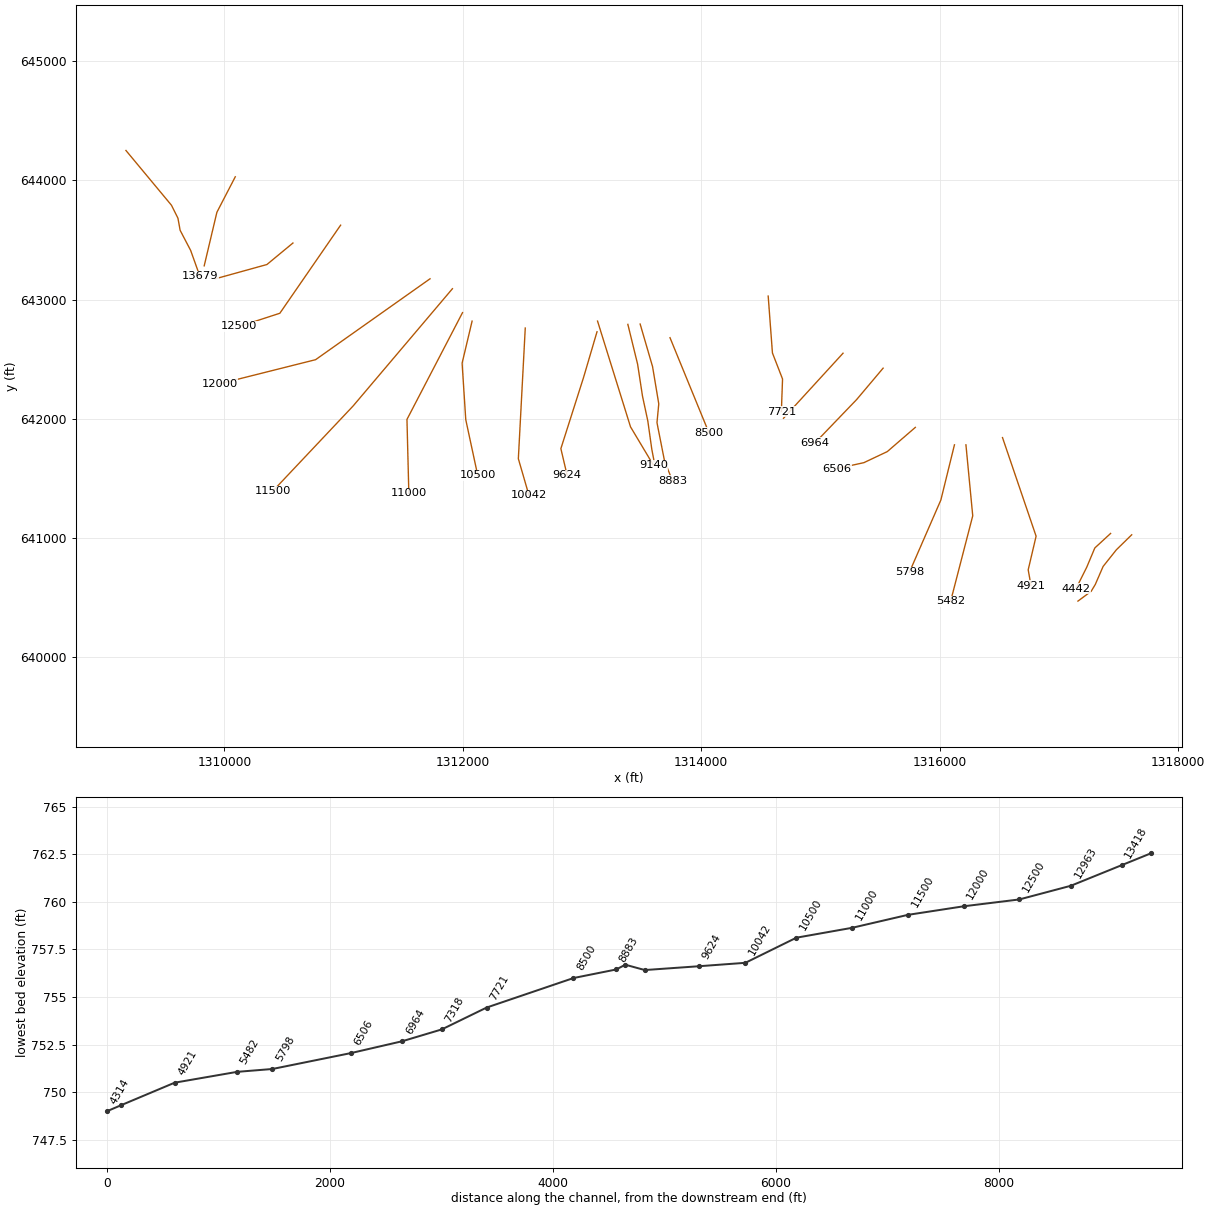
HEC-RAS study Howards Creek.prj: Howards Creek Limited Detail Study

--- Howards Creek.g01 (geometry) --- (continued)

Type RM Length L Ch R =3,13723,,,
BEGIN DESCRIPTION:
Daniels Road TOR HC
Structure ID: LDS_HC_03
Approximate Survey Structure
END DESCRIPTION:
Bridge Culvert--1,0,-1,-1,0
Deck Dist Width WeirC Skew NumUp NumDn MinLoCord MaxHiCord MaxSubmerge Is_Ogee
20,28,3,,30,30,,,,0,1,1,,,
  4230.3  4315.0  4391.3  4465.3  4479.5  4555.4  4570.3  4619.4  4626.1  4630.0
  4632.7  4932.3  4932.3  5067.8  5067.8  5075.9  5076.7  5141.5  5172.8  5179.9
  5192.1  5204.3  5253.3  5260.3  5293.5  5305.4  5352.5  5369.5  5370.4  5389.4
  792.29  786.54  782.52  780.38  780.32  778.82  778.94  778.40  777.93  778.32
  778.30  778.30  778.30  778.30  778.30  778.30  778.63  779.87  781.18  781.29
  782.22  782.61  785.15  785.81  788.02  789.18  792.65  794.12  794.16  795.95
  742.80  742.80  742.80  742.80  742.80  742.80  742.80  742.80  742.80  742.80
  742.80  742.80  776.30  776.30  742.80  742.80  742.80  742.80  742.80  742.80
  742.80  742.80  742.80  742.80  742.80  742.80  742.80  742.80  742.80  742.80
  4230.3  4315.0  4391.3  4465.3  4479.5  4555.4  4570.3  4619.4  4626.1  4630.0
  4632.7  4932.3  4932.3  5067.8  5067.8  5075.9  5076.7  5141.5  5172.8  5179.9
  5192.1  5204.3  5253.3  5260.3  5293.5  5305.4  5352.5  5369.5  5370.4  5389.4
  792.29  786.54  782.52  780.38  780.32  778.82  778.94  778.40  777.93  778.32
  778.30  778.30  778.30  778.30  778.30  778.30  778.63  779.87  781.18  781.29
  782.22  782.61  785.15  785.81  788.02  789.18  792.65  794.12  794.16  795.95
  742.80  742.80  742.80  742.80  742.80  742.80  742.80  742.80  742.80  742.80
  742.80  742.80  776.30  776.30  742.80  742.80  742.80  742.80  742.80  742.80
  742.80  742.80  742.80  742.80  742.80  742.80  742.80  742.80  742.80  742.80
Pier Skew, UpSta & Num, DnSta & Num=,4966.1,2,4966.1,2,0,0,0,0,0
       3       3
  770.07  776.30
       3       3
  771.45  776.30
Pier Skew, UpSta & Num, DnSta & Num=,5033.9,2,5033.9,2,0,0,0,0,0
       3       3
  770.78  776.30
       3       3
  770.67  776.30
Abutment Skew #Up #Dn=,2,2
  4932.3  4942.5
  776.30  772.10
  4932.3  4942.5
  776.30  772.91
Abutment Skew #Up #Dn=,2,2
  5057.5  5067.8
  770.49  776.30
  5057.5  5067.8
  771.88  776.30
BR Coef=1,1,0,1.25,0,,,0.8,0,2,0,
WSPro=,,,, 1 ,,,, 0 ,,,, 0 ,,,,-1 ,-1 ,-1 , 0 , 0 , 0 , 0 , 0
BC Design=,,0,,0,,,,,,

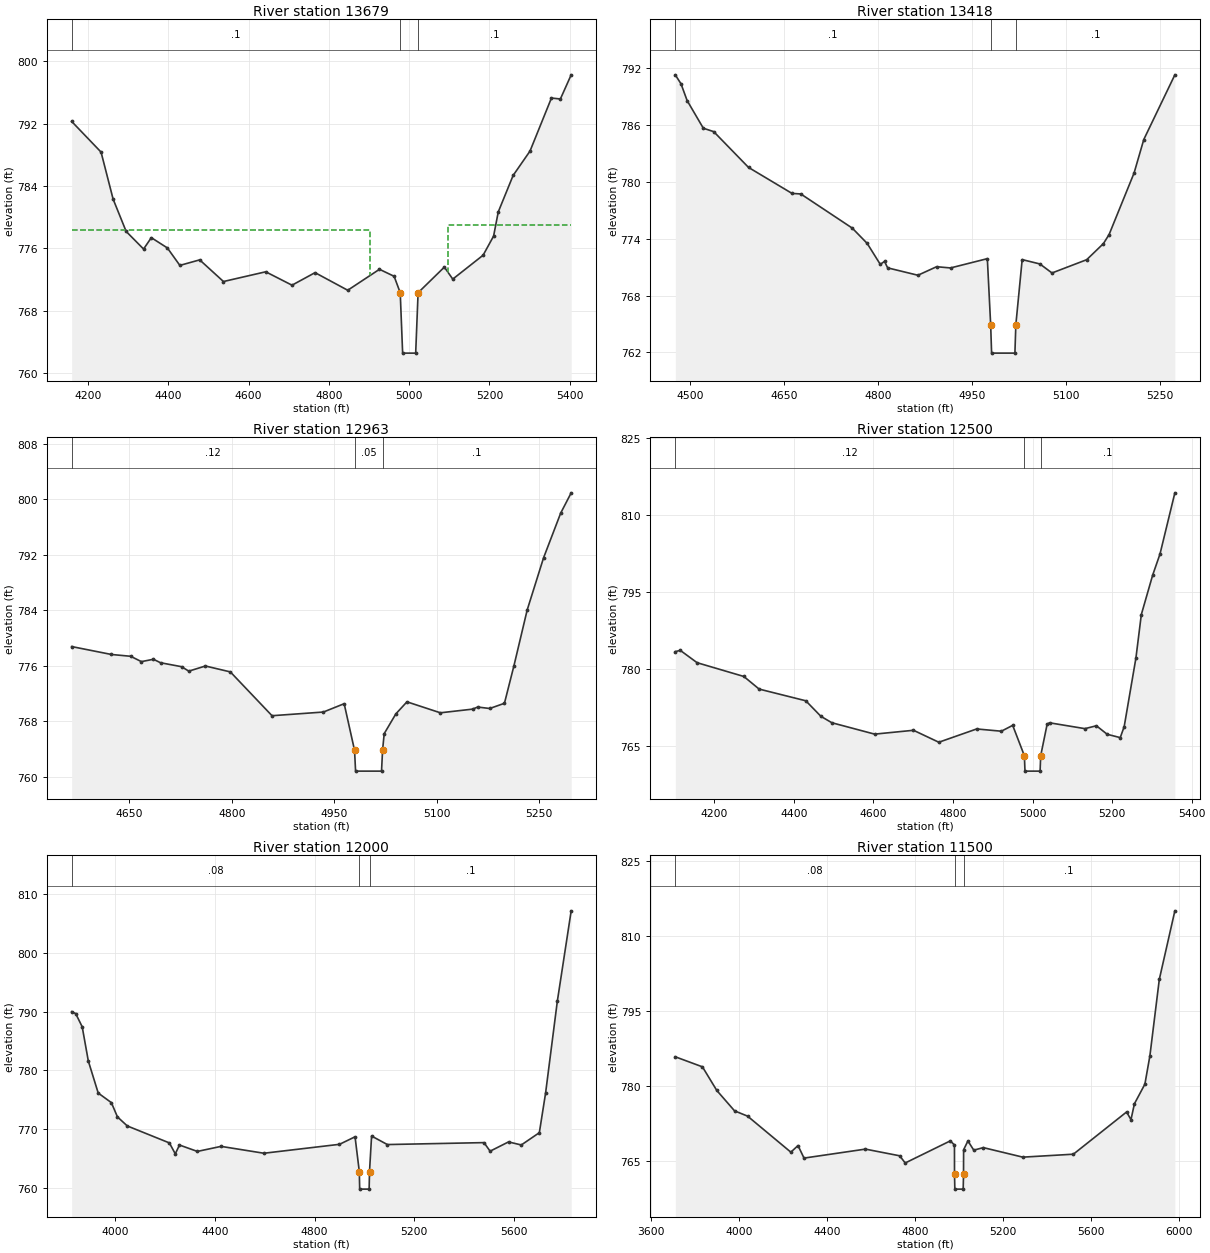
Type RM Length L Ch R = 1,13679,261,261,261
BEGIN DESCRIPTION:
Daniels Road d/s HC
END DESCRIPTION:
XS GIS Cut Line= 6
      1309174.62       644251.62      1309556.25       643792.10
      1309610.77       643683.06      1309628.95       643581.81
      1309717.22       643413.06      1309795.10       643194.98
#Sta/Elev= 30
  4159.2  792.29  4232.5  788.35  4262.5  782.32  4295.0  778.17  4338.4  775.91
  4357.7  777.37  4397.7  776.05  4428.8  773.81  4478.2  774.52  4537.4  771.74
  4642.7  772.99  4708.2  771.27  4765.6  772.88  4847.0  770.62  4926.1  773.31
  4962.6  772.41  4977.8  770.30  4983.8  762.55  5016.3  762.55  5022.3  770.30
  5087.7  773.59  5108.7  772.05  5184.3  775.12  5210.4  777.57  5222.0  780.67
  5259.1  785.36  5301.1  788.48  5354.5  795.29  5376.8  795.17  5403.7  798.27
#Mann=3,-1,0
  4159.2     0.1       0  4977.8    0.05       0  5022.3     0.1       0
#XS Ineff=2,0
    0.00 4902.30  778.30 5097.80    0.00  779.03
Bank Sta=4977.8,5022.3
XS Rating Curve= 0
Exp/Cntr=0.5,0.3

Type RM Length L Ch R = 1,13418,455,455,455
BEGIN DESCRIPTION:
Howards Creek 27.0
END DESCRIPTION:
XS GIS Cut Line= 3
      1310091.52       644030.90      1309937.26       643733.03
      1309830.88       643283.57
#Sta/Elev= 30
  4476.6  791.26  4485.7  790.32  4495.4  788.56  4521.3  785.64  4537.9  785.28
  4593.4  781.51  4662.8  778.77  4676.9  778.71  4759.0  775.11  4782.8  773.50
  4803.7  771.29  4810.5  771.60  4815.5  770.92  4863.8  770.14  4893.6  771.04
  4915.8  770.91  4974.6  771.89  4979.9  764.93  4981.4  761.93  5018.6  761.93
  5020.1  764.93  5030.2  771.79  5058.5  771.33  5077.8  770.38  5133.2  771.78
  5159.9  773.48  5168.9  774.43  5208.8  780.92  5224.3  784.45  5273.9  791.27
#Mann=3,-1,0
  4476.6     0.1       0  4979.9    0.05       0  5020.1     0.1       0
Bank Sta=4979.9,5020.1
XS Rating Curve= 0
Exp/Cntr=0.3,0.1

Type RM Length L Ch R = 1,12963,463,463,463
BEGIN DESCRIPTION:
Howards Creek 26.0
END DESCRIPTION:
XS GIS Cut Line= 3
      1310575.00       643475.00      1310356.83       643294.62
      1309925.00       643175.00
#Sta/Elev= 30
  4565.4  778.79  4623.6  777.65  4651.8  777.39  4667.5  776.62  4685.1  776.96
  4695.5  776.46  4726.3  775.89  4736.9  775.25  4761.2  775.99  4797.7  775.14
  4858.7  768.83  4933.9  769.36  4964.3  770.56  4979.5  763.85  4981.0  760.85
  5019.0  760.85  5020.5  763.85  5022.9  766.25  5040.0  769.10  5056.2  770.83
  5105.1  769.25  5152.4  769.78  5159.7  770.08  5177.4  769.87  5198.9  770.62
  5212.8  776.02  5232.2  784.06  5256.1  791.55  5281.2  798.00  5296.6  800.93
#Mann=3,-1,0
  4565.4    0.12       0  4979.5    0.05       0  5020.5     0.1       0
Bank Sta=4979.5,5020.5
XS Rating Curve= 0
Exp/Cntr=0.3,0.1

Type RM Length L Ch R = 1,12500,500,500,500
BEGIN DESCRIPTION:
Howards Creek 25.0
END DESCRIPTION:
XS GIS Cut Line= 3
      1310975.00       643625.00      1310465.25       642885.70
      1310125.00       642775.00
#Sta/Elev= 30
  4102.0  783.42  4114.4  783.67  4156.8  781.26  4274.2  778.58  4312.7  776.12
  4430.0  773.84  4468.0  770.81  4495.5  769.56  4603.0  767.34  4700.7  768.09
  4764.4  765.76  4859.6  768.35  4921.6  767.91  4950.1  769.05  4979.5  763.13
  4981.0  760.13  5019.0  760.13  5020.5  763.13  5036.7  769.27  5042.7  769.55
  5131.7  768.41  5160.6  768.97  5187.7  767.31  5220.5  766.66  5230.4  768.80
  5259.9  782.17  5273.5  790.65  5302.0  798.33  5320.4  802.44  5357.8  814.37
#Mann=3,-1,0
  4102.0    0.12       0  4979.5    0.05       0  5020.5     0.1       0
Bank Sta=4979.5,5020.5
XS Rating Curve= 0
Exp/Cntr=0.3,0.1

Type RM Length L Ch R = 1,12000,500,500,500
BEGIN DESCRIPTION:
Howards Creek 24.0
END DESCRIPTION:
XS GIS Cut Line= 3
      1311725.00       643175.00      1310765.24       642496.19
      1309960.05       642293.73
#Sta/Elev= 30
  3824.4  789.99  3840.7  789.66  3866.8  787.41  3891.4  781.58  3931.1  776.13
  3983.9  774.50  4008.3  772.07  4047.8  770.53  4216.8  767.64  4240.6  765.78
  4257.4  767.28  4329.2  766.19  4424.3  767.05  4596.5  765.88  4899.9  767.40
  4962.4  768.68  4979.5  762.77  4981.0  759.77  5019.0  759.77  5020.5  762.77
  5028.8  768.81  5092.2  767.36  5480.2  767.69  5504.7  766.23  5578.6  767.81
  5630.0  767.29  5702.4  769.38  5727.5  776.12  5774.6  791.75  5830.3  807.16
#Mann=3,-1,0
  3824.4    0.08       0  4979.5    0.05       0  5020.5     0.1       0
Bank Sta=4979.5,5020.5
XS Rating Curve= 0
Exp/Cntr=0.3,0.1

Type RM Length L Ch R = 1,11500,500,500,500
BEGIN DESCRIPTION:
Howards Creek 23.0
END DESCRIPTION:
XS GIS Cut Line= 3
      1311912.79       643091.77      1311079.34       642107.16
      1310405.88       641393.15
#Sta/Elev= 30
  3710.0  785.84  3833.3  783.83  3898.7  779.09  3979.3  775.01  4038.5  773.95
  4235.3  766.73  4267.9  768.05  4295.2  765.54  4574.4  767.34  4730.2  766.00
  4755.3  764.56  4960.4  768.99  4979.3  768.16  4979.5  762.32  4981.0  759.32
  5019.0  759.32  5020.5  762.32  5020.9  767.21  5040.5  768.98  5067.1  767.13
  5110.6  767.64  5290.1  765.73  5520.0  766.32  5762.1  774.79  5781.9  773.24
  5797.6  776.43  5845.2  780.36  5867.9  786.02  5910.8  801.37  5981.5  815.10
#Mann=3,-1,0
  3710.0    0.08       0  4979.5    0.05       0  5020.5     0.1       0
Bank Sta=4979.5,5020.5
XS Rating Curve= 0
Exp/Cntr=0.3,0.1

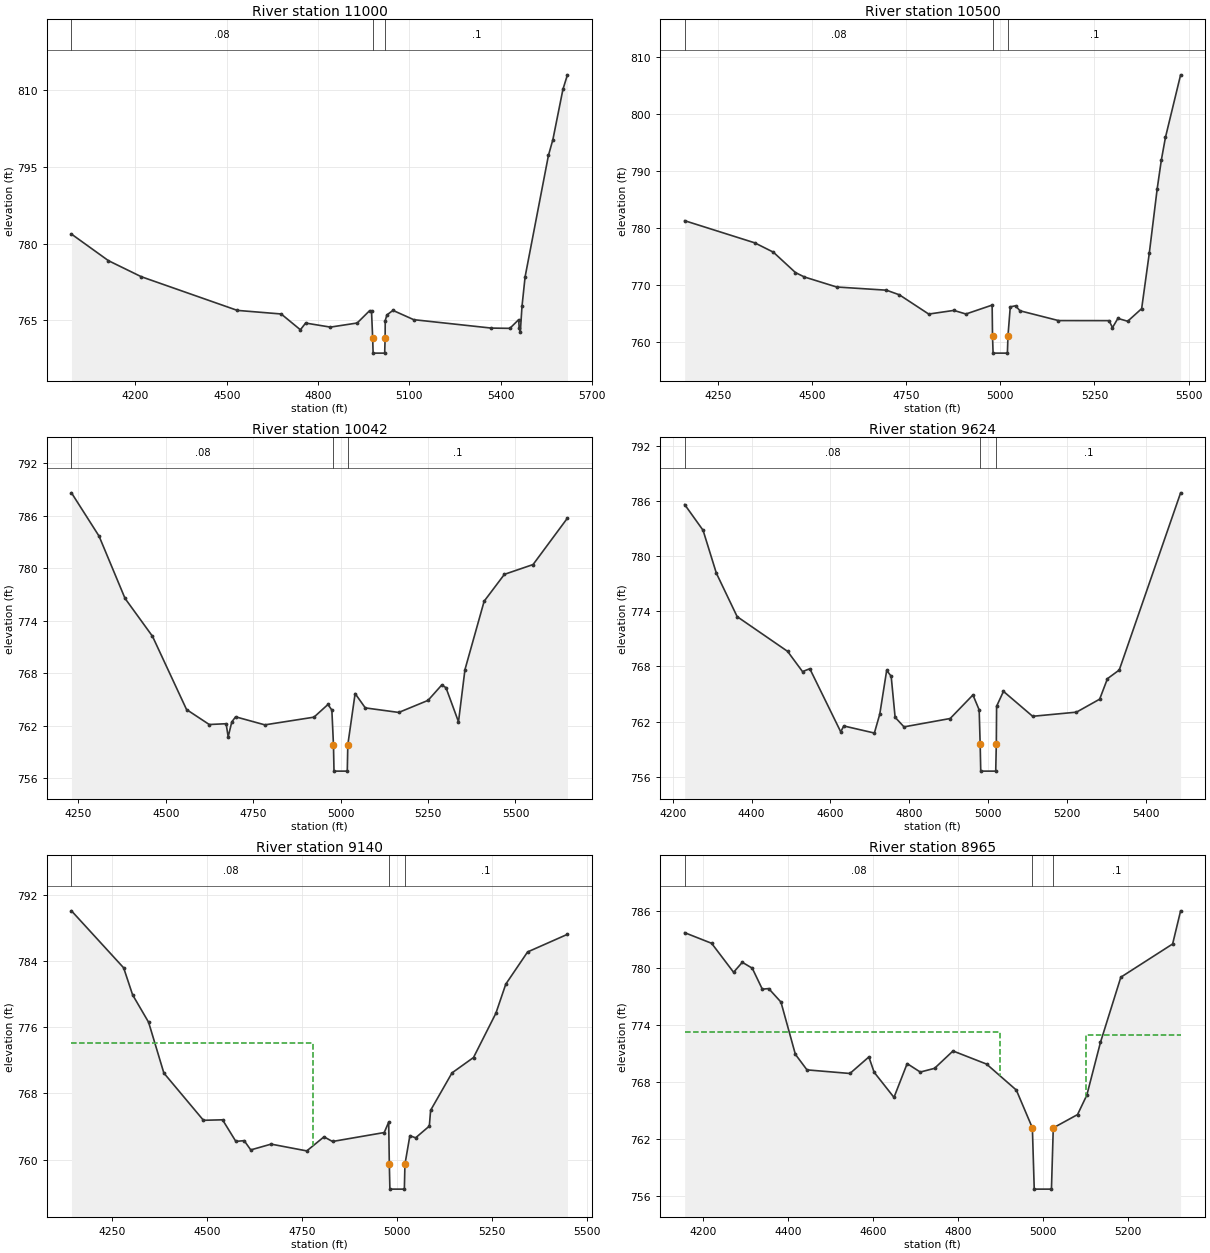
Type RM Length L Ch R = 1,11000,500,500,500
BEGIN DESCRIPTION:
Howards Creek 22.0
END DESCRIPTION:
XS GIS Cut Line= 3
      1311997.49       642891.15      1311531.40       641994.76
      1311547.20       641375.32
#Sta/Elev= 30
  3989.7  781.84  4111.2  776.66  4219.3  773.53  4534.7  766.97  4678.9  766.27
  4742.0  763.19  4759.2  764.50  4840.6  763.71  4928.6  764.51  4969.6  766.92
  4975.8  766.78  4979.5  761.64  4981.0  758.64  5019.0  758.64  5020.5  761.64
  5020.8  764.99  5026.4  766.09  5046.3  766.97  5114.4  765.16  5369.5  763.52
  5430.3  763.47  5459.3  765.16  5461.1  763.48  5464.7  762.70  5470.2  767.73
  5480.5  773.52  5557.1  797.16  5571.8  800.26  5604.9  810.08  5619.6  812.88
#Mann=3,-1,0
  3989.7    0.08       0  4979.5    0.05       0  5020.5     0.1       0
Bank Sta=4979.5,5020.5
XS Rating Curve= 0
Exp/Cntr=0.3,0.1

Type RM Length L Ch R = 1,10500,458,458,458
BEGIN DESCRIPTION:
Howards Creek 21.0
END DESCRIPTION:
XS GIS Cut Line= 4
      1312077.74       642819.81      1311993.94       642467.09
      1312024.56       641993.06      1312125.00       641525.00
#Sta/Elev= 30
  4162.4  781.31  4348.5  777.43  4397.8  775.80  4456.6  772.22  4480.4  771.45
  4565.8  769.70  4698.0  769.14  4732.3  768.33  4810.2  764.96  4876.9  765.60
  4908.9  764.97  4978.5  766.53  4979.5  761.12  4981.0  758.12  5019.0  758.12
  5020.5  761.12  5026.6  766.22  5040.5  766.41  5052.6  765.53  5154.6  763.82
  5288.7  763.81  5297.9  762.59  5312.2  764.20  5338.2  763.70  5375.3  765.91
  5395.7  775.69  5416.5  786.88  5427.6  791.95  5438.5  795.91  5478.7  806.85
#Mann=3,-1,0
  4162.4    0.08       0  4979.5    0.05       0  5020.5     0.1       0
Bank Sta=4979.5,5020.5
XS Rating Curve= 0
Exp/Cntr=0.3,0.1

Type RM Length L Ch R = 1,10042,418,418,418
BEGIN DESCRIPTION:
Howards Creek 20.0
END DESCRIPTION:
XS GIS Cut Line= 3
      1312523.57       642761.85      1312465.62       641665.11
      1312554.78       641357.49
#Sta/Elev= 30
  4230.1  788.62  4309.0  783.67  4383.3  776.55  4461.8  772.22  4559.3  763.84
  4624.2  762.13  4672.5  762.22  4678.3  760.72  4688.7  762.43  4699.6  763.01
  4783.2  762.09  4923.7  762.97  4963.7  764.42  4974.9  763.78  4979.5  759.80
  4981.0  756.80  5019.0  756.80  5020.5  759.80  5041.4  765.67  5070.5  764.03
  5166.3  763.51  5250.0  764.89  5289.2  766.65  5301.3  766.34  5337.1  762.44
  5355.6  768.41  5410.5  776.23  5468.4  779.30  5550.4  780.42  5648.7  785.73
#Mann=3,-1,0
  4230.1    0.08       0  4979.5    0.05       0  5020.5     0.1       0
Bank Sta=4979.5,5020.5
XS Rating Curve= 0
Exp/Cntr=0.3,0.1

Type RM Length L Ch R = 1,9624,484,484,484
BEGIN DESCRIPTION:
Howards Creek 19.0
END DESCRIPTION:
XS GIS Cut Line= 4
      1313125.45       642730.65      1313013.99       642351.69
      1312822.28       641749.82      1312875.00       641525.00
#Sta/Elev= 30
  4230.2  785.60  4276.9  782.80  4310.6  778.14  4363.4  773.41  4491.2  769.64
  4529.1  767.44  4547.6  767.75  4626.0  760.89  4633.7  761.53  4711.3  760.76
  4725.0  762.82  4742.5  767.57  4753.9  766.93  4763.9  762.47  4786.4  761.43
  4903.5  762.34  4961.2  764.90  4977.0  763.28  4979.5  759.62  4981.0  756.62
  5019.0  756.62  5020.5  759.62  5021.2  763.67  5038.6  765.29  5112.6  762.58
  5223.7  763.03  5282.5  764.44  5302.3  766.67  5332.2  767.61  5487.8  786.87
#Mann=3,-1,0
  4230.2    0.08       0  4979.5    0.05       0  5020.5     0.1       0
Bank Sta=4979.5,5020.5
XS Rating Curve= 0
Exp/Cntr=0.3,0.1

Type RM Length L Ch R = 1,9140,175,175,175
BEGIN DESCRIPTION:
Howards Creek 18.0
END DESCRIPTION:
XS GIS Cut Line= 3
      1313129.90       642819.81      1313406.32       641932.61
      1313598.03       641611.61
#Sta/Elev= 30
  4144.3  790.06  4281.4  783.17  4305.0  779.90  4347.0  776.59  4387.1  770.45
  4491.1  764.74  4541.3  764.80  4576.2  762.19  4598.1  762.28  4615.4  761.16
  4668.9  761.86  4762.6  761.04  4807.8  762.74  4830.2  762.18  4966.1  763.26
  4977.8  764.52  4979.5  759.42  4981.0  756.42  5019.0  756.42  5020.5  759.42
  5033.5  762.88  5048.5  762.62  5084.6  764.04  5088.0  765.95  5144.2  770.47
  5200.7  772.33  5259.5  777.68  5285.5  781.20  5342.8  785.09  5447.5  787.22
#Mann=3,-1,0
  4144.3    0.08       0  4979.5    0.05       0  5020.5     0.1       0
#XS Ineff=2,0
    0.00 4778.10  774.07               0
Bank Sta=4979.5,5020.5
XS Rating Curve= 0
Exp/Cntr=0.5,0.3

Type RM Length L Ch R = 1,8965,82,82,82
BEGIN DESCRIPTION:
Owls Den Rd u/s HC
END DESCRIPTION:
XS GIS Cut Line= 6
      1313384.15       642792.29      1313465.98       642457.56
      1313506.89       642189.77      1313551.52       641981.49
      1313585.00       641743.46      1313603.59       641646.76
#Sta/Elev= 30
  4157.0  783.71  4220.5  782.59  4272.2  779.54  4292.7  780.59  4316.1  779.97
  4339.8  777.76  4354.9  777.82  4383.7  776.40  4417.6  770.90  4444.9  769.26
  4546.0  768.88  4590.6  770.62  4603.0  769.01  4649.7  766.36  4680.7  769.92
  4711.6  769.03  4745.1  769.42  4788.6  771.25  4867.6  769.87  4937.7  767.13
  4975.4  763.15  4979.8  756.70  5020.3  756.70  5024.6  763.15  5081.7  764.55
  5103.5  766.59  5135.6  772.15  5183.6  779.02  5305.5  782.52  5324.3  786.01
#Mann=3,-1,0
  4157.0    0.08       0  4975.4   0.048       0  5024.6     0.1       0
#XS Ineff=2,0
    0.00 4899.30  773.28 5100.80    0.00  772.96
Bank Sta=4975.4,5024.6
XS Rating Curve= 0
Exp/Cntr=0.5,0.3

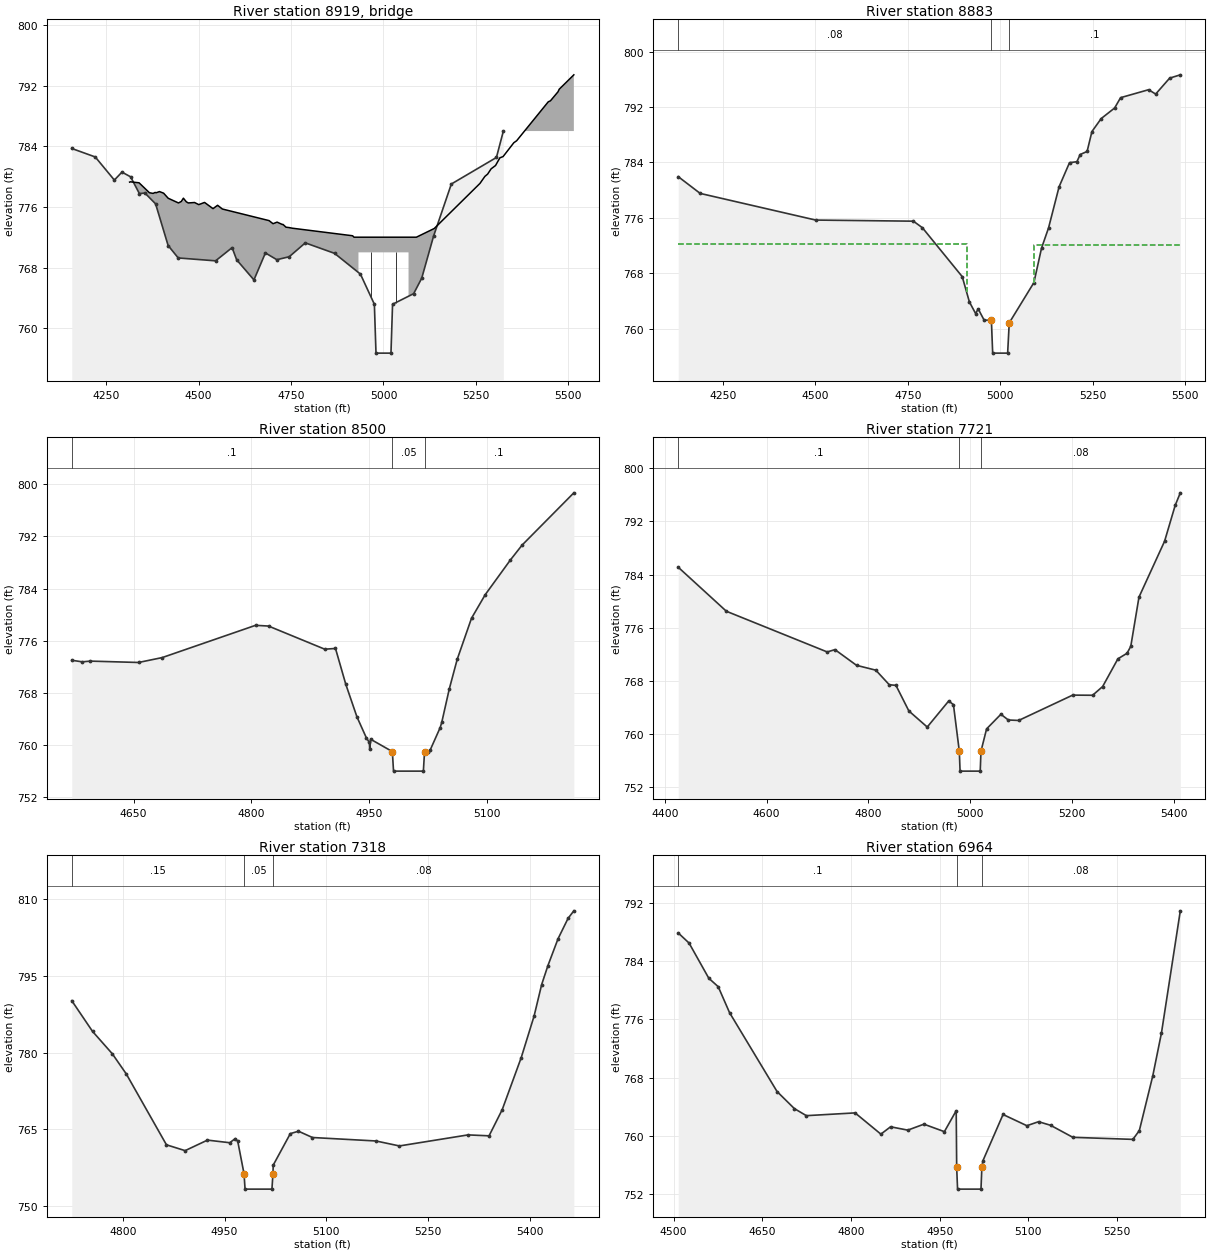
Type RM Length L Ch R =3,8919,,,
BEGIN DESCRIPTION:
Owls Den Rd TOR HC
Structure ID: LDS_HC_02
Approximate Survey Structure
END DESCRIPTION:
Bridge Culvert--1,0,-1,-1,0
Deck Dist Width WeirC Skew NumUp NumDn MinLoCord MaxHiCord MaxSubmerge Is_Ogee
33,26,3,,55,55,,,,0,1,1,,,
  4313.4  4315.4  4339.0  4367.0  4376.8  4382.6  4384.9  4394.2  4405.4  4417.8
  4445.6  4453.3  4458.9  4466.8  4472.1  4489.0  4500.5  4516.1  4539.0  4551.3
  4551.5  4564.3  4690.6  4701.3  4712.3  4726.3  4728.2  4736.4  4746.4  4746.5
  4746.7  4753.2  4916.5  4920.4  4932.3  4932.3  5067.8  5067.8  5089.0  5137.4
  5261.0  5274.4  5281.6  5291.1  5303.1  5314.5  5315.0  5323.5  5352.6  5360.2
  5445.7  5451.6  5472.2  5475.3  5514.9
  779.27  779.31  779.18  777.87  777.78  777.91  777.86  778.02  777.81  777.14
  776.52  776.72  777.15  776.67  776.52  776.58  776.30  776.59  775.77  776.21
  776.21  775.72  774.19  773.78  773.99  773.68  773.69  773.32  773.26  773.26
  773.25  773.19  772.19  772.00  772.00  772.00  772.00  772.00  772.00  773.15
  779.10  780.03  780.32  781.02  781.46  782.45  782.48  782.64  784.47  784.73
  789.87  790.00  791.20  791.53  793.43
  736.70  736.70  736.70  736.70  736.70  736.70  736.70  736.70  736.70  736.70
  736.70  736.70  736.70  736.70  736.70  736.70  736.70  736.70  736.70  736.70
  736.70  736.70  736.70  736.70  736.70  736.70  736.70  736.70  736.70  736.70
  736.70  736.70  736.70  736.70  736.70  770.00  770.00  736.70  736.70  736.70
  736.70  736.70  736.70  736.70  736.70  736.70  736.70  736.70  736.70  736.70
  736.70  736.70  736.70  736.70  736.70
  4313.4  4315.4  4339.0  4367.0  4376.8  4382.6  4384.9  4394.2  4405.4  4417.8
  4445.6  4453.3  4458.9  4466.8  4472.1  4489.0  4500.5  4516.1  4539.0  4551.3
  4551.5  4564.3  4690.6  4701.3  4712.3  4726.3  4728.2  4736.4  4746.4  4746.5
  4746.7  4753.2  4916.5  4920.4  4932.3  4932.3  5067.8  5067.8  5089.0  5137.4
  5261.0  5274.4  5281.6  5291.1  5303.1  5314.5  5315.0  5323.5  5352.6  5360.2
  5445.7  5451.6  5472.2  5475.3  5514.9
  779.27  779.31  779.18  777.87  777.78  777.91  777.86  778.02  777.81  777.14
  776.52  776.72  777.15  776.67  776.52  776.58  776.30  776.59  775.77  776.21
  776.21  775.72  774.19  773.78  773.99  773.68  773.69  773.32  773.26  773.26
  773.25  773.19  772.19  772.00  772.00  772.00  772.00  772.00  772.00  773.15
  779.10  780.03  780.32  781.02  781.46  782.45  782.48  782.64  784.47  784.73
  789.87  790.00  791.20  791.53  793.43
  736.70  736.70  736.70  736.70  736.70  736.70  736.70  736.70  736.70  736.70
  736.70  736.70  736.70  736.70  736.70  736.70  736.70  736.70  736.70  736.70
  736.70  736.70  736.70  736.70  736.70  736.70  736.70  736.70  736.70  736.70
  736.70  736.70  736.70  736.70  736.70  770.00  770.00  736.70  736.70  736.70
  736.70  736.70  736.70  736.70  736.70  736.70  736.70  736.70  736.70  736.70
  736.70  736.70  736.70  736.70  736.70
Pier Skew, UpSta & Num, DnSta & Num=,4966.1,2,4966.1,2,0,0,0,0,0
       1       1
  759.79  770.00
       1       1
  762.05  770.00
Pier Skew, UpSta & Num, DnSta & Num=,5033.9,2,5033.9,2,0,0,0,0,0
       1       1
  761.67  770.00
       1       1
  761.32  770.00
Abutment Skew #Up #Dn=,2,2
  4932.3  4945.0
  770.00  766.28
  4932.3  4945.0
  770.00  761.21
Abutment Skew #Up #Dn=,2,2
  5055.0  5067.8
  763.78  770.00
  5055.0  5067.8
  763.74  770.00
BR Coef=1,1,0,1.25,0,,,0.8,0,2,0,
WSPro=,,,, 1 ,,,, 0 ,,,, 0 ,,,,-1 ,-1 ,-1 , 0 , 0 , 0 , 0 , 0
BC Design=,,0,,0,,,,,,

Type RM Length L Ch R = 1,8883,383,383,383
BEGIN DESCRIPTION:
Owls Den Rd d/s HC
END DESCRIPTION:
XS GIS Cut Line= 6
      1313487.12       642795.07      1313591.26       642438.02
      1313643.33       642125.60      1313628.31       641967.62
      1313691.68       641645.81      1313758.63       641478.44
#Sta/Elev= 30
  4129.0  781.94  4188.4  779.52  4500.9  775.67  4765.3  775.51  4789.7  774.56
  4897.4  767.50  4916.8  763.85  4933.8  762.15  4940.5  762.85  4956.8  761.20
  4976.3  761.22  4979.8  756.45  5020.3  756.45  5024.6  760.82  5091.4  766.64
  5112.0  771.62  5131.0  774.54  5159.5  780.48  5187.7  783.96  5207.7  784.10
  5216.6  785.14  5235.3  785.58  5248.3  788.45  5273.4  790.33  5309.8  791.86
  5325.9  793.35  5401.7  794.50  5420.8  793.87  5458.6  796.17  5487.5  796.65
#Mann=3,-1,0
  4129.0    0.08       0  4976.3   0.048       0  5024.6     0.1       0
#XS Ineff=2,0
    0.00 4909.30  772.23 5090.80    0.00  772.04
Bank Sta=4976.3,5024.6
XS Rating Curve= 0
Exp/Cntr=0.5,0.3

Type RM Length L Ch R = 1,8500,779,779,779
BEGIN DESCRIPTION:
Howards Creek 17.0
END DESCRIPTION:
XS GIS Cut Line= 3
      1313737.49       642680.72      1313871.38       642353.42
      1314064.78       641881.07
#Sta/Elev= 30
  4571.3  773.01  4584.6  772.77  4595.1  772.88  4656.3  772.67  4686.4  773.42
  4805.3  778.37  4821.8  778.26  4893.4  774.71  4907.1  774.82  4920.2  769.33
  4934.4  764.33  4946.4  761.11  4950.2  760.41  4950.7  759.32  4951.9  760.89
  4979.5  759.00  4981.0  756.00  5019.0  756.00  5020.5  759.00  5024.7  759.00
  5027.8  759.27  5040.4  762.68  5042.4  763.48  5052.0  768.61  5062.1  773.16
  5080.3  779.46  5097.8  783.08  5129.7  788.38  5144.7  790.68  5210.6  798.70
#Mann=3,-1,0
  4571.3     0.1       0  4979.5    0.05       0  5020.5     0.1       0
Bank Sta=4979.5,5020.5
XS Rating Curve= 0
Exp/Cntr=0.3,0.1

Type RM Length L Ch R = 1,7721,403,403,403
BEGIN DESCRIPTION:
Howards Creek 16.0
END DESCRIPTION:
XS GIS Cut Line= 4
      1314561.02       643030.07      1314596.69       642552.31
      1314681.40       642333.86      1314671.59       642061.01
#Sta/Elev= 30
  4426.5  785.11  4521.1  778.49  4719.2  772.37  4734.4  772.72  4776.8  770.36
  4814.7  769.63  4841.1  767.44  4854.2  767.35  4879.6  763.50  4915.7  761.08
  4957.9  765.00  4967.2  764.44  4978.7  757.45  4980.2  754.45  5019.8  754.45
  5021.3  757.45  5032.3  760.80  5060.4  763.00  5075.0  762.14  5095.3  762.07
  5201.4  765.88  5240.6  765.86  5260.3  767.17  5290.3  771.34  5308.2  772.17
  5315.6  773.22  5331.7  780.62  5382.0  789.02  5402.8  794.41  5412.9  796.30
#Mann=3,-1,0
  4426.5     0.1       0  4978.7    0.05       0  5021.3    0.08       0
Bank Sta=4978.7,5021.3
XS Rating Curve= 0
Exp/Cntr=0.3,0.1

Type RM Length L Ch R = 1,7318,354,354,354
BEGIN DESCRIPTION:
Howards Creek 15.0
END DESCRIPTION:
XS GIS Cut Line= 2
      1315188.75       642550.35      1314689.42       642004.65
#Sta/Elev= 30
  4724.9  790.17  4755.5  784.16  4784.7  779.77  4805.2  775.84  4864.4  761.97
  4891.9  760.83  4924.8  762.89  4957.6  762.38  4965.9  763.19  4969.4  762.68
  4978.7  756.30  4980.2  753.30  5019.8  753.30  5021.3  756.30  5021.7  758.00
  5046.9  764.16  5058.9  764.63  5079.5  763.40  5173.1  762.72  5207.6  761.75
  5308.7  763.91  5339.7  763.73  5359.1  768.86  5387.1  779.04  5406.0  787.15
  5417.2  793.33  5426.4  797.03  5441.3  802.28  5456.1  806.28  5464.6  807.75
#Mann=3,-1,0
  4724.9    0.15       0  4978.7    0.05       0  5021.3    0.08       0
Bank Sta=4978.7,5021.3
XS Rating Curve= 0
Exp/Cntr=0.3,0.1

Type RM Length L Ch R = 1,6964,458,458,458
BEGIN DESCRIPTION:
Howards Creek 14.0
END DESCRIPTION:
XS GIS Cut Line= 3
      1315525.00       642425.00      1315302.89       642161.59
      1314953.35       641797.79
#Sta/Elev= 30
  4507.8  787.90  4526.1  786.51  4559.5  781.67  4575.4  780.51  4594.6  776.94
  4674.9  766.10  4704.2  763.75  4724.5  762.78  4806.9  763.16  4850.5  760.24
  4866.9  761.25  4896.0  760.79  4923.3  761.61  4957.9  760.58  4977.9  763.46
  4978.7  755.68  4980.2  752.68  5019.8  752.68  5021.3  755.68  5023.0  756.57
  5057.1  762.94  5097.4  761.40  5117.2  761.95  5137.4  761.46  5175.2  759.80
  5276.7  759.52  5287.6  760.73  5310.3  768.24  5325.0  774.14  5356.9  790.94
#Mann=3,-1,0
  4507.8     0.1       0  4978.7    0.05       0  5021.3    0.08       0
Bank Sta=4978.7,5021.3
XS Rating Curve= 0
Exp/Cntr=0.3,0.1

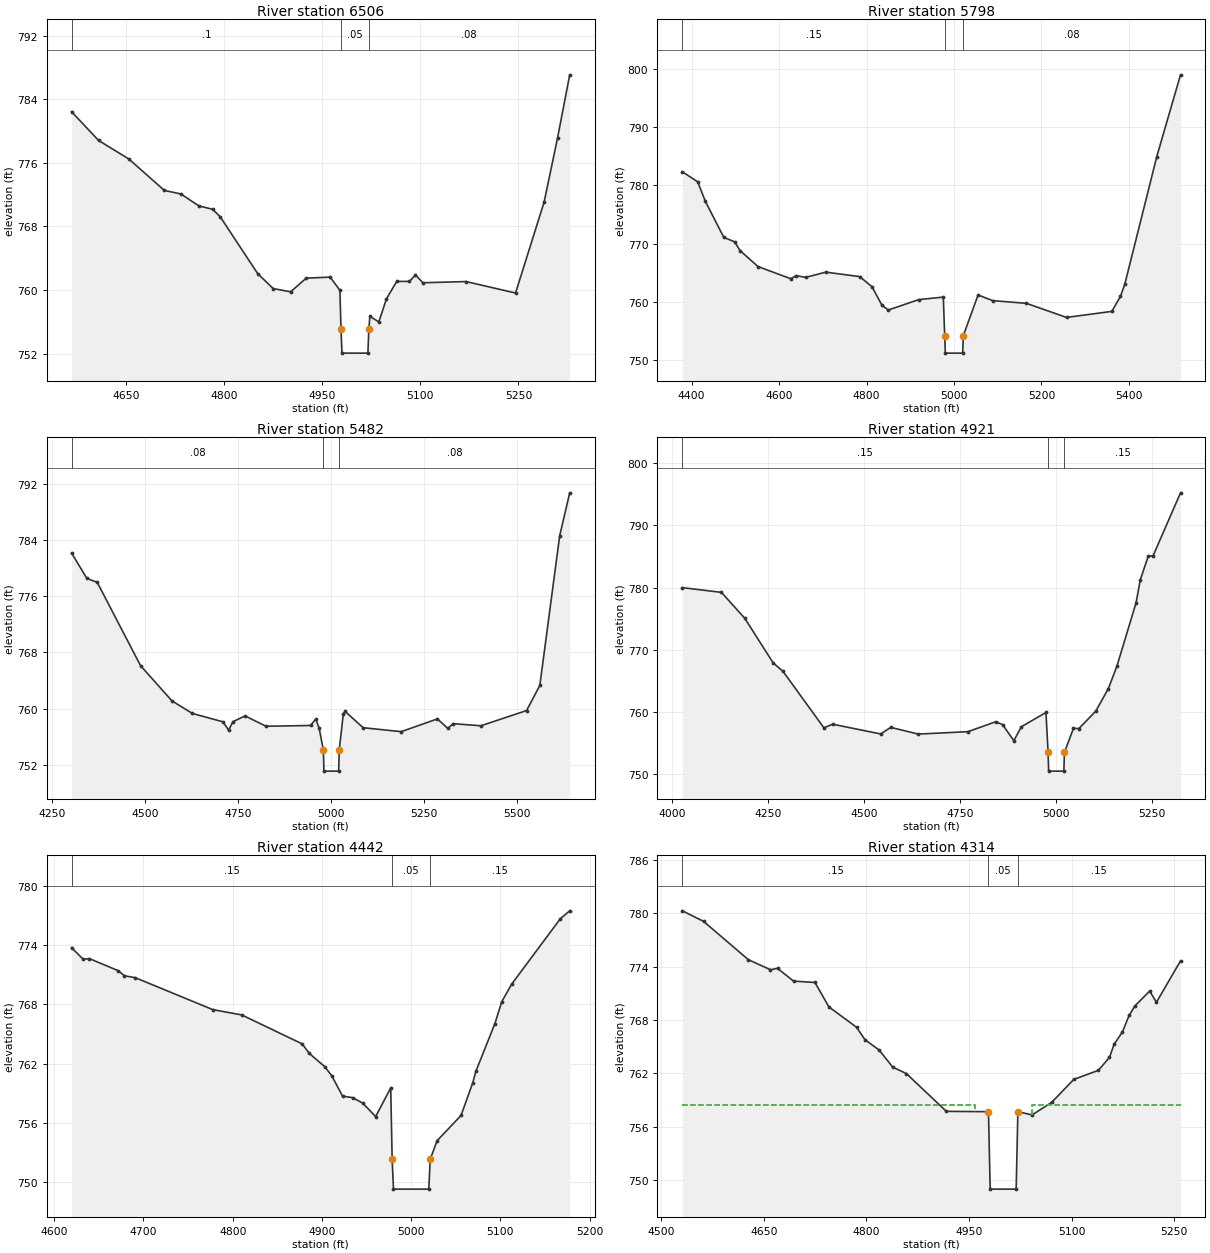
Type RM Length L Ch R = 1,6506,708,708,708
BEGIN DESCRIPTION:
Howards Creek 13.0
END DESCRIPTION:
XS GIS Cut Line= 4
      1315795.08       641927.97      1315559.68       641724.67
      1315363.52       641631.94      1315135.25       641582.01
#Sta/Elev= 30
  4566.7  782.42  4607.9  778.81  4654.2  776.48  4708.6  772.52  4733.8  772.08
  4761.5  770.57  4782.5  770.15  4794.3  769.17  4851.4  762.05  4875.0  760.18
  4901.6  759.77  4925.6  761.49  4962.1  761.62  4977.0  759.96  4978.7  755.06
  4980.2  752.06  5019.8  752.06  5021.3  755.06  5022.8  756.68  5036.6  755.99
  5048.2  758.89  5063.9  761.08  5083.4  761.08  5092.6  761.90  5103.8  760.91
  5169.8  761.06  5245.6  759.62  5289.3  771.06  5309.9  779.15  5328.4  787.06
#Mann=3,-1,0
  4566.7     0.1       0  4978.7    0.05       0  5021.3    0.08       0
Bank Sta=4978.7,5021.3
XS Rating Curve= 0
Exp/Cntr=0.3,0.1

Type RM Length L Ch R = 1,5798,316,316,316
BEGIN DESCRIPTION:
Howards Creek 12.0
END DESCRIPTION:
XS GIS Cut Line= 3
      1316123.22       641781.74      1316009.08       641318.07
      1315745.15       640711.74
#Sta/Elev= 30
  4379.0  782.32  4414.0  780.60  4431.7  777.23  4473.7  771.07  4498.5  770.31
  4510.7  768.81  4551.8  766.07  4626.8  763.98  4639.2  764.51  4660.9  764.21
  4706.9  765.11  4784.5  764.34  4812.4  762.62  4835.4  759.41  4850.0  758.62
  4919.4  760.40  4975.5  760.83  4978.7  754.22  4980.2  751.22  5019.8  751.22
  5021.3  754.22  5055.0  761.19  5088.6  760.22  5165.4  759.76  5257.3  757.34
  5360.8  758.38  5380.5  760.95  5390.5  763.06  5463.6  784.94  5517.8  798.95
#Mann=3,-1,0
  4379.0    0.15       0  4978.7    0.05       0  5021.3    0.08       0
Bank Sta=4978.7,5021.3
XS Rating Curve= 0
Exp/Cntr=0.3,0.1

Type RM Length L Ch R = 1,5482,561,561,561
BEGIN DESCRIPTION:
Howards Creek 11.0
END DESCRIPTION:
XS GIS Cut Line= 3
      1316219.51       641781.74      1316276.58       641186.11
      1316091.12       640469.21
#Sta/Elev= 30
  4301.9  782.18  4342.9  778.56  4370.9  777.99  4487.3  766.11  4571.9  761.08
  4626.9  759.29  4709.0  758.10  4723.9  756.91  4735.9  758.13  4768.4  758.94
  4824.6  757.47  4944.3  757.58  4958.2  758.49  4967.2  757.22  4978.7  754.07
  4980.2  751.07  5019.8  751.07  5021.3  754.07  5032.4  759.27  5037.3  759.58
  5085.7  757.26  5188.0  756.70  5285.2  758.52  5313.3  757.16  5327.1  757.84
  5402.2  757.54  5524.9  759.71  5560.5  763.29  5613.9  784.64  5640.8  790.76
#Mann=3,-1,0
  4301.9    0.08       0  4978.7    0.05       0  5021.3    0.08       0
Bank Sta=4978.7,5021.3
XS Rating Curve= 0
Exp/Cntr=0.3,0.1

Type RM Length L Ch R = 1,4921,479,479,479
BEGIN DESCRIPTION:
Howards Creek 10.0
END DESCRIPTION:
XS GIS Cut Line= 4
      1316526.25       641842.37      1316808.01       641014.91
      1316741.71       640732.78      1316765.21       640601.18
#Sta/Elev= 30
  4026.0  779.98  4127.7  779.22  4188.5  775.06  4262.5  767.89  4288.3  766.52
  4394.7  757.45  4417.4  758.04  4542.8  756.47  4568.7  757.53  4640.6  756.45
  4770.1  756.84  4842.6  758.44  4860.4  757.96  4889.4  755.39  4909.3  757.64
  4973.2  759.92  4978.7  753.50  4980.2  750.50  5019.8  750.50  5021.3  753.50
  5044.8  757.37  5059.0  757.34  5103.1  760.15  5135.8  763.77  5158.1  767.37
  5207.9  777.54  5219.0  781.25  5239.5  785.01  5252.3  785.10  5323.7  795.21
#Mann=3,-1,0
  4026.0    0.15       0  4978.7    0.05       0  5021.3    0.15       0
Bank Sta=4978.7,5021.3
XS Rating Curve= 0
Exp/Cntr=0.3,0.1

Type RM Length L Ch R = 1,4442,128,128,128
BEGIN DESCRIPTION:
Howards Creek 9.0
END DESCRIPTION:
XS GIS Cut Line= 4
      1317432.89       641038.09      1317300.29       640915.97
      1317233.16       640755.61      1317141.85       640573.00
#Sta/Elev= 30
  4619.4  773.74  4632.5  772.57  4639.3  772.64  4671.3  771.43  4678.7  770.90
  4690.7  770.71  4777.6  767.48  4810.1  766.94  4877.9  764.01  4885.7  763.06
  4903.0  761.72  4911.0  760.79  4923.1  758.73  4934.5  758.57  4945.7  758.02
  4960.2  756.66  4977.1  759.56  4978.7  752.32  4980.2  749.32  5019.8  749.32
  5021.3  752.32  5029.1  754.22  5055.9  756.77  5069.1  760.09  5072.6  761.25
  5093.9  766.07  5101.6  768.29  5112.8  770.07  5167.2  776.67  5177.7  777.47
#Mann=3,-1,0
  4619.4    0.15       0  4978.7    0.05       0  5021.3    0.15       0
Bank Sta=4978.7,5021.3
XS Rating Curve= 0
Exp/Cntr=0.5,0.3

Type RM Length L Ch R = 1,4314,74,74,74
BEGIN DESCRIPTION:
Private Drive u/s Howards Creek
END DESCRIPTION:
XS GIS Cut Line= 6
      1317609.79       641026.68      1317481.40       640901.13
      1317370.12       640761.32      1317304.49       640610.09
      1317270.25       640553.03      1317158.97       640470.28
#Sta/Elev= 30
  4530.9  780.27  4561.8  779.09  4627.4  774.78  4659.7  773.65  4670.0  773.81
  4693.5  772.37  4724.8  772.22  4745.2  769.47  4785.6  767.19  4798.0  765.78
  4818.5  764.64  4838.5  762.71  4858.5  761.98  4916.9  757.74  4978.5  757.70
  4981.0  749.00  5019.0  749.00  5021.5  757.70  5042.3  757.34  5070.8  758.74
  5103.3  761.33  5139.3  762.35  5155.4  763.80  5162.3  765.28  5174.4  766.67
  5184.1  768.51  5192.7  769.59  5214.2  771.25  5224.1  770.00  5259.3  774.64
#Mann=3,-1,0
  4530.9    0.15       0  4978.5    0.05       0  5021.5    0.15       0
#XS Ineff=2,0
    0.00 4958.50  758.50 5041.50    0.00  758.50
Bank Sta=4978.5,5021.5
XS Rating Curve= 0
Exp/Cntr=0.5,0.3