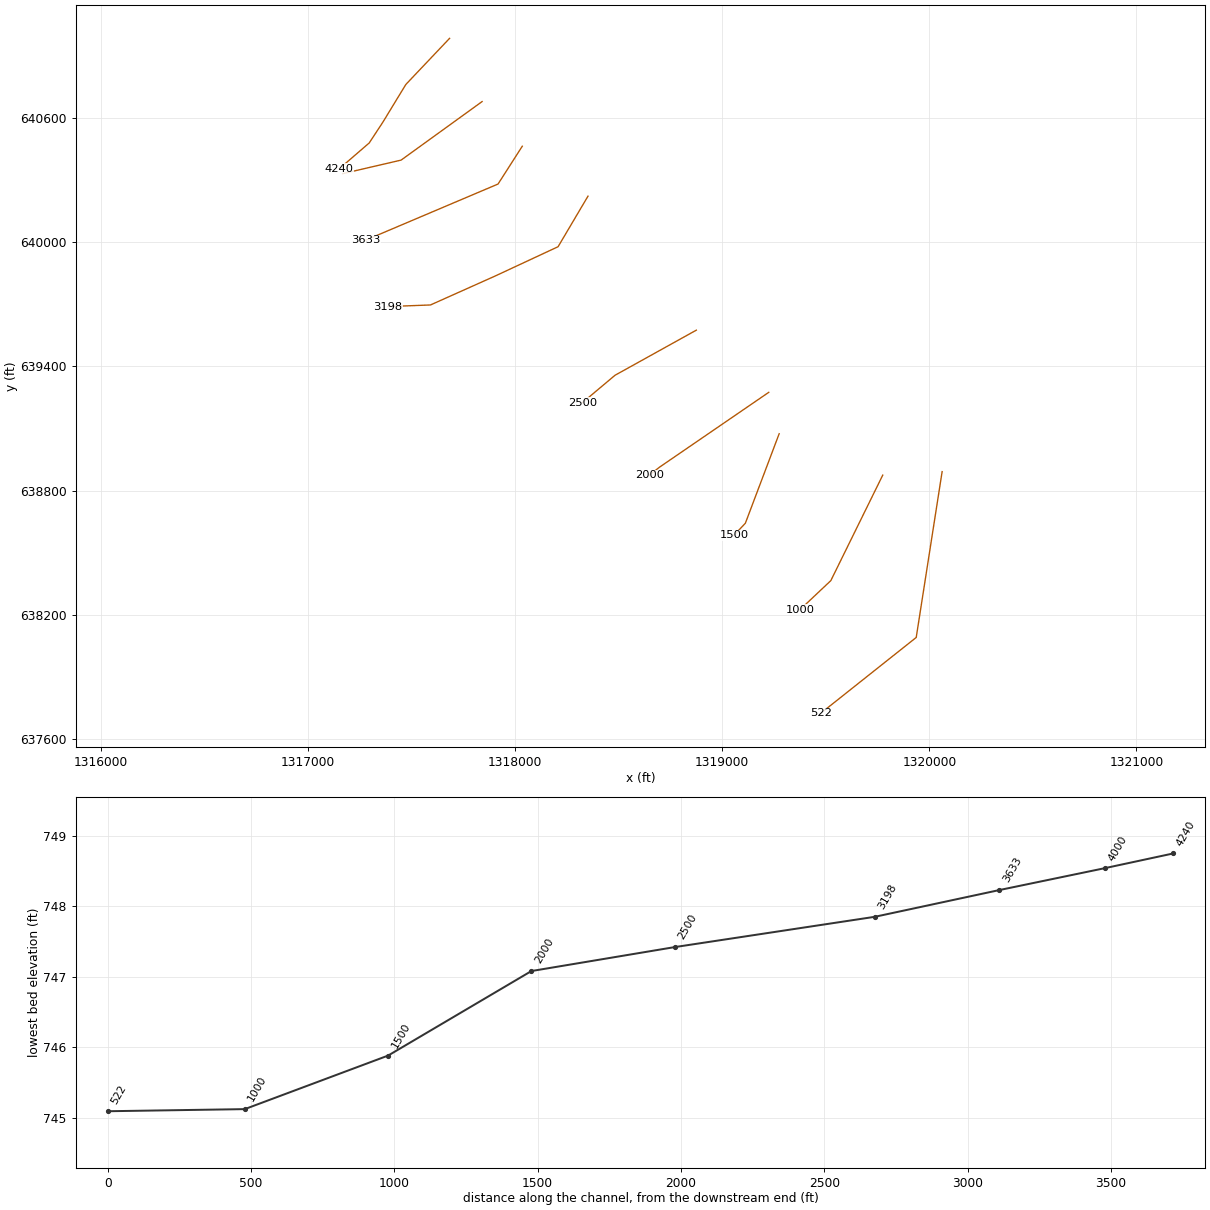
HEC-RAS study Howards Creek.prj: Howards Creek Limited Detail Study

--- Howards Creek.g01 (geometry) --- (continued)

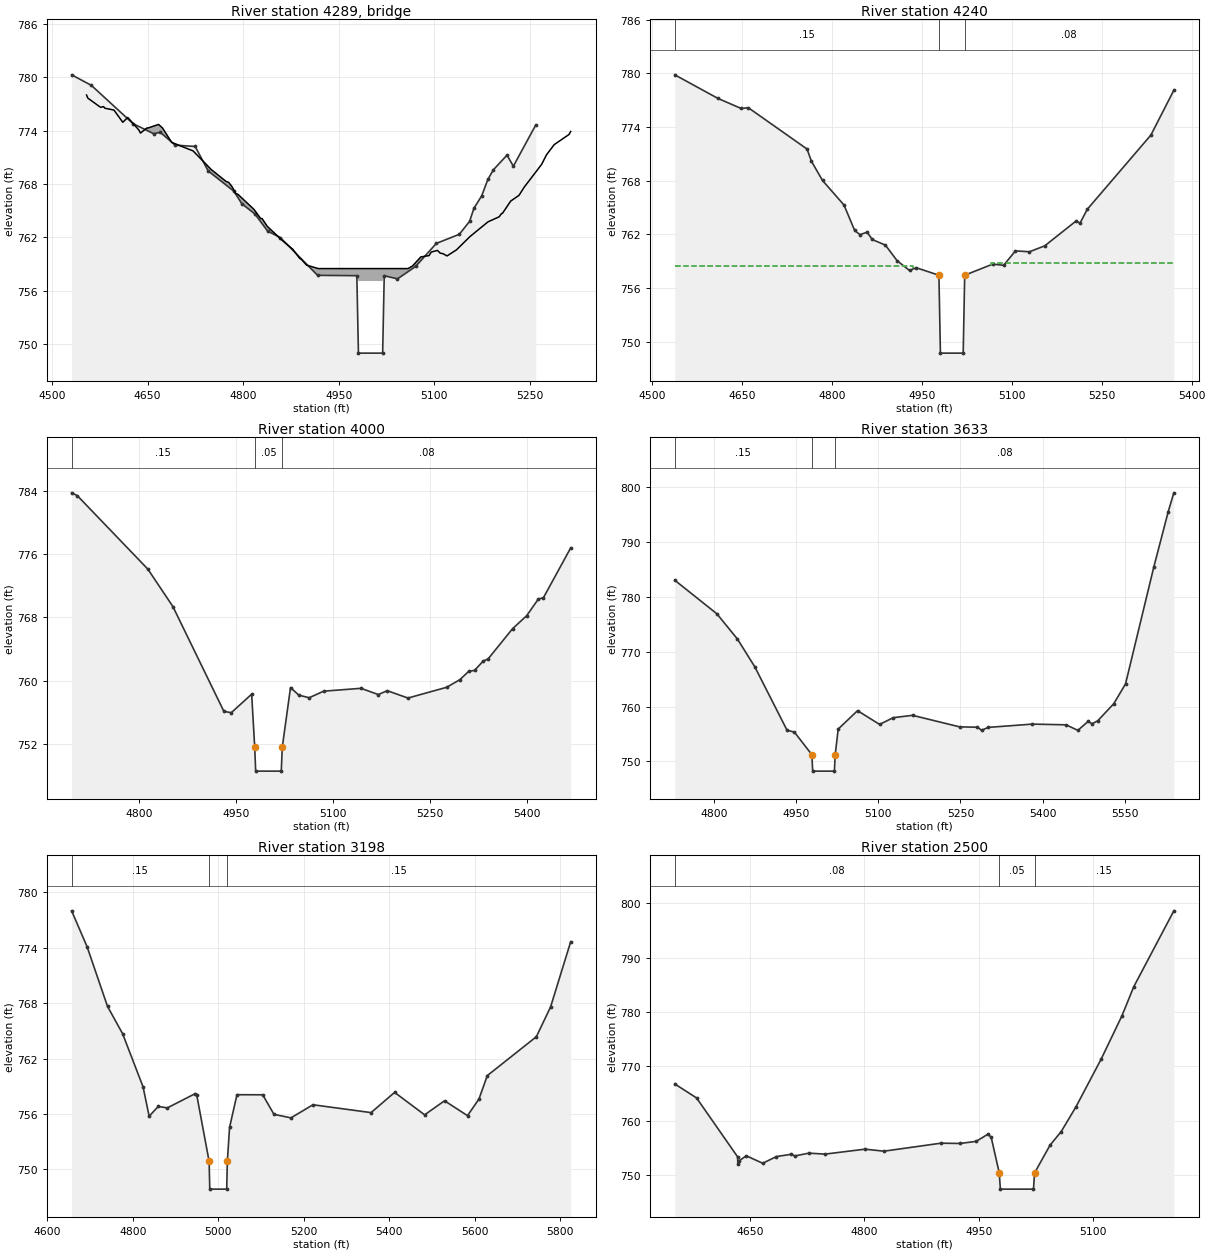
Type RM Length L Ch R =3,4289,,,
BEGIN DESCRIPTION:
Private Drive TOR Howards Creek
Structure ID: LDS_HC_01
Approximate Survey Structure
END DESCRIPTION:
Bridge Culvert--1,0,-1,-1,0
Deck Dist Width WeirC Skew NumUp NumDn MinLoCord MaxHiCord MaxSubmerge Is_Ogee
20,10,3,, 59, 59,,,,0,1,1,,,
  4554.3  4556.4  4576.3  4581.0  4583.0  4597.3  4611.2  4619.0  4636.4  4638.9
  4649.3  4650.7  4667.3  4673.6  4687.9  4721.5  4750.0  4773.3  4777.3  4782.7
  4788.3  4791.8  4817.2  4827.7  4829.7  4837.9  4861.9  4878.0  4889.1  4890.7
  4899.6  4918.0  4978.5  4978.5  5021.5  5021.5  5058.8  5066.0  5078.9  5091.8
  5095.3  5105.1  5109.2  5113.8  5120.0  5134.8  5156.1  5184.3  5201.9  5205.5
  5207.0  5219.9  5233.0  5241.3  5268.5  5276.1  5288.3  5311.5  5314.1
  778.00  777.65  776.62  776.70  776.52  776.31  774.94  775.48  774.07  773.73
  774.31  774.29  774.70  774.29  772.68  771.72  769.63  768.29  768.19  767.70
  766.95  766.85  765.14  764.11  764.13  763.25  761.63  760.67  759.62  759.60
  758.89  758.50  758.50  758.50  758.50  758.50  758.50  758.80  759.81  759.96
  760.36  760.54  760.24  760.17  759.92  760.60  762.10  763.75  764.32  764.68
  764.70  766.08  766.73  767.66  770.21  771.28  772.43  773.57  773.91
  729.00  729.00  729.00  729.00  729.00  729.00  729.00  729.00  729.00  729.00
  729.00  729.00  729.00  729.00  729.00  729.00  729.00  729.00  729.00  729.00
  729.00  729.00  729.00  729.00  729.00  729.00  729.00  729.00  729.00  729.00
  729.00  729.00  729.00  757.10  757.10  729.00  729.00  729.00  729.00  729.00
  729.00  729.00  729.00  729.00  729.00  729.00  729.00  729.00  729.00  729.00
  729.00  729.00  729.00  729.00  729.00  729.00  729.00  729.00  729.00
  4554.3  4556.4  4576.3  4581.0  4583.0  4597.3  4611.2  4619.0  4636.4  4638.9
  4649.3  4650.7  4667.3  4673.6  4687.9  4721.5  4750.0  4773.3  4777.3  4782.7
  4788.3  4791.8  4817.2  4827.7  4829.7  4837.9  4861.9  4878.0  4889.1  4890.7
  4899.6  4918.0  4978.5  4978.5  5021.5  5021.5  5058.8  5066.0  5078.9  5091.8
  5095.3  5105.1  5109.2  5113.8  5120.0  5134.8  5156.1  5184.3  5201.9  5205.5
  5207.0  5219.9  5233.0  5241.3  5268.5  5276.1  5288.3  5311.5  5314.1
  778.00  777.65  776.62  776.70  776.52  776.31  774.94  775.48  774.07  773.73
  774.31  774.29  774.70  774.29  772.68  771.72  769.63  768.29  768.19  767.70
  766.95  766.85  765.14  764.11  764.13  763.25  761.63  760.67  759.62  759.60
  758.89  758.50  758.50  758.50  758.50  758.50  758.50  758.80  759.81  759.96
  760.36  760.54  760.24  760.17  759.92  760.60  762.10  763.75  764.32  764.68
  764.70  766.08  766.73  767.66  770.21  771.28  772.43  773.57  773.91
  729.00  729.00  729.00  729.00  729.00  729.00  729.00  729.00  729.00  729.00
  729.00  729.00  729.00  729.00  729.00  729.00  729.00  729.00  729.00  729.00
  729.00  729.00  729.00  729.00  729.00  729.00  729.00  729.00  729.00  729.00
  729.00  729.00  729.00  757.10  757.10  729.00  729.00  729.00  729.00  729.00
  729.00  729.00  729.00  729.00  729.00  729.00  729.00  729.00  729.00  729.00
  729.00  729.00  729.00  729.00  729.00  729.00  729.00  729.00  729.00
Abutment Skew #Up #Dn=,2,2
  4978.5  4981.0
  757.10  749.00
  4978.5  4981.0
  757.10  748.75
Abutment Skew #Up #Dn=,2,2
  5019.0  5021.5
  749.00  757.10
  5019.0  5021.5
  748.75  757.10
BR Coef=1,1,0,1.25,0,,,0.8,0,2,0,
WSPro=,,,, 1 ,,,, 0 ,,,, 0 ,,,,-1 ,-1 ,-1 , 0 , 0 , 0 , 0 , 0
BC Design=,,0,,0,,,,,,

Type RM Length L Ch R = 1,4240,240,240,240
BEGIN DESCRIPTION:
Private Drive d/s Howards Cr
END DESCRIPTION:
XS GIS Cut Line= 5
      1317683.98       640983.88      1317472.84       640761.32
      1317361.56       640578.71      1317295.93       640478.84
      1317150.41       640353.30
#Sta/Elev= 30
  4538.0  779.83  4609.9  777.20  4648.7  776.07  4660.6  776.16  4758.6  771.54
  4765.8  770.19  4784.4  768.03  4820.2  765.29  4838.0  762.45  4846.9  761.98
  4858.8  762.26  4867.3  761.44  4889.3  760.81  4908.8  759.07  4929.5  757.98
  4940.5  758.29  4978.5  757.45  4981.0  748.75  5019.0  748.75  5021.5  757.45
  5068.2  758.69  5086.4  758.56  5106.2  760.17  5129.5  760.07  5155.0  760.73
  5207.5  763.52  5213.7  763.25  5226.0  764.82  5332.0  773.10  5370.3  778.11
#Mann=3,-1,0
  4538.0    0.15       0  4978.5    0.05       0  5021.5    0.08       0
#XS Ineff=2,0
    0.00 4934.50  758.50 5065.50    0.00  758.79
Bank Sta=4978.5,5021.5
XS Rating Curve= 0
Exp/Cntr=0.5,0.3

Type RM Length L Ch R = 1,4000,367,367,367
BEGIN DESCRIPTION:
Howards Creek 8.0
END DESCRIPTION:
XS GIS Cut Line= 3
      1317840.91       640678.57      1317450.01       640396.10
      1317167.53       640330.47
#Sta/Elev= 30
  4695.4  783.76  4704.1  783.41  4813.3  774.11  4852.1  769.37  4931.0  756.10
  4942.5  755.94  4974.0  758.28  4978.7  751.54  4980.2  748.54  5019.8  748.54
  5021.3  751.54  5034.1  759.12  5047.0  758.15  5063.0  757.83  5085.5  758.66
  5143.1  759.02  5170.0  758.23  5183.7  758.72  5215.8  757.79  5275.7  759.15
  5296.1  760.11  5309.6  761.15  5318.8  761.29  5332.4  762.48  5339.6  762.72
  5377.7  766.57  5399.5  768.21  5417.4  770.30  5425.5  770.50  5467.6  776.79
#Mann=3,-1,0
  4695.4    0.15       0  4978.7    0.05       0  5021.3    0.08       0
Bank Sta=4978.7,5021.3
XS Rating Curve= 0
Exp/Cntr=0.3,0.1

Type RM Length L Ch R = 1,3633,435,435,435
BEGIN DESCRIPTION:
Howards Creek 7.0
END DESCRIPTION:
XS GIS Cut Line= 3
      1318034.94       640463.15      1317917.95       640280.54
      1317278.81       640009.47
#Sta/Elev= 30
  4728.4  783.02  4805.3  776.90  4842.9  772.29  4874.5  767.24  4933.3  755.70
  4946.9  755.33  4978.7  751.23  4980.2  748.23  5019.8  748.23  5021.3  751.23
  5026.8  755.90  5062.1  759.25  5102.4  756.74  5127.2  757.97  5162.5  758.40
  5248.3  756.30  5281.1  756.23  5288.5  755.68  5300.8  756.20  5381.1  756.80
  5442.9  756.67  5464.3  755.66  5483.1  757.29  5490.3  756.86  5500.7  757.41
  5530.0  760.53  5551.4  764.13  5602.9  785.38  5629.4  795.54  5639.6  798.95
#Mann=3,-1,0
  4728.4    0.15       0  4978.7    0.05       0  5021.3    0.08       0
Bank Sta=4978.7,5021.3
XS Rating Curve= 0
Exp/Cntr=0.3,0.1

Type RM Length L Ch R = 1,3198,698,698,698
BEGIN DESCRIPTION:
Howards Creek 6.0
END DESCRIPTION:
XS GIS Cut Line= 5
      1318352.22       640222.14      1318207.75       639977.91
      1317905.04       639836.87      1317591.64       639696.67
      1317385.62       639688.96
#Sta/Elev= 30
  4657.1  778.00  4693.2  774.12  4741.1  767.64  4776.3  764.69  4824.2  758.93
  4838.4  755.75  4859.8  756.81  4880.9  756.65  4946.3  758.20  4949.8  758.03
  4978.7  750.85  4980.2  747.85  5019.8  747.85  5021.3  750.85  5026.5  754.54
  5043.8  758.08  5104.0  758.07  5130.4  755.95  5170.1  755.57  5221.5  756.99
  5357.4  756.14  5412.5  758.33  5482.7  755.90  5529.3  757.42  5583.0  755.81
  5609.8  757.61  5629.3  760.15  5744.0  764.36  5777.2  767.58  5824.3  774.65
#Mann=3,-1,0
  4657.1    0.15       0  4978.7    0.05       0  5021.3    0.15       0
Bank Sta=4978.7,5021.3
XS Rating Curve= 0
Exp/Cntr=0.3,0.1

Type RM Length L Ch R = 1,2500,500,500,500
BEGIN DESCRIPTION:
Howards Creek 5.0
END DESCRIPTION:
XS GIS Cut Line= 3
      1318875.00       639575.00      1318482.68       639357.29
      1318325.00       639225.00
#Sta/Elev= 30
  4551.3  766.77  4579.9  764.19  4633.7  753.36  4634.0  752.03  4635.4  752.59
  4645.0  753.55  4666.6  752.18  4684.6  753.41  4703.6  753.82  4709.0  753.53
  4727.2  754.04  4748.3  753.86  4800.7  754.77  4825.6  754.40  4900.3  755.87
  4925.5  755.82  4946.7  756.21  4961.8  757.51  4966.2  756.99  4976.8  750.42
  4978.3  747.42  5021.7  747.42  5023.2  750.42  5043.6  755.54  5057.9  757.97
  5077.3  762.52  5110.7  771.40  5137.6  779.26  5153.3  784.67  5205.8  798.61
#Mann=3,-1,0
  4551.3    0.08       0  4976.8    0.05       0  5023.2    0.15       0
Bank Sta=4976.8,5023.2
XS Rating Curve= 0
Exp/Cntr=0.3,0.1

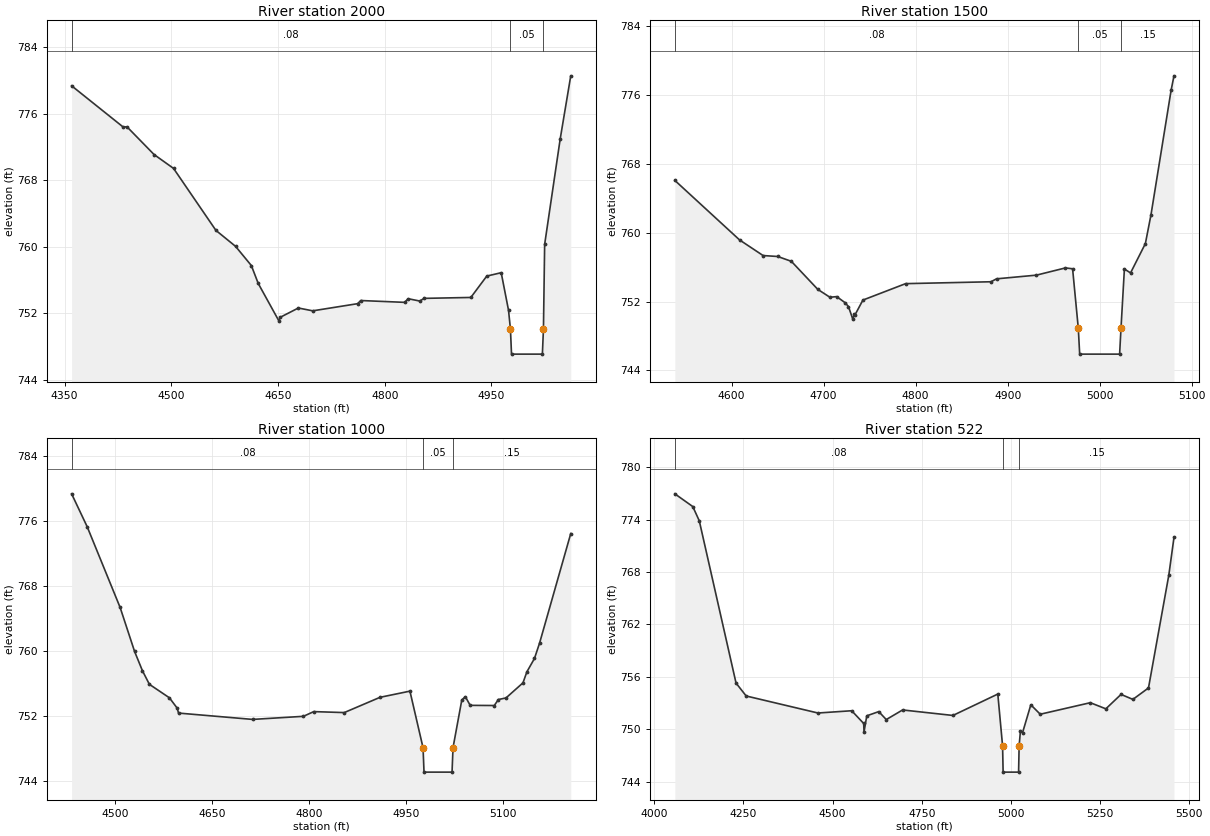
Type RM Length L Ch R = 1,2000,500,500,500
BEGIN DESCRIPTION:
Howards Creek 4.0
END DESCRIPTION:
XS GIS Cut Line= 3
      1319225.00       639275.00      1318696.88       638913.21
      1318648.40       638875.28
#Sta/Elev= 30
  4359.8  779.37  4432.1  774.42  4437.7  774.43  4475.7  771.10  4503.1  769.43
  4562.7  761.97  4590.3  760.05  4612.5  757.74  4622.2  755.58  4651.1  751.10
  4653.3  751.52  4678.6  752.63  4698.8  752.29  4761.8  753.15  4766.4  753.53
  4828.1  753.31  4832.9  753.75  4849.2  753.47  4855.4  753.79  4921.1  753.90
  4943.5  756.47  4963.8  756.88  4974.1  752.36  4976.8  750.08  4978.3  747.08
  5021.7  747.08  5023.2  750.08  5024.9  760.29  5046.8  773.00  5061.6  780.57
#Mann=3,-1,0
  4359.8    0.08       0  4976.8    0.05       0  5023.2    0.15       0
Bank Sta=4976.8,5023.2
XS Rating Curve= 0
Exp/Cntr=0.3,0.1

Type RM Length L Ch R = 1,1500,500,500,500
BEGIN DESCRIPTION:
Howards Creek 3.0
END DESCRIPTION:
XS GIS Cut Line= 3
      1319275.00       639075.00      1319111.85       638643.04
      1319056.43       638584.24
#Sta/Elev= 30
  4538.3  766.09  4608.6  759.17  4634.2  757.35  4650.1  757.24  4664.9  756.68
  4693.7  753.41  4706.8  752.50  4714.2  752.57  4723.4  751.86  4727.0  751.41
  4731.8  749.92  4733.4  750.57  4733.9  750.41  4742.7  752.17  4789.1  754.08
  4881.9  754.30  4887.9  754.64  4931.3  755.07  4962.8  755.91  4970.6  755.81
  4976.8  748.88  4978.3  745.88  5021.7  745.88  5023.2  748.88  5026.9  755.78
  5033.6  755.33  5049.7  758.74  5055.8  762.09  5077.7  776.60  5080.8  778.26
#Mann=3,-1,0
  4538.3    0.08       0  4976.8    0.05       0  5023.2    0.15       0
Bank Sta=4976.8,5023.2
XS Rating Curve= 0
Exp/Cntr=0.3,0.1

Type RM Length L Ch R = 1,1000,478,478,478
BEGIN DESCRIPTION:
Howards Creek 2.0
END DESCRIPTION:
XS GIS Cut Line= 3
      1319775.00       638875.00      1319524.50       638365.97
      1319375.00       638225.00
#Sta/Elev= 30
  4432.7  779.38  4456.9  775.31  4507.8  765.39  4530.2  759.97  4542.4  757.59
  4553.1  755.93  4584.1  754.27  4596.2  752.99  4598.2  752.39  4712.9  751.61
  4791.6  751.99  4807.6  752.57  4854.8  752.45  4910.2  754.33  4956.5  755.09
  4976.8  748.12  4978.3  745.12  5021.7  745.12  5023.2  748.12  5036.8  754.00
  5042.3  754.41  5049.8  753.34  5087.1  753.32  5093.5  754.06  5105.2  754.25
  5131.5  756.11  5137.6  757.47  5149.3  759.11  5157.2  761.00  5205.5  774.49
#Mann=3,-1,0
  4432.7    0.08       0  4976.8    0.05       0  5023.2    0.15       0
Bank Sta=4976.8,5023.2
XS Rating Curve= 0
Exp/Cntr=0.3,0.1

Type RM Length L Ch R = 1,522,0,0,0
BEGIN DESCRIPTION:
Howards Creek 1.0
END DESCRIPTION:
XS GIS Cut Line= 3
      1320061.78       638892.11      1319936.68       638091.45
      1319475.00       637725.00
#Sta/Elev= 30
  4057.7  776.96  4108.0  775.50  4126.2  773.87  4229.3  755.29  4257.7  753.81
  4459.0  751.86  4553.7  752.12  4587.3  750.66  4588.2  749.70  4596.0  751.54
  4629.5  752.02  4650.6  751.11  4696.4  752.21  4837.5  751.58  4963.4  754.03
  4976.8  748.09  4978.3  745.09  5021.7  745.09  5023.2  748.09  5026.9  749.82
  5032.9  749.62  5056.0  752.80  5082.4  751.72  5222.8  753.04  5266.4  752.34
  5309.0  753.99  5342.2  753.42  5386.0  754.73  5443.0  767.65  5457.5  771.97
#Mann=3,-1,0
  4057.7    0.08       0  4976.8    0.05       0  5023.2    0.15       0
Bank Sta=4976.8,5023.2
XS Rating Curve= 0
Exp/Cntr=0.3,0.1

Chan Stop Cuts=-1